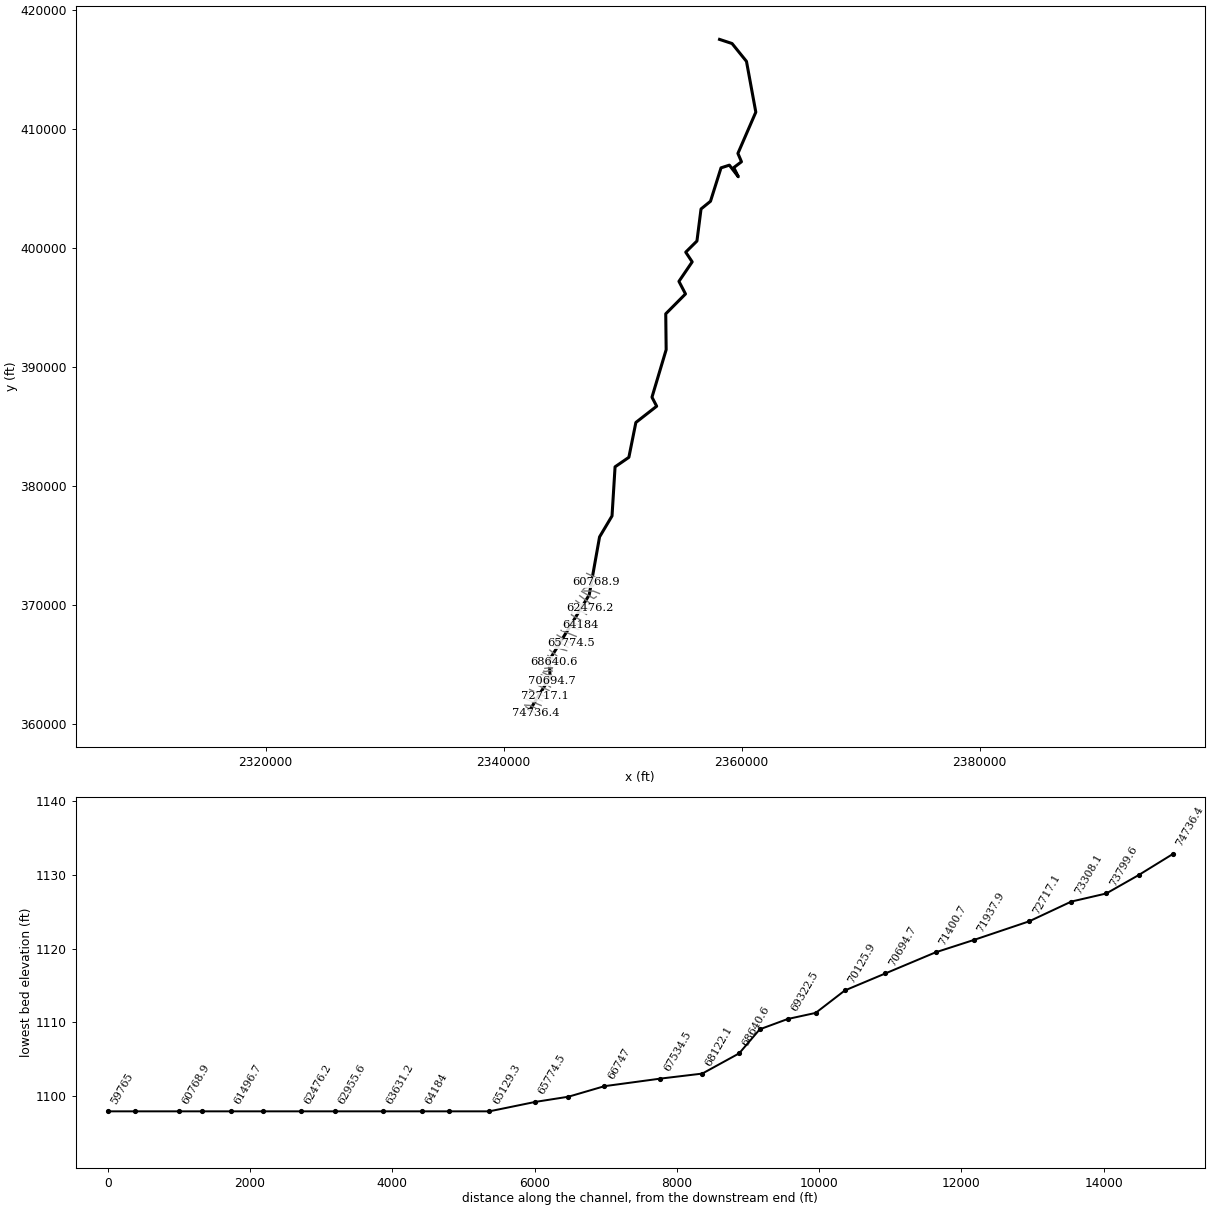
--- MEADOWBRCH.prj (project) ---

Proj Title=MEADOWBRCH
Current Plan=p01
Default Exp/Contr=0,0
English Units
Geom File=g01
Flow File=f01
Plan File=p01
BEGIN DESCRIPTION:
END DESCRIPTION:
DSS Export Rating Curves= 0
DSS Export Rating Curve Sorted= 0
DSS Export Volume Flow Curves= 0
DXF OffsetX= 0
DXF OffsetY= 0
DXF ScaleX= 0
DXF ScaleY= 0

--- MEADOWBRCH.p01 (plan) ---

Plan Title=Floodplain
Program Version=4.00
Geom File=g01
Flow File=f01
K Sum by GR=0
Std Step Tol=0.01
Critical Tol=0.01
Num of Std Step Trials=20
Max Error Tol=0.3
Flow Tol Ratio=0.001
Split Flow NTrial=30
Split Flow Tol=0.02
Split Flow Ratio=0.02
Log Output Level=0
Friction Slope Method=1
Unsteady Friction Slope Method=2
Unsteady Bridges Friction Slope Method=1
Global Log Level=0
CheckData=False
Run HTab=0
Run UNet=0
Run PostProcess=0
UNET Theta=0
UNET Theta Warmup=0
UNET ZTol=0
UNET ZSATol=0
UNET MxIter=0
UNET MaxInSteps=0
UNET DtIC=0
UNET DtMin=0
UNET MaxCRTS=0
UNET WFStab=0
UNET SFStab=0
UNET WFX=0
UNET SFX=0
UNET DSS MLevel=0
UNET DZMax Abort=0
UNET Convert EG Bridges=0
UNET Use Existing IB Tables=0
UNET Froude Limit=0
UNET Froude Power=0
Write IC File=0
Echo Input=False
Echo Output=False
Write Detailed=0

--- MEADOWBRCH.f01 (steady flow) ---

Flow Title=NFF Regression Equation
Program Version=4.00
Number of Profiles=1
Profile Names=P100yr
River Rch & RM=MEADOWBRCH,Main      ,74736.4
541.0649
River Rch & RM=MEADOWBRCH,Main      ,73799.6
568.4033
River Rch & RM=MEADOWBRCH,Main      ,72717.1
607.1135
River Rch & RM=MEADOWBRCH,Main      ,71400.7
669.1586
River Rch & RM=MEADOWBRCH,Main      ,68930.1
696.7008
River Rch & RM=MEADOWBRCH,Main      ,68640.6
1213.032
River Rch & RM=MEADOWBRCH,Main      ,68122.1
1263.720
River Rch & RM=MEADOWBRCH,Main      ,64567.7
1368.178
River Rch & RM=MEADOWBRCH,Main      ,62955.6
1509.903
River Rch & RM=MEADOWBRCH,Main      ,61952.8
1577.632
River Rch & RM=MEADOWBRCH,Main      ,60149.7
1722.475
River Rch & RM=MEADOWBRCH,Main      ,57590.2
1883.984
River Rch & RM=MEADOWBRCH,Main      ,54771.7
2022.129
River Rch & RM=MEADOWBRCH,Main      ,52242.9
2195.701
River Rch & RM=MEADOWBRCH,Main      ,47702.5
2405.742
River Rch & RM=MEADOWBRCH,Main      ,41619.9
2668.796
River Rch & RM=MEADOWBRCH,Main      ,35215.6
2953.062
River Rch & RM=MEADOWBRCH,Main      ,27700.8
3232.437
River Rch & RM=MEADOWBRCH,Main      ,16736.3
3569.098
River Rch & RM=MEADOWBRCH,Main      ,592.9
3965.393
River Rch & RM=MEADOWBRCH,Main      ,102.9
3966.674
Boundary for River Rch & Prof#=MEADOWBRCH,Main      ,1
Up Type=0
Dn Type=3
Dn Slope=0.013951

--- MEADOWBRCH.g01 (geometry) ---

Geom Title=USGS 10m DEM
Program Version=4.10

River Reach=MEADOWBRCH      ,Main
Reach XY= 30
     2342214.458      361193.212     2343903.694      363941.475
     2343843.798      365371.163     2347194.927      370848.594
     2348064.718      375718.385     2349111.593      377478.975
     2349367.496      381603.455     2350527.218      382402.066
      2351115.76      385329.149     2352864.024      386693.732
      2352468.19      387448.941     2353660.899       391440.26
     2353626.176      394452.413     2355285.899      396122.552
     2354733.815      397178.108     2355848.399       398815.26
     2355304.996      399631.233     2356247.704      400566.996
     2356591.454      403257.968     2357386.593      403905.538
      2358272.01      406711.093     2358972.458      406937.294
     2359723.326      405965.072     2359344.637      406734.386
     2359989.168      407222.667     2359690.774      407925.793
     2361194.681      411388.972     2360409.959      415652.862
     2359198.153      417151.125     2358147.392      417498.146

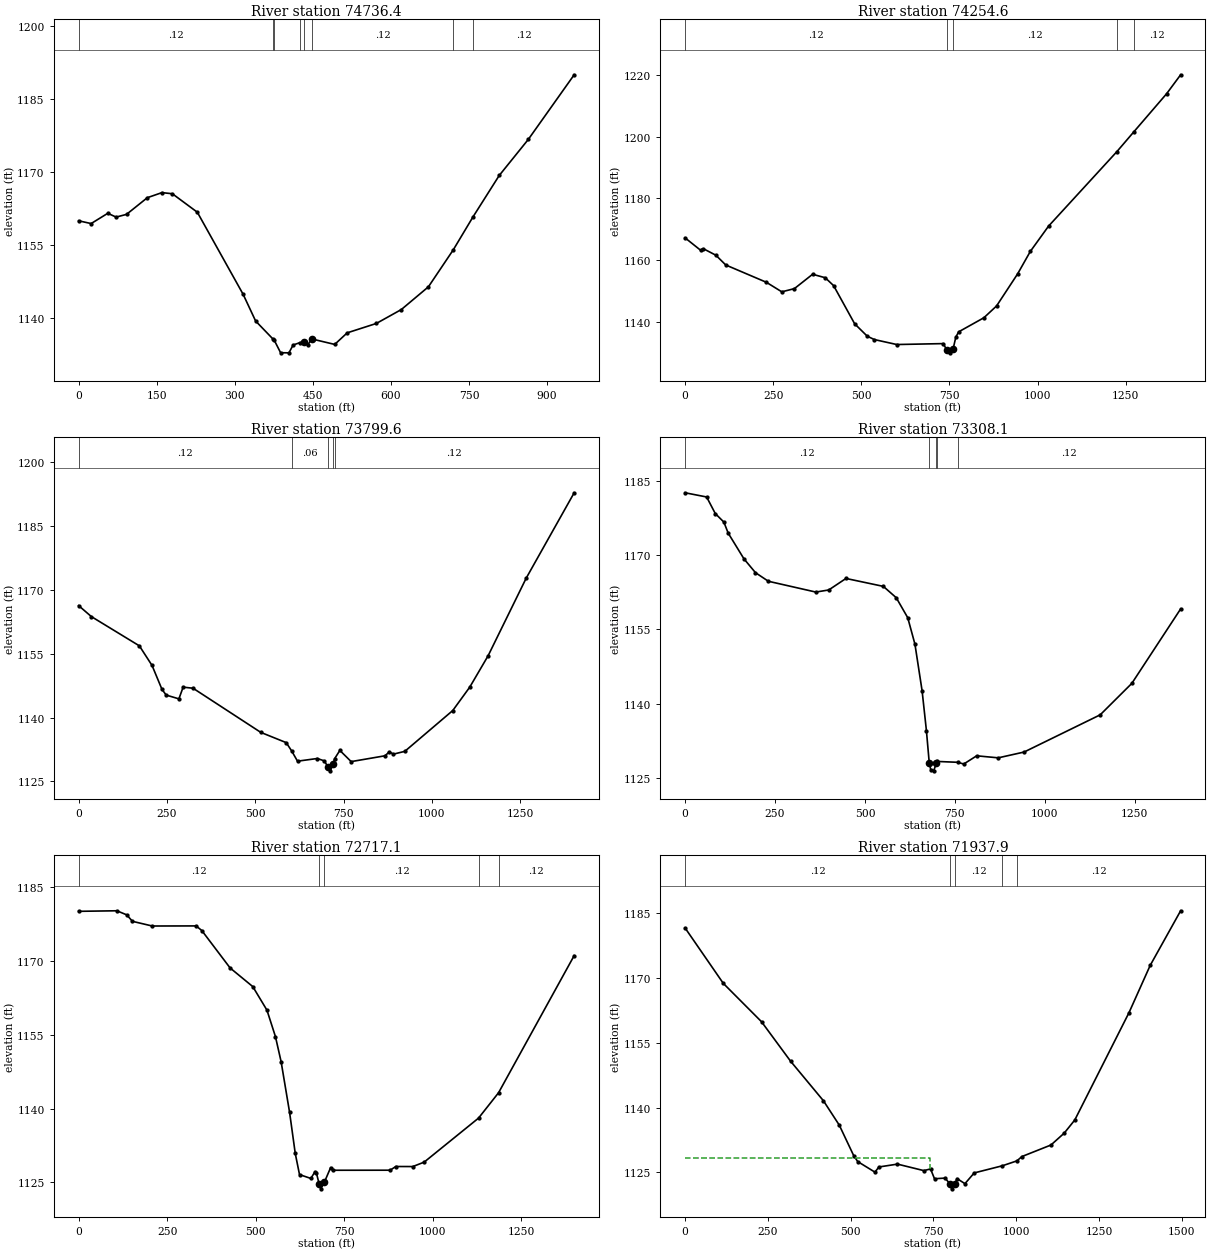
Type RM Length L Ch R = 1 ,74736.4 ,466.4,481.8,482.6
XS GIS Cut Line= 2
     2341876.114      361455.166     2342660.614      360916.037
#Sta/Elev= 30
       0    1160      24 1159.43      56 1161.54      72 1160.76      92 1161.32
     132 1164.75     160 1165.79     180 1165.56     228 1161.76     316 1144.89
     340  1139.4  373.591135.669  375.641135.474     388 1132.88     404 1132.86
     412 1134.47   424.9 1134.95     432    1135   439.9 1134.47     448 1135.71
   491.9 1134.59   515.9 1136.97   571.9  1138.9   619.9 1141.76   671.9 1146.43
  719.791154.053  757.451160.784   807.9 1169.31   863.9 1176.74   951.9 1190.01
#Mann= 8 ,-1 , 0
       0     .12       0  373.59     .06       0  375.64     .12       0
   424.9    .045       0     432    .045       0     448     .12       0
  719.79    .016       0  757.45     .12       0
Bank Sta=432,448
XS Rating Curve= 0 ,0
Exp/Cntr=0.3,0.1

Type RM Length L Ch R = 1 ,74254.6 ,455,455,454
XS GIS Cut Line= 3
     2341773.978      361596.287     2342250.024      361566.627
     2343067.228      361125.424
#Sta/Elev= 30
       0  1167.2    43.7 1163.22    51.7  1163.7    87.4 1161.58   115.3 1158.43
   230.5 1152.83   274.3 1149.74     310 1150.77   361.7 1155.42   397.5  1154.3
   421.3 1151.74     481 1139.39   516.8 1135.37   536.8 1134.29   600.5 1132.68
   732.1 1132.98   741.8 1131.06     752 1129.99     760 1131.11   767.9 1135.04
   775.9 1136.78   847.6 1141.35   883.5 1145.16   943.3 1155.55   979.2  1162.8
    1031    1171 1224.81 1195.11 1272.451201.461  1365.8 1213.84  1405.7 1219.99
#Mann= 5 ,-1 , 0
       0     .12       0   741.8    .045       0     760     .12       0
 1224.81    .016       0 1272.45     .12       0
Bank Sta=741.8,760
XS Rating Curve= 0 ,0
Exp/Cntr=0.3,0.1

Type RM Length L Ch R = 1 ,73799.6 ,480.1,491.5,500.4
XS GIS Cut Line= 3
     2341869.125      362121.237     2342531.857       361821.25
     2343155.104      361561.728
#Sta/Elev= 30
       0 1166.33      36 1163.75   171.9 1156.87   207.8 1152.26   235.8 1146.66
   247.8  1145.3   283.8 1144.41   295.8 1147.16   323.8 1146.91   515.6 1136.53
   587.6 1134.12  603.54 1132.09   619.5 1129.76   675.5 1130.39   695.5 1129.83
   705.5 1128.42   711.5 1127.49   720.5  1129.2  724.72 1130.37   739.4 1132.29
   771.4 1129.66   867.3 1131.03   879.3 1131.95   891.2 1131.42   923.2 1132.07
    1059 1141.67    1107 1147.16  1158.9 1154.52  1266.8 1172.78  1402.6 1192.85
#Mann= 5 ,-1 , 0
       0     .12       0  603.54     .06       0   705.5    .045       0
   720.5     .06       0  724.72     .12       0
Bank Sta=705.5,720.5
XS Rating Curve= 0 ,0
Exp/Cntr=0.3,0.1

Type RM Length L Ch R = 1 ,73308.1 ,597.6,591,584.2
XS GIS Cut Line= 2
     2342002.638      362531.948     2343247.599      361941.858
#Sta/Elev= 30
       0 1182.63    59.9 1181.78    83.9 1178.43   107.8  1176.7   119.8 1174.47
   163.7 1169.26   195.7 1166.47   231.6 1164.73   363.4 1162.55   399.3 1162.97
   447.3  1165.3   551.1  1163.7     587 1161.41     619 1157.36     639 1152.01
   658.9 1142.59   670.9 1134.54   678.9 1127.91   682.9 1126.65   690.9 1126.39
   698.8  1127.9   700.9 1128.29   757.91128.117   774.7 1127.77   810.7 1129.43
   870.6 1129.02   942.4 1130.19  1154.1 1137.72    1242 1144.08  1377.7 1159.14
#Mann= 5 ,-1 , 0
       0     .12       0   678.9    .045       0   698.8    .045       0
   700.9     .06       0   757.9     .12       0
Bank Sta=678.9,698.8
XS Rating Curve= 0 ,0
Exp/Cntr=0.3,0.1

Type RM Length L Ch R = 1 ,72717.1 ,774.8,779.3,764.1
XS GIS Cut Line= 2
     2342192.114      362908.115      2343467.34      362333.184
#Sta/Elev= 30
       0    1180   107.9 1180.11   135.9 1179.28   151.9 1177.97   207.8 1177.02
   331.7 1177.04   347.7  1176.1   427.6 1168.51   491.6 1164.73   531.6 1159.95
   555.5  1154.6   571.5 1149.53   595.5 1139.21   611.5 1130.88   623.5  1126.6
   655.5 1125.82   667.4 1127.21   671.4 1126.87   678.6 1124.79   683.4 1123.71
   693.6 1125.04   711.4 1128.03   719.4 1127.48   879.3 1127.49   895.3 1128.24
   943.2 1128.23   975.2 1129.12 1128.851138.057 1185.431143.209  1398.8 1171.02
#Mann= 5 ,-1 , 0
       0     .12       0   678.6    .045       0   693.6     .12       0
 1128.85    .016       0 1185.43     .12       0
Bank Sta=678.6,693.6
XS Rating Curve= 0 ,0
Exp/Cntr=0.3,0.1

Type RM Length L Ch R = 1 ,71937.9 ,538.3,537.1,530.4
XS GIS Cut Line= 3
     2342744.778       363708.65      2342922.73       363235.56
     2343823.626      362822.041
#Sta/Elev= 30
       0 1181.64   115.4  1168.8   230.8 1159.91   318.4 1150.78   417.9 1141.58
   465.6 1135.95   509.4 1128.84   521.4 1127.49   573.4 1125.04   585.4 1126.24
   641.4  1126.9   721.3 1125.39   741.3 1125.79   753.3 1123.51   785.2 1123.66
     800 1122.32   805.2 1121.17     815 1122.25   821.2 1123.56   845.2 1122.37
   873.2 1124.86  958.181126.515 1002.281127.654  1017.1 1128.65    1105 1131.33
    1145 1134.08    1177 1137.13  1340.8 1162.02  1404.8 1172.98  1496.7 1185.63
#Mann= 5 ,-1 , 0
       0     .12       0     800    .045       0     815     .12       0
  958.18    .016       0 1002.28     .12       0
#XS Ineff= 2 , 0
          738.95 1128.42
Permanent Ineff=
       F       F
Bank Sta=800,815
XS Rating Curve= 0 ,0
Exp/Cntr=0.3,0.1

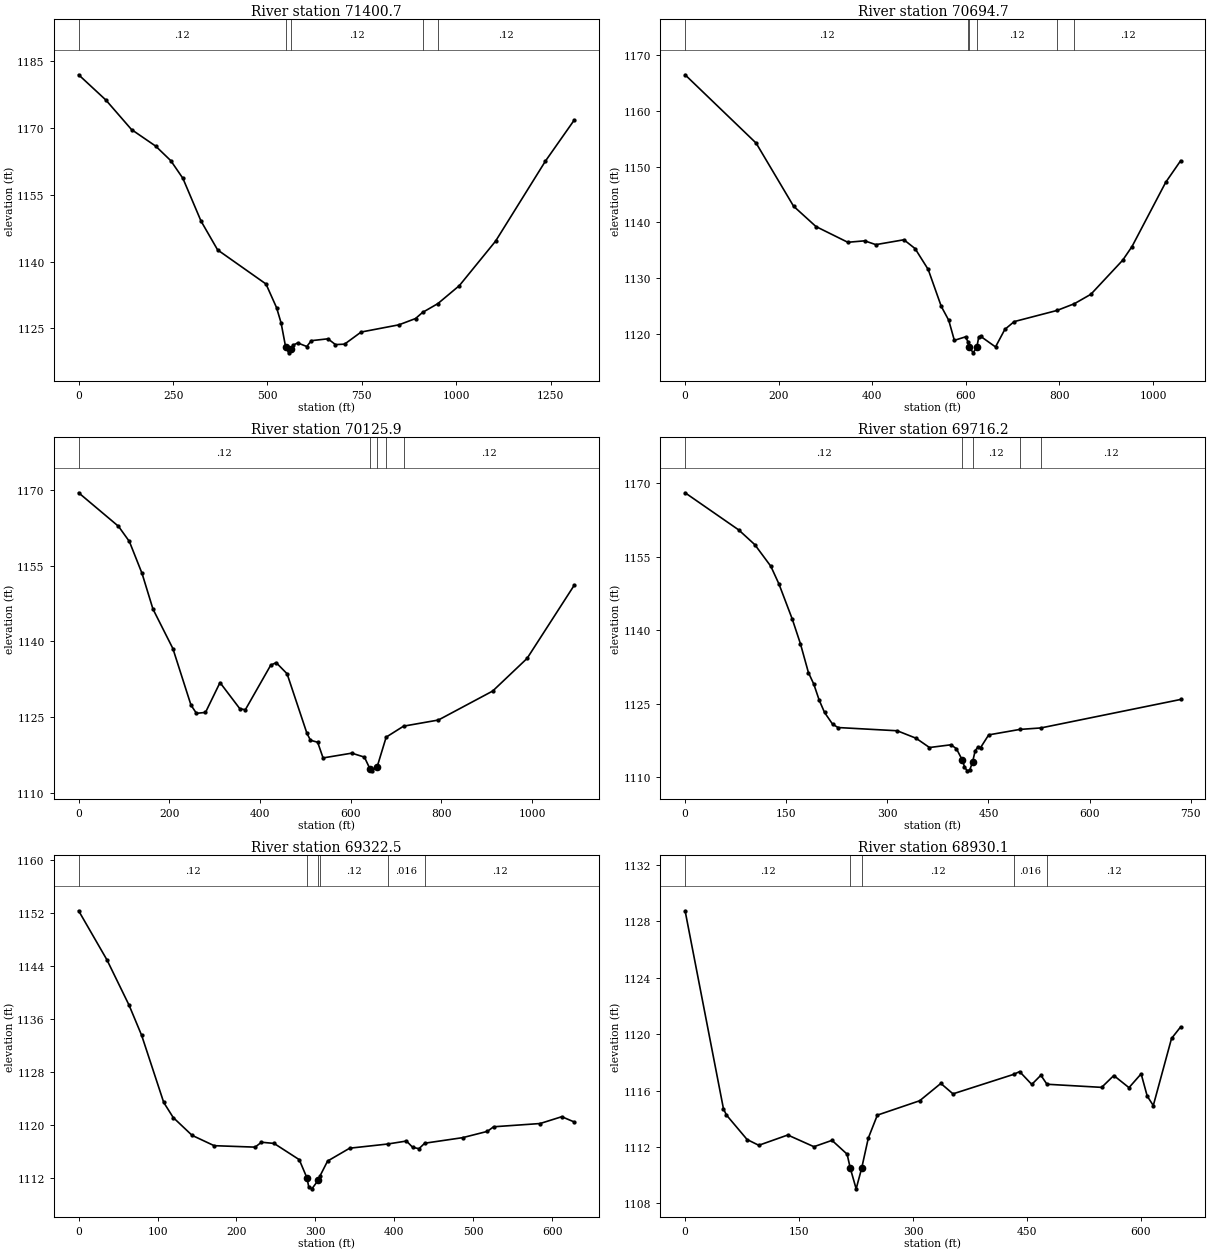
Type RM Length L Ch R = 1 ,71400.7 ,714.9,706,624
XS GIS Cut Line= 2
     2342861.651      363855.402     2343939.677      363107.779
#Sta/Elev= 30
       0 1181.93      72 1176.27     140 1169.63     204 1165.91     244 1162.64
     276 1158.68     324 1149.08     368  1142.6     496 1134.95     524 1129.64
     536 1126.21   547.9 1120.86     556 1119.49   562.9 1120.26     568 1121.23
     580 1121.72     604 1120.91     616 1122.22     660 1122.64     680 1121.34
     704 1121.44   747.9 1124.16   847.9 1125.78   891.9 1127.19   910.51128.564
  951.021130.545  1007.9 1134.58  1103.9 1144.58  1235.9 1162.56  1311.9 1171.74
#Mann= 5 ,-1 , 0
       0     .12       0   547.9    .045       0   562.9     .12       0
   910.5    .016       0  951.02     .12       0
Bank Sta=547.9,562.9
XS Rating Curve= 0 ,0
Exp/Cntr=0.3,0.1

Type RM Length L Ch R = 1 ,70694.7 ,549,568.8,598
XS GIS Cut Line= 2
     2343167.955      364144.848     2344092.435      363628.355
#Sta/Elev= 30
       0 1166.47   151.8 1154.22   231.8 1142.91   279.7 1139.26   347.7 1136.44
   383.6  1136.7   407.6 1136.02   467.6 1136.89   491.5 1135.31   519.5 1131.57
   547.5 1124.94   563.4 1122.46   575.4 1118.86   599.4 1119.49   604.7 1118.57
   607.4 1117.73   615.4 1116.62   623.4 1117.61   627.4 1119.39   631.4 1119.59
   663.4 1117.68   683.3 1120.82   703.3 1122.22  794.631124.214  831.831125.425
   867.2 1127.12   935.1 1133.22   955.1 1135.68    1027 1147.18    1059 1151.06
#Mann= 6 ,-1 , 0
       0     .12       0   604.7    .045       0   607.4    .045       0
   623.4     .12       0  794.63    .016       0  831.83     .12       0
Bank Sta=607.4,623.4
XS Rating Curve= 0 ,0
Exp/Cntr=0.3,0.1

Type RM Length L Ch R = 1 ,70125.9 ,405.3,409.7,413.7
XS GIS Cut Line= 4
     2343313.355      364322.799     2343736.532      364114.466
     2343986.098      364125.317     2344292.087      363914.813
#Sta/Elev= 30
       0 1169.47    87.9 1162.82   111.9 1159.81   139.9 1153.46   163.9 1146.41
   207.9 1138.56   247.8 1127.35   259.8 1125.72   279.8  1125.9   311.8 1131.82
   355.8  1126.6   367.8 1126.45   423.7 1135.28   435.7 1135.77   459.7 1133.57
   503.4 1121.78   511.3 1120.38   527.2 1119.98   539.1 1116.87   602.5 1117.82
   630.3 1117.03     643 1114.61   646.1 1114.31     658    1115  678.281120.997
  716.661123.173   793.4 1124.39   913.2 1130.14     989 1136.61  1092.9 1151.11
#Mann= 5 ,-1 , 0
       0     .12       0     643    .045       0     658     .12       0
  678.28    .016       0  716.66     .12       0
Bank Sta=643,658
XS Rating Curve= 0 ,0
Exp/Cntr=0.3,0.1

Type RM Length L Ch R = 1 ,69716.2 ,412.5,393.7,390.6
XS GIS Cut Line= 4
     2343374.119      364446.497     2343553.926      364413.128
     2343880.553      364504.666     2344085.924      364448.667
#Sta/Elev= 30
       0 1168.02    79.5 1160.44   103.4 1157.43   127.2 1153.01   139.2  1149.4
     159 1142.22     171 1137.23   182.9 1131.33   190.9 1128.95   198.8 1125.73
   206.8 1123.18   218.8 1120.78   226.8  1120.1   314.6 1119.44   342.5 1117.92
   362.5 1116.02   394.4 1116.58   402.4 1115.78   411.3 1113.43   414.3 1112.12
   418.3 1111.26   422.3 1111.47   426.3 1113.01   430.3 1115.39   434.3 1116.09
   438.3 1116.01   450.3  1118.6  496.481119.714  527.721120.017     735 1125.83
#Mann= 5 ,-1 , 0
       0     .12       0   411.3    .045       0   426.3     .12       0
  496.48    .016       0  527.72     .12       0
Bank Sta=411.3,426.3
XS Rating Curve= 0 ,0
Exp/Cntr=0.3,0.1

Type RM Length L Ch R = 1 ,69322.5 ,368.6,392.4,354.6
XS GIS Cut Line= 3
     2343465.264      364683.042     2343910.326      364726.754
     2344075.074       364652.66
#Sta/Elev= 30
       0 1152.37    35.9 1144.96    63.9 1138.13    79.9 1133.56   107.8 1123.46
   119.8 1121.19   143.7  1118.5   171.7 1116.94   223.6 1116.72   231.6 1117.46
   247.6 1117.28   279.5 1114.83  289.26 1112.08   291.5 1110.74   295.5 1110.43
   303.5 1111.72   305.9  1112.4   315.4 1114.62   343.4 1116.56  391.661117.192
   415.3 1117.64   423.2 1116.69   431.2 1116.49  438.471117.312   486.5 1118.15
   517.9  1119.1   525.7 1119.79   584.6 1120.28   612.1 1121.31   627.8 1120.52
#Mann= 6 ,-1 , 0
       0     .12       0  289.26    .045       0   303.5    .045       0
   305.9     .12       0  391.66    .016       0  438.47     .12       0
Bank Sta=289.26,303.5
XS Rating Curve= 0 ,0
Exp/Cntr=0.3,0.1

Type RM Length L Ch R = 1 ,68930.1 ,309.9,289.5,331.9
XS GIS Cut Line= 5
     2343690.644      365084.786     2343768.769      365041.383
     2343849.064      365016.426      2343858.83      364789.647
     2344103.285      364728.615
#Sta/Elev= 30
       0 1128.76    50.5 1114.71    54.4 1114.27    81.6 1112.53      97 1112.12
   135.2 1112.85   169.6 1112.02   193.4 1112.47   213.3 1111.49   217.4 1110.51
   225.2 1109.03   232.4 1110.48   241.2 1112.63   253.1 1114.26   308.8 1115.28
   336.7 1116.51   352.7 1115.77  432.821117.157   440.4 1117.35   456.4 1116.44
   468.4 1117.09  476.381116.452   548.4 1116.23   564.4 1117.07   584.4 1116.21
   600.4 1117.19   608.4 1115.61   616.4 1114.94   640.4  1119.7   652.4 1120.52
#Mann= 5 ,-1 , 0
       0     .12       0   217.4    .045       0   232.4     .12       0
  432.82    .016       0  476.38     .12       0
Bank Sta=217.4,232.4
XS Rating Curve= 0 ,0
Exp/Cntr=0.3,0.1

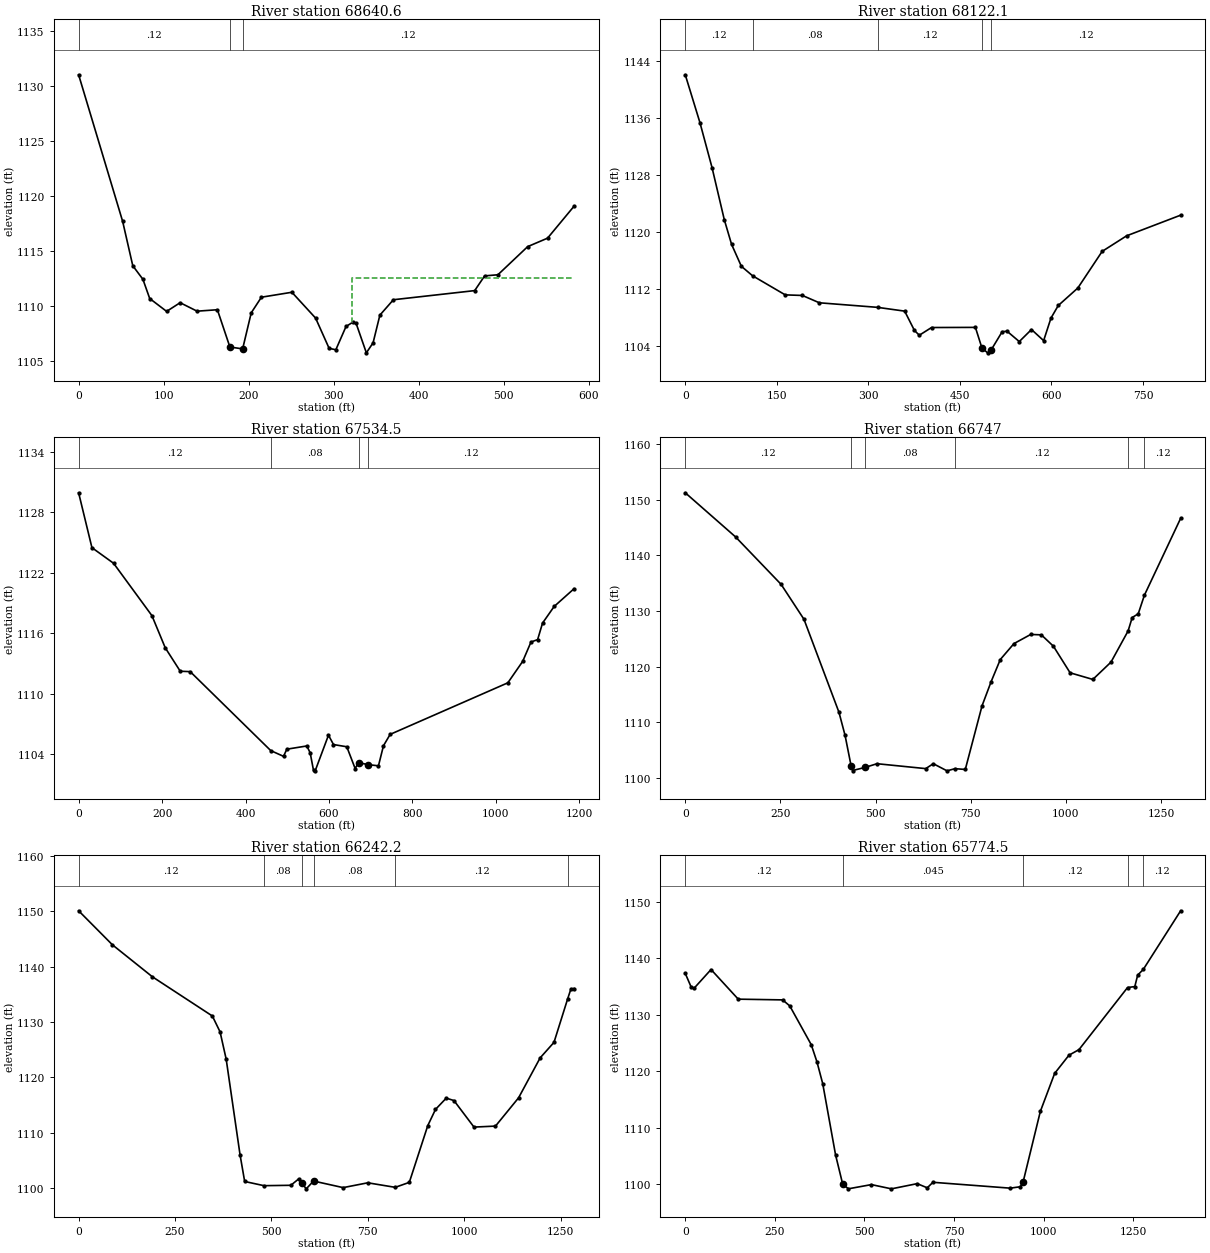
Type RM Length L Ch R = 1 ,68640.6 ,539.6,518.5,497.1
XS GIS Cut Line= 3
      2343698.24       365120.81     2344149.629      365250.801
     2344262.476       365254.49
#Sta/Elev= 30
       0 1131.05    51.8 1117.71    63.7 1113.68    75.6 1112.45    83.6  1110.7
   103.5 1109.53   119.4 1110.32   139.3 1109.55   163.2 1109.68   177.9 1106.29
   192.9 1106.12     203  1109.4     215 1110.82   250.8 1111.27   278.7 1108.92
   294.6 1106.17   302.5 1106.04   314.5 1108.16   322.4 1108.54   326.4 1108.43
   338.4 1105.76   346.3 1106.67   354.3 1109.19   370.2 1110.59   465.8 1111.42
   477.5 1112.76   493.1 1112.86   528.1 1115.42   551.5 1116.19   582.6 1119.09
#Mann= 3 ,-1 , 0
       0     .12       0   177.9    .045       0   192.9     .12       0
#XS Ineff= 2 , 0
                          321.88         1112.61
Permanent Ineff=
       F       F
Bank Sta=177.9,192.9
XS Rating Curve= 0 ,0
Exp/Cntr=0.3,0.1

Type RM Length L Ch R = 1 ,68122.1 ,579.5,587.7,594.2
XS GIS Cut Line= 3
     2343725.681      365759.431     2344336.085      365321.893
     2344372.383       365273.32
#Sta/Elev= 30
       0 1142.01      24 1135.31    43.9 1128.98    63.9  1121.7    75.9 1118.22
    91.9 1115.15  110.221113.823   163.8 1111.14   191.8 1111.06   219.7 1110.03
  315.06 1109.39   359.5 1108.86   375.5 1106.15   383.5 1105.48   403.5 1106.56
   475.4 1106.58   486.1 1103.69   495.4 1103.01   501.1  1103.4   519.3 1105.98
   527.3 1106.04   547.3 1104.59   567.3 1106.28   587.2 1104.72   599.2 1107.88
   611.2 1109.65   643.2  1112.1   683.1 1117.24   723.1 1119.42   811.7 1122.32
#Mann= 5 ,-1 , 0
       0     .12       0  110.22     .08       0  315.06     .12       0
   486.1    .045       0   501.1     .12       0
Bank Sta=486.1,501.1
XS Rating Curve= 0 ,0
Exp/Cntr=0.3,0.1

Type RM Length L Ch R = 1 ,67534.5 ,782.9,787.4,790.2
XS GIS Cut Line= 3
     2343884.872       366214.56     2344513.442      365696.497
     2344580.716      365329.744
#Sta/Elev= 30
       0 1129.94    31.9 1124.49    83.8 1122.94   175.7 1117.74   207.6 1114.55
   243.6 1112.22   267.5 1112.18  460.51 1104.34   491.1 1103.77   499.1 1104.48
     547  1104.8     555 1104.12     563 1102.38     567 1102.33   598.9 1105.87
   610.9 1104.94   642.8 1104.72   662.8 1102.56   670.9 1103.14   694.8 1102.94
   718.7 1102.83   730.7 1104.82   746.7 1105.95  1028.8 1111.07  1064.4  1113.2
  1084.3 1115.12  1100.2 1115.36    1112    1117  1139.8 1118.65  1187.4 1120.41
#Mann= 4 ,-1 , 0
       0     .12       0  460.51     .08       0   670.9    .045       0
   694.8     .12       0
Bank Sta=670.9,694.8
XS Rating Curve= 0 ,0
Exp/Cntr=0.3,0.1

Type RM Length L Ch R = 1 ,66747   ,510.4,504.9,499.6
XS GIS Cut Line= 3
     2344061.955      366563.518     2344926.538      366274.456
     2345301.538      366167.685
#Sta/Elev= 30
       0 1151.25     132 1143.33   251.9 1134.79   311.9 1128.52   403.8 1111.82
   419.8 1107.68   435.8 1102.16   439.8 1101.36   472.5 1101.92   503.8 1102.58
   631.7  1101.7   651.7 1102.58   687.7  1101.3  708.591101.688   735.7 1101.55
   779.7 1112.98   803.7 1117.34   827.7  1121.3   863.6 1124.16   907.6  1125.8
   935.5 1125.73   967.3 1123.68  1011.1 1118.91  1070.8 1117.72  1118.5 1120.83
 1163.481126.435  1174.2 1128.84  1190.1 1129.51 1206.241132.845  1301.5 1146.66
#Mann= 6 ,-1 , 0
       0     .12       0   435.8    .045       0   472.5     .08       0
  708.59     .12       0 1163.48    .016       0 1206.24     .12       0
Bank Sta=435.8,472.5
XS Rating Curve= 0 ,0
Exp/Cntr=0.3,0.1

Type RM Length L Ch R = 1 ,66242.2 ,465.9,467.6,467.1
XS GIS Cut Line= 3
     2344267.684      366849.977     2344590.601      366938.518
     2345399.343      366440.375
#Sta/Elev= 30
       0 1150.08    87.7 1143.93   191.3 1138.16   346.8 1131.08   366.8 1128.22
   382.7 1123.28   418.6 1106.04   430.6  1101.2  480.731100.441   550.4 1100.51
   570.3 1101.64   578.3 1100.96   590.3 1099.87   609.2 1101.28     686 1100.09
   749.9 1100.96   821.11100.142   857.6 1101.04   905.5 1111.29   925.5 1114.21
   953.4 1116.25   973.4 1115.81  1025.3 1111.02  1081.1  1111.2    1141 1116.31
  1196.9 1123.52  1232.8 1126.32 1268.441134.218  1276.7 1135.97  1284.7 1136.04
#Mann= 6 ,-1 , 0
       0     .12       0  480.73     .08       0   578.3    .045       0
   609.2     .08       0   821.1     .12       0 1268.44    .016       0
Bank Sta=578.3,609.2
XS Rating Curve= 0 ,0
Exp/Cntr=0.3,0.1

Type RM Length L Ch R = 1 ,65774.5 ,641.7,645.2,648.8
XS GIS Cut Line= 2
     2344496.859       367485.01     2345679.143      366769.247
#Sta/Elev= 30
       0 1137.33      16 1134.98      24 1134.66    71.9 1138.02   147.8 1132.77
   271.6 1132.64   291.6 1131.57   351.5  1124.7   367.5 1121.64   383.5  1117.8
   419.4 1105.15   439.4 1099.94   455.4 1099.17   519.3 1099.91   575.2 1099.16
   647.1 1100.08   675.1 1099.34     691 1100.32   906.7 1099.28   934.7 1099.53
   942.7 1100.41   990.6 1112.87  1030.6 1119.62  1070.5 1122.84  1098.5 1123.83
 1233.961134.827  1254.2    1135  1262.2 1137.03 1277.771138.029  1382.1 1148.43
#Mann= 5 ,-1 , 0
       0     .12       0   439.4    .045       0   942.7     .12       0
 1233.96    .016       0 1277.77     .12       0
Bank Sta=439.4,942.7
XS Rating Curve= 0 ,0
Exp/Cntr=0.3,0.1

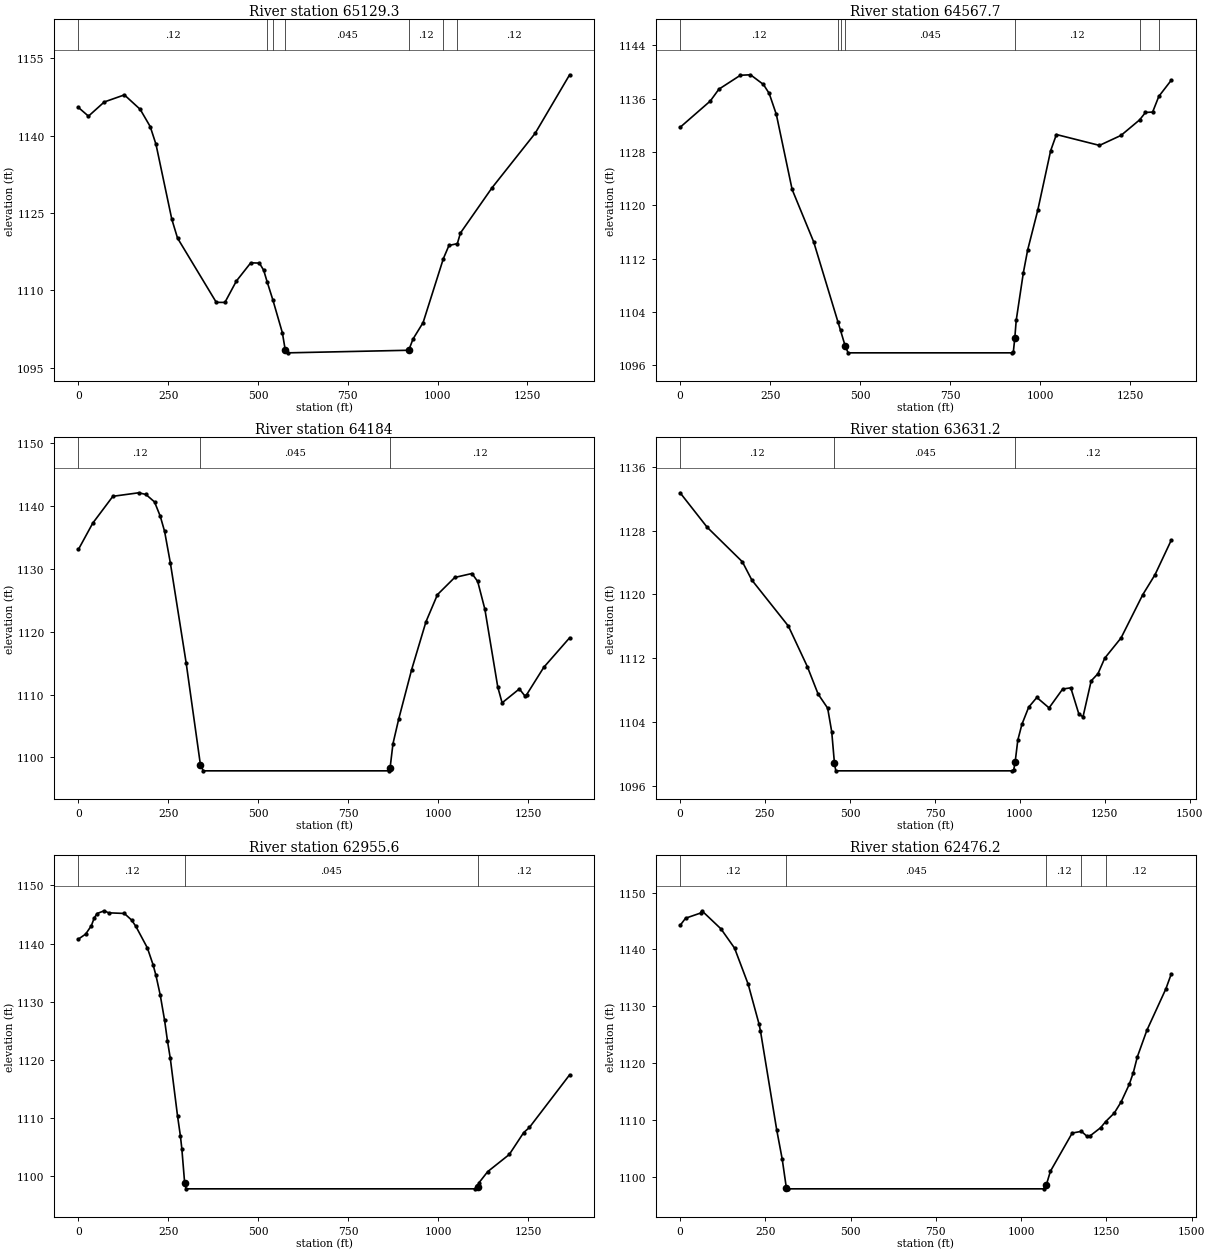
Type RM Length L Ch R = 1 ,65129.3 ,559.6,561.6,563.6
XS GIS Cut Line= 2
     2344832.113      367870.901     2346101.925      367362.647
#Sta/Elev= 30
       0 1145.44      28 1143.76      72 1146.51     128 1147.88     172 1145.08
     200 1141.73     216  1138.3     260  1123.8     276 1120.12   383.9 1107.67
   407.9 1107.65   439.9  1111.8   479.9 1115.33   503.9 1115.28   515.9 1113.89
  525.451111.667  541.411108.149   567.9 1101.78   575.9 1098.46   583.9 1097.88
   919.8 1098.38   931.8 1100.57   959.8 1103.74 1016.331116.159  1031.8 1118.69
 1055.15 1119.05  1063.8 1121.11  1151.8 1129.88  1271.8 1140.43  1367.8 1151.78
#Mann= 7 ,-1 , 0
       0     .12       0  525.45     .06       0  541.41     .12       0
   575.9    .045       0   919.8     .12       0 1016.33    .016       0
 1055.15     .12       0
Bank Sta=575.9,919.8
XS Rating Curve= 0 ,0
Exp/Cntr=0.3,0.1

Type RM Length L Ch R = 1 ,64567.7 ,383.3,383.7,384.1
XS GIS Cut Line= 3
     2344996.608      368332.479     2345650.949      368138.459
     2346305.291       367944.44
#Sta/Elev= 30
       0  1131.7    83.8 1135.64   107.8 1137.42   167.6 1139.51   195.6 1139.58
   231.5 1138.13   247.5 1136.79   267.4 1133.64   311.3 1122.38   371.2 1114.52
  438.761102.496  445.891101.238     459 1098.85     467 1097.88     922 1097.88
     926    1098     930 1100.05     934 1102.75   953.9 1109.91   965.9 1113.32
   993.8 1119.24  1029.7 1128.19  1045.7 1130.62  1165.4 1128.99  1225.3 1130.49
  1276.91132.815  1293.2 1133.93  1313.1 1133.99  1330.31136.342    1365 1138.77
#Mann= 7 ,-1 , 0
       0     .12       0  438.76     .06       0  445.89     .12       0
     459    .045       0     930     .12       0  1276.9    .016       0
  1330.3     .12       0
Bank Sta=459,930
XS Rating Curve= 0 ,0
Exp/Cntr=0.3,0.1

Type RM Length L Ch R = 1 ,64184   ,558.4,552.8,547.3
XS GIS Cut Line= 3
     2345139.775      368676.733       2345797.7      368495.237
     2346455.625       368313.74
#Sta/Elev= 30
       0 1133.04    39.9 1137.22    95.8 1141.48   167.6 1142.04   187.6 1141.77
   211.5 1140.59   227.5 1138.31   239.5 1135.91   255.4 1130.93   299.3 1115.06
   339.2 1098.78   347.2 1097.88   862.1 1097.88   866.1 1098.32   874.1 1102.18
     890 1106.09     926 1113.95   965.9 1121.57   997.8 1125.87  1045.7 1128.59
  1093.6 1129.22  1109.6 1127.95  1129.5 1123.55  1165.4 1111.18  1177.4 1108.68
  1225.3 1110.89  1241.3 1109.74  1245.3 1109.95  1293.2 1114.32    1365 1119.01
#Mann= 3 ,-1 , 0
       0     .12       0   339.2    .045       0   866.1     .12       0
Bank Sta=339.2,866.1
XS Rating Curve= 0 ,0
Exp/Cntr=0.3,0.1

Type RM Length L Ch R = 1 ,63631.2 ,676.6,675.6,674.6
XS GIS Cut Line= 3
     2345772.893      369576.539     2345699.976      369172.893
     2346600.776       368662.47
#Sta/Elev= 30
       0 1132.74    79.6 1128.42   183.2 1124.09   211.1  1121.8   318.6 1116.03
   374.3 1110.96   406.2  1107.5   434.2 1105.74   446.2 1102.78   454.2 1098.83
   458.2 1097.88   977.8 1097.88   981.8 1098.02   985.8 1098.93   993.8 1101.73
  1005.8  1103.7  1025.8 1105.86  1049.8 1107.08  1085.8 1105.77  1125.7 1108.13
  1149.7 1108.29  1173.7 1104.97  1185.7 1104.66  1209.7 1109.16  1229.7 1110.06
  1249.7 1112.01  1297.6 1114.54  1361.6 1119.97  1397.6 1122.47  1445.5 1126.81
#Mann= 3 ,-1 , 0
       0     .12       0   454.2    .045       0   985.8     .12       0
Bank Sta=454.2,985.8
XS Rating Curve= 0 ,0
Exp/Cntr=0.3,0.1

Type RM Length L Ch R = 1 ,62955.6 ,480.8,479.4,478
XS GIS Cut Line= 3
     2345799.406      369925.048     2346377.104      369561.724
     2346964.263      369213.258
#Sta/Elev= 30
       0 1140.78      20 1141.63    35.9 1143.07    43.9 1144.39    51.9 1145.17
    71.8 1145.64    83.8 1145.29   127.7 1145.18   147.7 1144.05   159.6 1142.97
   191.6 1139.27   207.5 1136.37   215.5 1134.54   227.5 1131.14   239.5 1126.83
   247.4 1123.33   255.4 1120.28   275.4 1110.44   283.4 1106.99   287.4  1104.8
   295.3 1098.86   299.3 1097.88  1101.7 1097.88  1109.7 1098.25  1113.7 1098.96
  1137.6 1100.84  1197.5 1103.78  1237.5 1107.54  1253.4 1108.42  1365.2 1117.46
#Mann= 3 ,-1 , 0
       0     .12       0   295.3    .045       0  1109.7     .12       0
Bank Sta=295.3,1109.7
XS Rating Curve= 0 ,0
Exp/Cntr=0.3,0.1

Type RM Length L Ch R = 1 ,62476.2 ,523.5,523.4,523.2
XS GIS Cut Line= 3
     2346075.716       370365.66     2347048.934      369667.685
     2347285.913      369719.768
#Sta/Elev= 30
       0 1144.22      16 1145.48    59.9 1146.39    63.9 1146.79   119.8 1143.61
   159.7 1140.22   199.6 1133.87   231.5 1126.86   235.5  1125.7   283.4 1108.21
   299.4 1103.11   311.4 1098.11   315.4 1097.88  1065.9 1097.88  1073.9 1098.59
  1085.8 1100.97  1149.7 1107.69 1176.781107.995  1193.6 1107.09  1201.6 1107.17
  1233.4 1108.65 1247.891109.716  1273.2 1111.22  1293.1 1113.16    1317 1116.26
  1328.9 1118.32  1340.8 1121.11  1368.7 1125.77  1424.4 1133.06  1440.3  1135.7
#Mann= 5 ,-1 , 0
       0     .12       0   311.4    .045       0  1073.9     .12       0
 1176.78     .06       0 1247.89     .12       0
Bank Sta=311.4,1073.9
XS Rating Curve= 0 ,0
Exp/Cntr=0.3,0.1

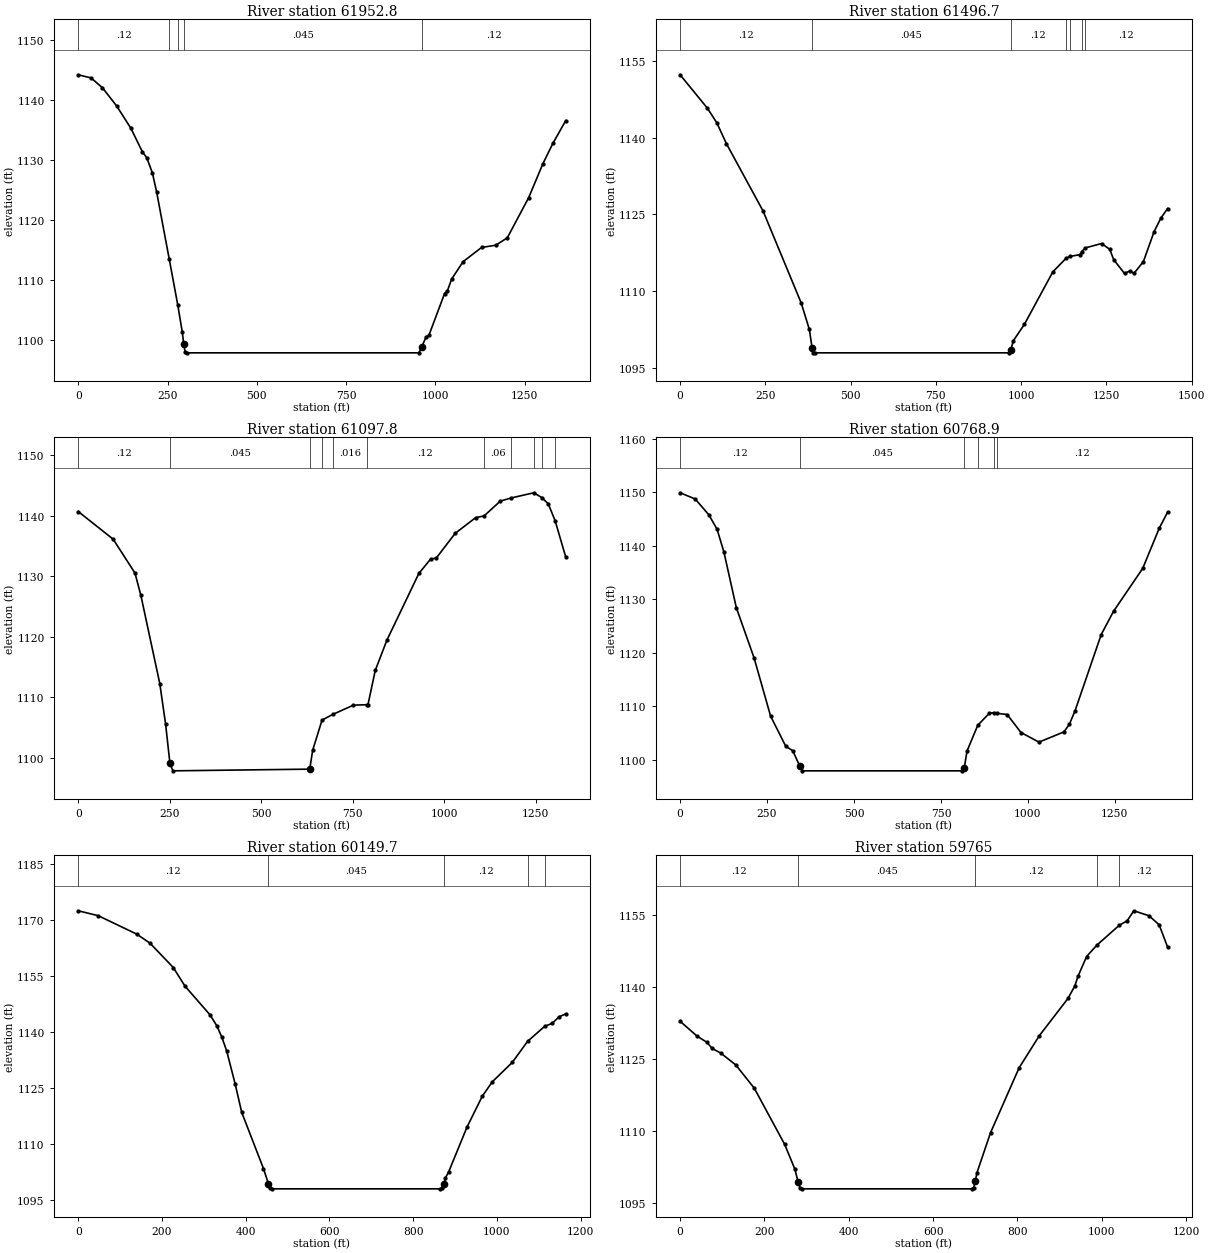
Type RM Length L Ch R = 1 ,61952.8 ,453.8,456.1,458.5
XS GIS Cut Line= 3
      2346396.58       370782.45     2346948.261      370380.637
     2347499.943      369978.823
#Sta/Elev= 30
       0  1144.2    35.9 1143.68    67.8 1142.04   107.8 1138.99   147.7 1135.26
   179.6 1131.36   191.6 1130.42   207.5 1127.89   219.5 1124.69  254.911113.472
  278.561105.901   291.4 1101.34   295.4 1099.29   299.3 1098.05   303.3 1097.88
   953.9 1097.88   961.9 1098.86   973.9 1100.53   981.8 1100.77  1025.8 1107.76
  1033.7 1108.21  1045.7 1110.18  1077.6 1113.06  1129.5 1115.44  1169.4 1115.81
  1201.4 1117.04  1261.2 1123.72  1301.1 1129.38  1329.1 1132.77    1365 1136.56
#Mann= 5 ,-1 , 0
       0     .12       0  254.91     .06       0  278.56     .12       0
   295.4    .045       0   961.9     .12       0
Bank Sta=295.4,961.9
XS Rating Curve= 0 ,0
Exp/Cntr=0.3,0.1

Type RM Length L Ch R = 1 ,61496.7 ,387.2,398.9,410.7
XS GIS Cut Line= 3
     2346563.551      371137.383      2347577.58      370547.893
     2347788.518      370693.727
#Sta/Elev= 30
       0 1152.28    79.8 1145.76   107.7 1142.88   135.6 1138.83   243.4 1125.61
   355.1 1107.63     379 1102.46     387 1098.81     391  1097.9     395 1097.88
   965.5 1097.88   969.5 1098.45   977.4 1100.28  1009.4 1103.44  1093.1 1113.74
  1131.81116.383 1142.041116.733  1172.9 1117.09 1177.371117.666  1187.91118.407
    1236 1119.27  1259.7 1118.13  1271.6 1116.09  1303.1 1113.41  1318.9 1113.92
  1330.7 1113.41  1358.4 1115.72  1389.9  1121.6  1409.6 1124.22  1429.4 1126.11
#Mann= 7 ,-1 , 0
       0     .12       0     387    .045       0   969.5     .12       0
  1131.8     .06       0 1142.04     .12       0 1177.37    .016       0
  1187.9     .12       0
Bank Sta=387,969.5
XS Rating Curve= 0 ,0
Exp/Cntr=0.3,0.1

Type RM Length L Ch R = 1 ,61097.8 ,325.3,328.9,332.5
XS GIS Cut Line= 3
     2346767.684      371178.102     2347543.726      371170.289
     2348060.204      370963.421
#Sta/Elev= 30
       0 1140.72    95.5 1136.15   155.2 1130.54   171.1 1126.89   222.9  1112.3
   238.8  1105.6   250.7  1099.1   258.7 1097.88   632.8 1098.16   640.8 1101.28
  666.331106.261  695.851107.206   752.2 1108.73  788.331108.802     792 1108.83
   811.8 1114.46   843.6 1119.46   931.1  1130.5   962.9 1132.84   978.8 1133.05
  1030.4 1137.12  1086.1  1139.7 1109.351139.995  1153.6 1142.44 1183.37 1142.96
 1245.121143.816 1267.351143.013  1284.8 1141.98 1303.57 1139.18  1332.4 1133.22
#Mann= 11 ,-1 , 0
       0     .12       0   250.7    .045       0   632.8     .12       0
  666.33     .08       0  695.85    .016       0  788.33     .12       0
 1109.35     .06       0 1183.37    .016       0 1245.12     .12       0
 1267.35     .06       0 1303.57     .12       0
Bank Sta=250.7,632.8
XS Rating Curve= 0 ,0
Exp/Cntr=0.3,0.1

Type RM Length L Ch R = 1 ,60768.9 ,629.5,619.2,609
XS GIS Cut Line= 4
     2346655.705      371251.018     2346815.344      371441.149
     2347468.205      371540.081     2347804.128      371900.921
#Sta/Elev= 30
       0  1149.9    43.4 1148.74    82.8 1145.76   106.4 1143.06   126.1 1138.78
   161.6 1128.41   212.8 1118.98   260.2 1108.12     304 1102.45   323.8 1101.65
   343.7 1098.83   351.7 1097.88   809.1 1097.88   817.1  1098.5     825 1101.59
  855.731106.397   888.7 1108.62  901.781108.773  910.711108.652   940.4 1108.41
   980.1 1105.05  1031.8 1103.25  1103.4 1105.16  1119.3  1106.6  1135.2 1109.05
  1210.7 1123.37  1246.5 1127.76    1330 1135.74  1377.7 1143.28  1401.6 1146.27
#Mann= 6 ,-1 , 0
       0     .12       0   343.7    .045       0   817.1     .12       0
  855.73    .016       0  901.78     .06       0  910.71     .12       0
Bank Sta=343.7,817.1
XS Rating Curve= 0 ,0
Exp/Cntr=0.3,0.1

Type RM Length L Ch R = 1 ,60149.7 ,387.5,384.7,381.8
XS GIS Cut Line= 3
     2346637.476      372251.018     2346960.393      372201.539
     2347759.872      371951.539
#Sta/Elev= 30
       0 1172.56    47.8 1171.24   139.4 1166.31   171.3 1163.87   227.1 1157.31
     255 1152.32   314.7 1144.62   330.7 1141.72   342.6 1138.74   354.6  1134.9
   374.6 1126.15   390.5 1118.41   442.4 1103.34   454.3 1099.24   458.3 1098.09
   462.3 1097.88   865.2 1097.88   869.2 1098.08   873.2 1099.29   877.1  1100.8
   885.1 1102.53     929 1114.58   964.9 1122.72   988.8 1126.61  1036.7 1131.84
 1073.061137.466 1113.731141.498  1132.4 1142.36  1148.4 1144.08  1164.3 1144.87
#Mann= 5 ,-1 , 0
       0     .12       0   454.3    .045       0   873.2     .12       0
 1073.06    .016       0 1113.73     .12       0
Bank Sta=454.3,873.2
XS Rating Curve= 0 ,0
Exp/Cntr=0.3,0.1

Type RM Length L Ch R = 1 ,59765   ,532.7,533.2,533.6
XS GIS Cut Line= 2
      2346983.83      372657.268      2348035.31      372177.124
#Sta/Elev= 30
       0 1132.82      40 1129.74      64  1128.4      76 1127.15      96 1126.21
     132 1123.72     176 1118.85     248 1107.14     272 1102.01     280 1099.24
     284 1098.13     288 1097.88     692 1097.88     696 1098.07     700 1099.52
     704 1101.27     736 1109.57   803.9 1123.13   851.9 1129.83   919.9  1137.6
   935.9 1140.19   943.9  1142.3   963.9 1146.32   987.4 1148.63  1041.51152.846
  1059.9 1153.76  1075.9 1155.86  1111.9 1154.82  1135.9 1152.94  1155.9 1148.29
#Mann= 5 ,-1 , 0
       0     .12       0     280    .045       0     700     .12       0
   987.4    .016       0  1041.5     .12       0
Bank Sta=280,700
XS Rating Curve= 0 ,0
Exp/Cntr=0.3,0.1