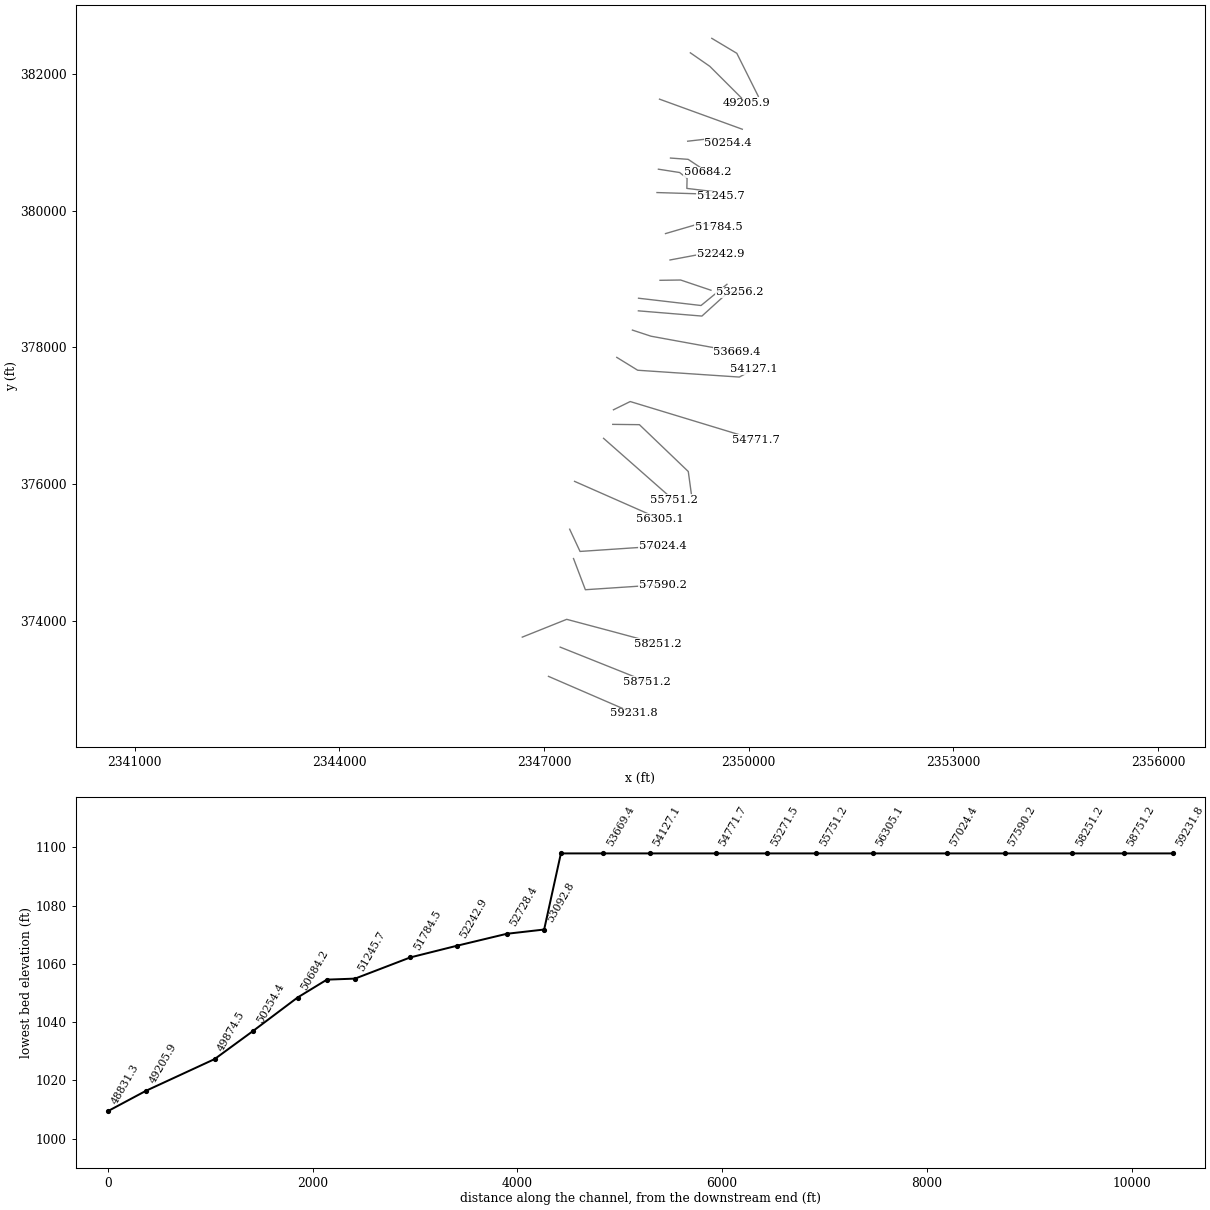
HEC-RAS study MEADOWBRCH.prj: MEADOWBRCH

--- MEADOWBRCH.g01 (geometry) --- (continued)

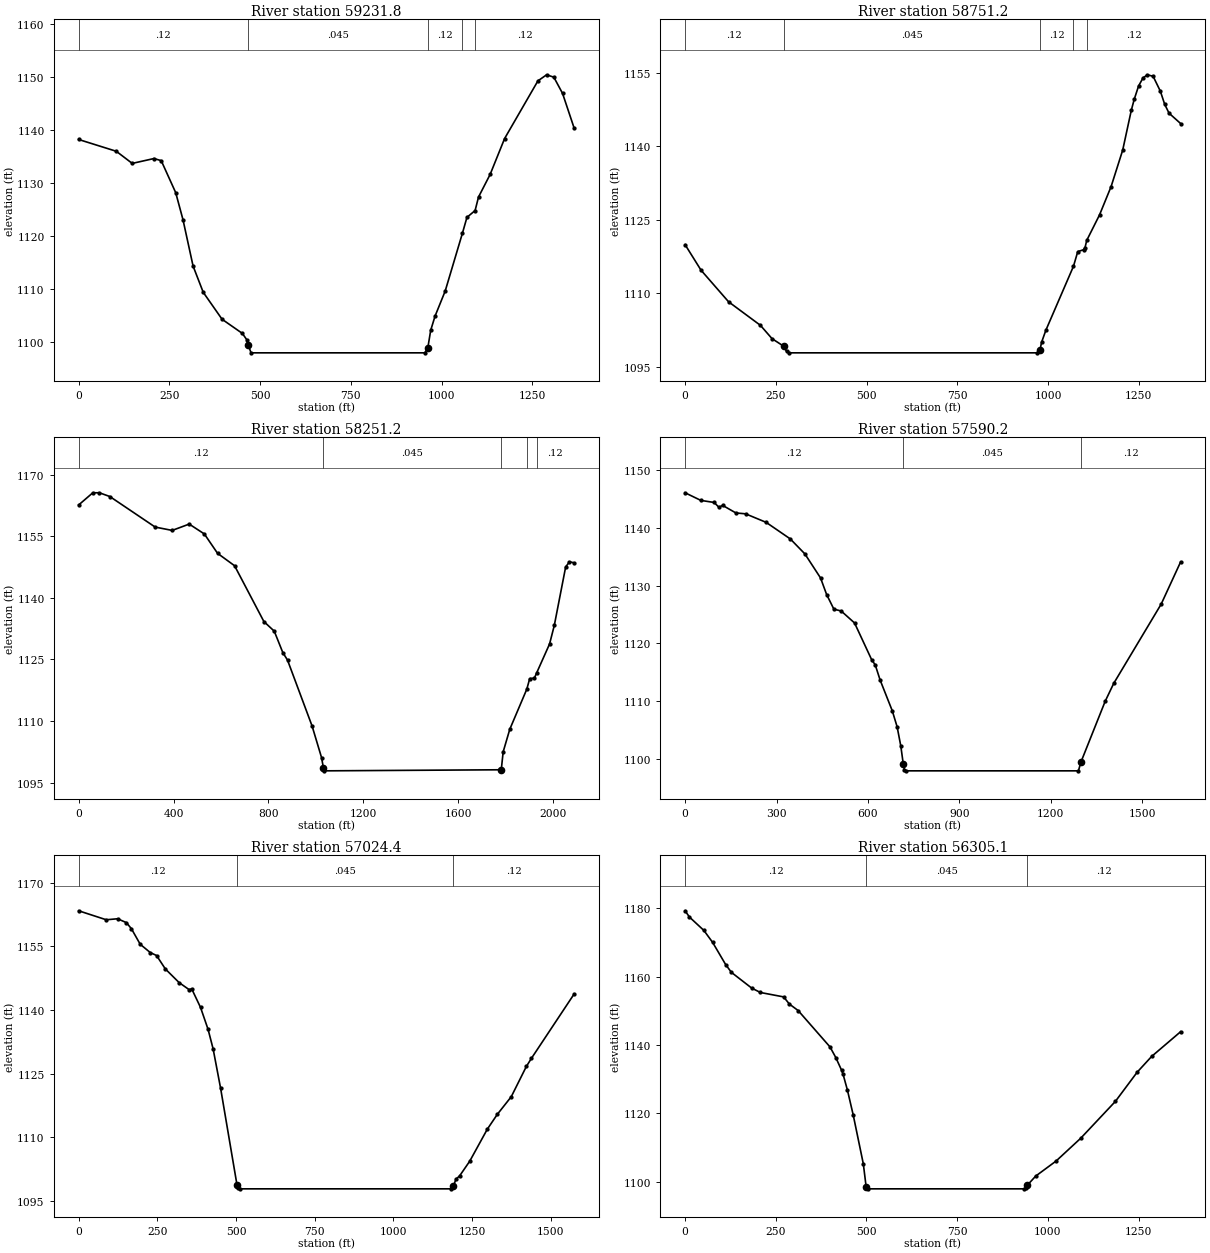
Type RM Length L Ch R = 1 ,59231.8 ,480,480.6,481.3
XS GIS Cut Line= 2
     2347065.856      373183.073     2348319.347      372641.331
#Sta/Elev= 30
       0 1138.18   103.8 1135.95   147.7 1133.66   207.6 1134.58   227.6 1134.18
   267.5 1128.14   287.5 1123.05   315.4 1114.27   343.4 1109.31   395.3 1104.22
   451.2 1101.55   463.2 1100.37   467.2 1099.38   475.2 1097.88   954.3 1097.88
   962.3 1098.83   970.3 1102.16   982.2 1104.81  1010.2 1109.56 1057.841120.519
  1070.1 1123.47 1092.581124.756    1102 1127.31    1134 1131.58  1173.9 1138.36
  1265.7 1149.25  1289.7  1150.4  1309.6 1149.94  1333.6 1146.88  1365.6 1140.31
#Mann= 5 ,-1 , 0
       0     .12       0   467.2    .045       0   962.3     .12       0
 1057.84    .016       0 1092.58     .12       0
Bank Sta=467.2,962.3
XS Rating Curve= 0 ,0
Exp/Cntr=0.3,0.1

Type RM Length L Ch R = 1 ,58751.2 ,497.3,500,502.6
XS GIS Cut Line= 3
     2347236.976       373611.41       2347870.9      373358.534
     2348504.823      373105.657
#Sta/Elev= 30
       0 1119.95    43.9 1114.74   119.7  1108.3   207.5 1103.49   239.5 1100.77
   271.4 1099.24   279.4 1098.18   287.4 1097.88   969.9 1097.88   977.8 1098.53
   981.8    1100   993.8  1102.5 1069.831115.545  1081.6 1118.53  1097.6 1118.92
  1101.6 1119.34 1106.351120.823  1141.5 1126.01  1173.4 1131.79  1205.4 1139.24
  1229.3 1147.43  1237.3 1149.64  1249.2 1152.33  1261.2 1153.95  1273.2 1154.61
  1289.2  1154.3  1309.1 1151.27  1321.1 1148.58  1333.1 1146.77    1365 1144.66
#Mann= 5 ,-1 , 0
       0     .12       0   271.4    .045       0   977.8     .12       0
 1069.83    .016       0 1106.35     .12       0
Bank Sta=271.4,977.8
XS Rating Curve= 0 ,0
Exp/Cntr=0.3,0.1

Type RM Length L Ch R = 1 ,58251.2 ,653.7,661,668.5
XS GIS Cut Line= 4
     2346681.844      373757.695     2347332.886      374018.112
      2348014.42      373836.853      2348673.33      373658.966
#Sta/Elev= 30
       0 1162.59    59.8 1165.56    87.6 1165.56   131.5 1164.65   322.7 1157.21
   394.4  1156.4   466.1 1157.94   529.9 1155.54   585.7 1150.82   657.4  1147.8
   780.9 1134.22   824.7 1131.87   860.6 1126.68   880.5 1124.84   984.1 1108.79
  1023.9 1101.12  1031.9  1098.6  1035.9 1097.88  1781.6 1098.14  1789.6 1102.51
  1817.5    1108 1889.261117.766  1901.3  1120.3  1921.3 1120.46 1930.92 1121.74
  1985.2 1128.76  2005.1 1133.27    2053  1147.5    2069 1148.76  2088.9 1148.51
#Mann= 5 ,-1 , 0
       0     .12       0  1031.9    .045       0  1781.6     .12       0
 1889.26    .016       0 1930.92     .12       0
Bank Sta=1031.9,1781.6
XS Rating Curve= 0 ,0
Exp/Cntr=0.3,0.1

Type RM Length L Ch R = 1 ,57590.2 ,565.7,565.7,565.7
XS GIS Cut Line= 3
     2347432.712      374907.869     2347606.226      374451.539
     2348741.643       374527.06
#Sta/Elev= 30
       0 1146.12    51.6  1144.8    95.3 1144.44   111.1  1143.6     123 1143.94
   166.7 1142.62   198.5 1142.47   265.9 1140.99   345.3 1138.11     393 1135.52
   444.5 1131.34   464.4 1128.47   488.2 1125.93   512.2 1125.61   556.1 1123.53
     612 1117.18     624 1116.25   639.9 1113.64   679.9 1108.29   695.8 1105.51
   707.8  1102.2   715.8 1099.12   719.8 1097.98   723.8 1097.88  1290.7 1097.88
  1298.7 1099.37  1378.6 1109.96  1406.5 1113.05  1562.2  1126.8  1626.1 1134.13
#Mann= 3 ,-1 , 0
       0     .12       0   715.8    .045       0  1298.7     .12       0
Bank Sta=715.8,1298.7
XS Rating Curve= 0 ,0
Exp/Cntr=0.3,0.1

Type RM Length L Ch R = 1 ,57024.4 ,730.3,719.3,708.4
XS GIS Cut Line= 3
     2347376.289      375337.556     2347528.199      375012.035
     2348740.207      375093.567
#Sta/Elev= 30
       0 1163.39    87.8 1161.27   123.7 1161.51   151.7  1160.6   167.6 1159.17
   195.6  1155.5   227.5 1153.55   247.5 1152.85   275.4 1149.69   319.3 1146.46
   351.2  1144.8   359.2 1144.99   387.2 1140.62   411.2 1135.44   427.2 1130.85
   451.1 1121.52   503.1 1098.77   507.1 1097.96   511.1 1097.88  1182.4 1097.88
  1190.4 1098.53  1198.4 1100.14  1210.3 1100.95  1242.3  1104.4  1298.2 1111.95
  1330.2 1115.46  1374.2 1119.59  1422.1 1126.71  1438.1 1128.61    1574  1143.8
#Mann= 3 ,-1 , 0
       0     .12       0   503.1    .045       0  1190.4     .12       0
Bank Sta=503.1,1190.4
XS Rating Curve= 0 ,0
Exp/Cntr=0.3,0.1

Type RM Length L Ch R = 1 ,56305.1 ,560.8,553.9,547
XS GIS Cut Line= 2
     2347448.021      376038.083     2348698.237      375487.533
#Sta/Elev= 30
       0 1179.31      12 1177.47    51.9 1173.54    75.9 1170.05   111.8 1163.56
   127.8 1161.26   183.7 1156.66   207.7 1155.38   271.6 1154.09   287.6 1151.98
   311.6  1150.1   399.4 1139.45   415.4 1136.34   431.4 1132.61   435.4 1131.48
   447.4 1126.83   463.4 1119.54   491.3 1105.21   499.3  1098.3   503.3 1097.88
   934.7 1097.88   938.7 1098.06   942.7 1098.86   966.6 1101.62  1022.6 1106.01
  1090.5 1112.68  1186.3  1123.5  1246.2 1132.03  1286.2 1136.66  1366.1  1143.9
#Mann= 3 ,-1 , 0
       0     .12       0   499.3    .045       0   942.7     .12       0
Bank Sta=499.3,942.7
XS Rating Curve= 0 ,0
Exp/Cntr=0.3,0.1

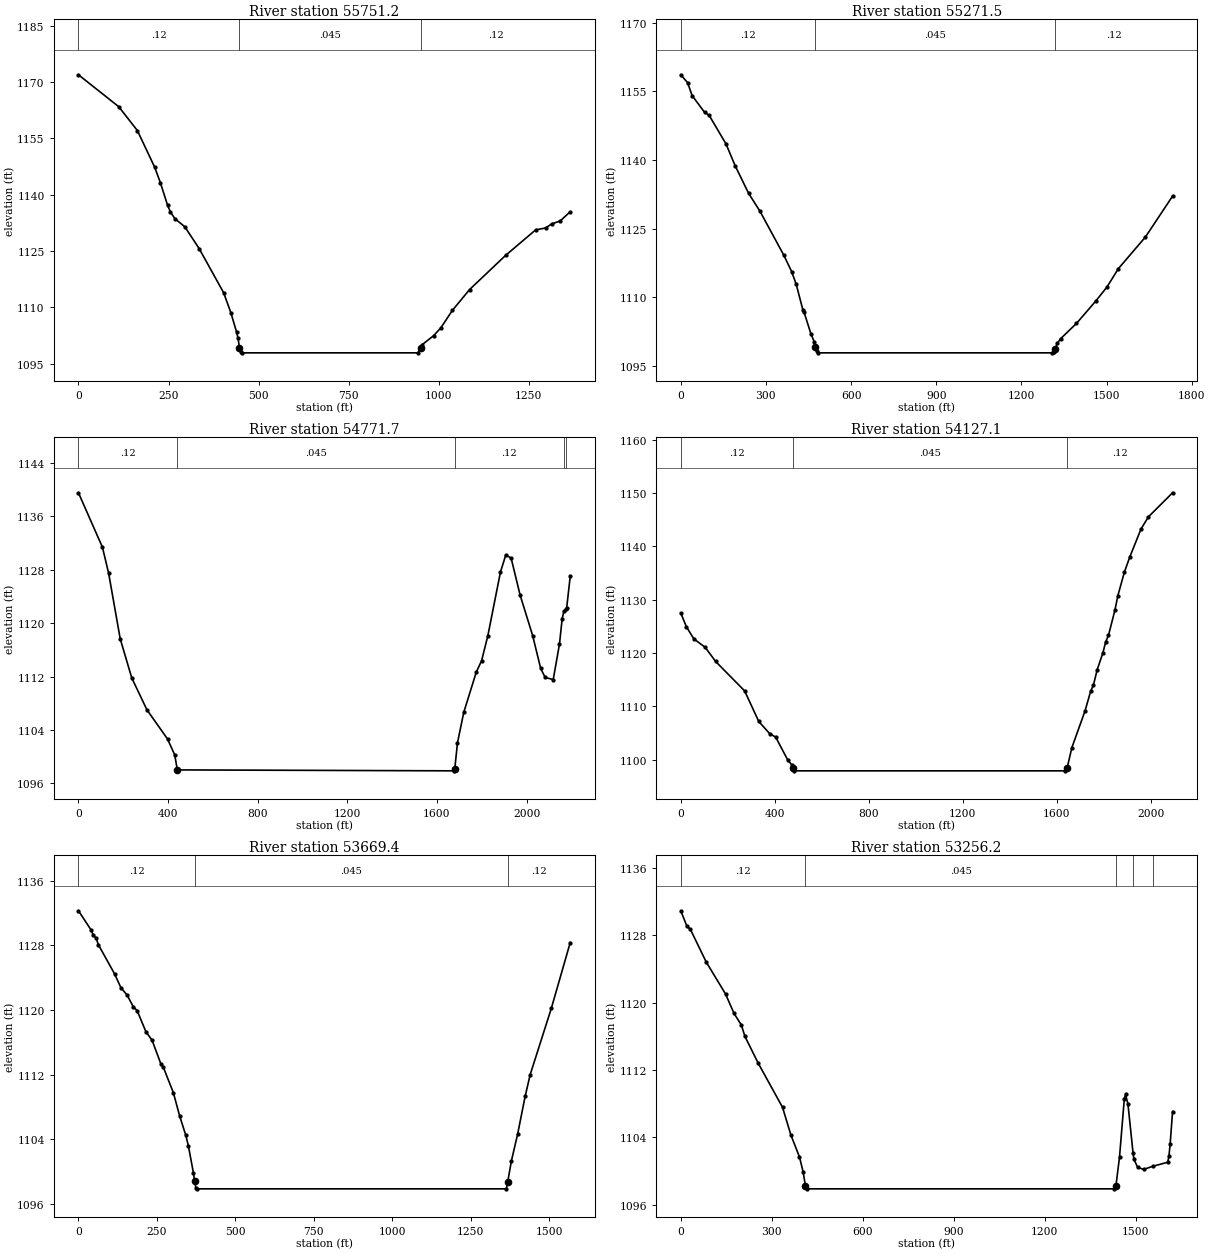
Type RM Length L Ch R = 1 ,55751.2 ,480.7,479.7,478.8
XS GIS Cut Line= 3
      2347872.95      376667.913     2348385.252      376216.965
     2348897.553      375766.017
#Sta/Elev= 30
       0 1171.89   111.8  1163.4   163.6 1157.04   211.5 1147.31   227.5 1143.15
   247.5 1137.12   255.4 1135.38   267.4 1133.62   295.4 1131.42   335.3 1125.59
   403.1 1113.86   423.1 1108.56     439 1103.38     443 1101.76     447 1099.18
     451 1097.98     455 1097.88   941.9 1097.88   949.9 1099.16   953.9 1100.04
   985.8 1102.44  1005.8 1104.53  1037.7 1109.15  1085.6 1114.72  1185.4  1123.8
  1269.2 1130.62  1297.2 1131.12  1313.1 1132.19  1337.1 1132.97    1365 1135.45
#Mann= 3 ,-1 , 0
       0     .12       0     447    .045       0   949.9     .12       0
Bank Sta=447,949.9
XS Rating Curve= 0 ,0
Exp/Cntr=0.3,0.1

Type RM Length L Ch R = 1 ,55271.5 ,489.1,499.8,510.4
XS GIS Cut Line= 4
     2348007.485      376872.329      2348398.11      376867.989
     2349114.255      376182.225     2349161.998      375835.003
#Sta/Elev= 30
       0 1158.59    23.9 1156.88    39.9 1154.06    83.7  1150.4    99.7 1149.76
   159.4 1143.49   191.3 1138.77   239.2 1132.68     279  1128.8   362.8 1119.22
   390.6 1115.63   406.6 1112.86   430.6 1107.18   434.6 1106.71   458.6 1102.02
   470.6 1100.26   474.6 1099.12   478.6 1098.18   482.6 1097.88  1306.2 1097.88
  1314.2 1098.06  1318.2 1098.62  1326.2 1099.92  1338.2 1100.96  1394.1  1104.3
  1461.8 1109.16  1501.7 1112.26  1541.5 1116.24  1637.1 1123.17  1732.7 1132.09
#Mann= 3 ,-1 , 0
       0     .12       0   474.6    .045       0  1318.2     .12       0
Bank Sta=474.6,1318.2
XS Rating Curve= 0 ,0
Exp/Cntr=0.3,0.1

Type RM Length L Ch R = 1 ,54771.7 ,639.4,644.6,649.8
XS GIS Cut Line= 3
     2348017.901      377085.871     2348263.561       377206.53
     2350101.983       376648.32
#Sta/Elev= 30
       0 1139.55   107.1 1131.39   134.9 1127.47   186.4 1117.67     238  1111.8
   305.6 1107.03   397.5 1102.66   429.5 1100.29   441.5 1098.02  1675.7 1097.88
  1679.7 1098.17  1691.7 1102.06  1719.7 1106.63  1775.6 1112.66  1799.6  1114.4
  1827.5 1118.16  1883.4 1127.64  1907.4 1130.24  1931.4 1129.74  1971.3 1124.22
  2027.2 1118.16  2063.2 1113.22  2083.2 1111.87  2119.1 1111.56  2147.1 1116.89
    2159 1120.67 2166.791121.795 2176.45 1122.12    2179 1122.26    2195 1127.02
#Mann= 5 ,-1 , 0
       0     .12       0   441.5    .045       0  1679.7     .12       0
 2166.79    .016       0 2176.45     .12       0
Bank Sta=441.5,1679.7
XS Rating Curve= 0 ,0
Exp/Cntr=0.3,0.1

Type RM Length L Ch R = 1 ,54127.1 ,460.4,457.7,455.1
XS GIS Cut Line= 4
     2348066.512      377853.232     2348372.936      377664.864
     2349861.651      377565.037     2350074.325      377677.885
#Sta/Elev= 30
       0 1127.48      24 1124.89      56 1122.61   103.9 1121.05   147.9 1118.41
   271.8 1112.87   331.7 1107.15   379.6 1104.79   403.6 1104.23   455.4 1099.89
   471.4 1099.06   475.4 1098.41   483.4 1097.88  1636.3 1097.88  1644.3  1098.5
  1664.2 1102.25  1720.1 1109.12    1744 1112.81    1756 1113.99    1772 1116.88
  1795.9 1119.97  1807.9 1122.07  1819.8 1123.27  1847.8 1128.12  1859.6  1130.7
  1887.3 1135.12    1911 1138.05  1958.3 1143.24  1989.9 1145.52  2092.5 1150.03
#Mann= 3 ,-1 , 0
       0     .12       0   475.4    .045       0  1644.3     .12       0
Bank Sta=475.4,1644.3
XS Rating Curve= 0 ,0
Exp/Cntr=0.3,0.1

Type RM Length L Ch R = 1 ,53669.4 ,410.9,413.2,415.4
XS GIS Cut Line= 3
     2348295.679      378252.537     2348567.953       378163.13
     2349828.318      377933.324
#Sta/Elev= 30
       0 1132.27    39.8 1129.93    47.8 1129.22    55.7 1128.94    63.7 1128.06
   115.4 1124.45   135.3 1122.76   155.2 1121.84   175.1 1120.38   187.1 1119.92
   214.9 1117.33   234.8 1116.25   262.7 1113.34   270.7 1112.91   302.5 1109.78
   322.5 1106.91   342.4 1104.48   350.4  1103.2   366.4 1099.88   370.4 1098.79
   374.4 1098.03   378.4 1097.88  1364.2 1097.88  1368.2  1098.7  1380.1 1101.32
  1400.1 1104.66    1424 1109.32    1440    1112  1507.9 1120.26  1567.7 1128.34
#Mann= 3 ,-1 , 0
       0     .12       0   370.4    .045       0  1368.2     .12       0
Bank Sta=370.4,1368.2
XS Rating Curve= 0 ,0
Exp/Cntr=0.3,0.1

Type RM Length L Ch R = 1 ,53256.2 ,164.1,163.5,162.8
XS GIS Cut Line= 4
     2348383.005      378534.453     2349314.127       378457.94
      2349702.45       378810.06      2349865.21       378803.55
#Sta/Elev= 30
       0 1130.91      20  1129.1    31.9 1128.69    83.8 1124.83   147.7 1121.02
   175.7 1118.71   199.6 1117.35   211.6 1115.98   255.5 1112.79   335.4 1107.57
   363.3 1104.25   391.3 1101.67   403.2 1099.93   411.2  1098.2   415.2 1097.88
  1426.7 1097.88 1434.71 1098.24  1446.5 1101.65  1462.4  1108.6  1466.4 1109.09
  1474.4 1107.92  1491.2 1102.13  1494.2 1101.38  1506.1 1100.45    1526 1100.18
 1555.33 1100.55  1605.5 1101.04  1609.4 1101.76  1613.4 1103.17  1621.4 1107.06
#Mann= 5 ,-1 , 0
       0     .12       0   411.2    .045       0 1434.71     .06       0
  1491.2     .08       0 1555.33     .06       0
Bank Sta=411.2,1434.71
XS Rating Curve= 0 ,0
Exp/Cntr=0.3,0.1

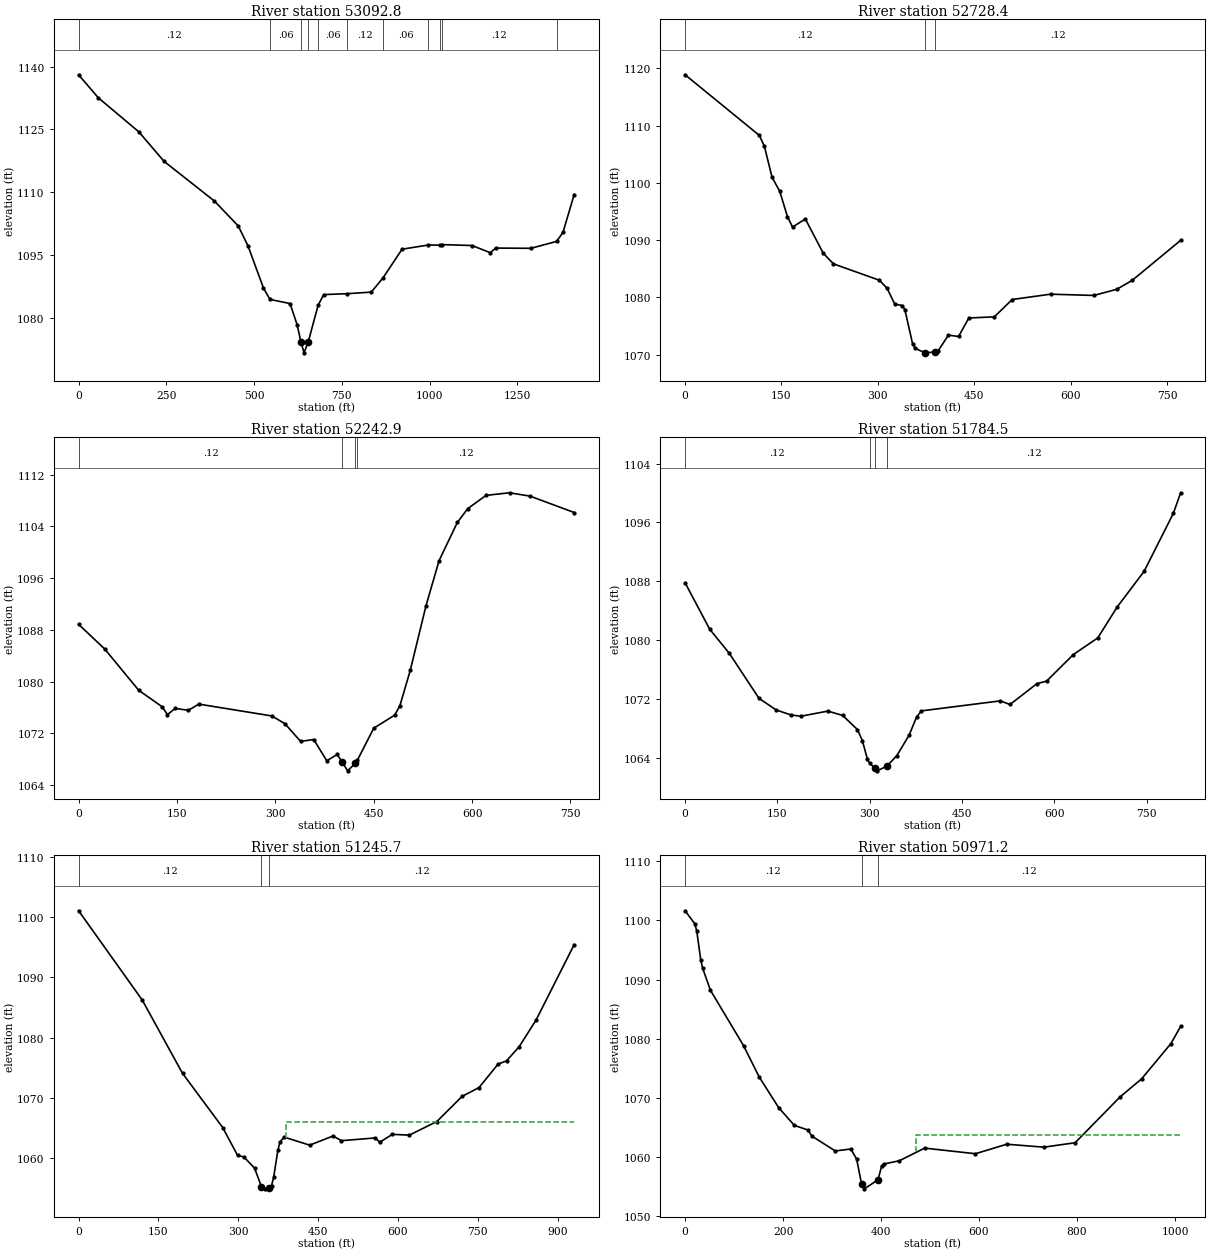
Type RM Length L Ch R = 1 ,53092.8 ,368.4,364.3,359.5
XS GIS Cut Line= 3
     2348385.377      378719.113     2349300.974      378612.578
     2349680.748      378922.908
#Sta/Elev= 30
       0 1138.04    55.9 1132.57   171.6 1124.44   243.4 1117.41   387.1 1107.94
   454.9 1102.01   482.8 1097.23   526.7 1087.23  545.22  1084.5   602.5 1083.52
   622.5  1078.5   633.5 1074.39   642.4 1071.77   654.4 1074.39  682.471083.097
   698.3 1085.65  765.791085.871     834 1086.24   867.21089.609   921.8 1096.47
  996.921097.476 1030.681097.431 1034.491097.567  1121.1 1097.35    1173 1095.64
  1188.9 1096.74  1288.6 1096.68 1362.071098.322  1380.3 1100.48  1412.2  1109.5
#Mann= 11 ,-1 , 0
       0     .12       0  545.22     .06       0   633.5    .045       0
   654.4     .12       0  682.47     .06       0  765.79     .12       0
   867.2     .06       0  996.92     .12       0 1030.68     .06       0
 1034.49     .12       0 1362.07     .06       0
Bank Sta=633.5,654.4
XS Rating Curve= 0 ,0
Exp/Cntr=0.3,0.1

Type RM Length L Ch R = 1 ,52728.4 ,473,485.5,498.5
XS GIS Cut Line= 3
     2348699.846      378981.501     2349002.309      378985.842
     2349446.373      378836.102
#Sta/Elev= 30
       0  1118.9   115.4 1108.32   123.4 1106.41   135.3 1100.99   147.3 1098.53
   159.2 1094.13   167.2 1092.28   187.1 1093.71   214.9 1087.73   230.8 1085.86
   302.5 1082.99   314.4 1081.56   326.3 1078.82   338.2 1078.58   342.2 1077.76
   354.1 1071.83   358.1 1071.07   373.8 1070.31   388.8 1070.46   393.8 1070.66
   409.7  1073.4   425.6 1073.17   441.5  1076.4   481.2  1076.6     509 1079.63
   568.6 1080.56   636.1 1080.34   671.8 1081.42   695.7 1082.97   771.1 1089.97
#Mann= 3 ,-1 , 0
       0     .12       0   373.8    .045       0   388.8     .12       0
Bank Sta=373.8,388.8
XS Rating Curve= 0 ,0
Exp/Cntr=0.3,0.1

Type RM Length L Ch R = 1 ,52242.9 ,455.7,458.4,460.7
XS GIS Cut Line= 3
       2348846.6      379279.224     2349480.832      379397.816
     2349585.002      379360.961
#Sta/Elev= 30
       0 1088.85    39.8 1085.04    91.6 1078.67   127.4 1076.12   135.4 1074.91
   147.4 1075.87   167.3 1075.57   183.2 1076.53   294.7  1074.7   314.6  1073.5
   338.5 1070.77   358.5 1071.06   378.4 1067.78   394.3 1068.75   402.3 1067.53
   410.2 1066.22   422.2  1067.4   424.9 1067.83   450.1 1072.81   481.9 1074.82
   489.9 1076.27   505.8 1081.77   529.7 1091.71   549.6 1098.68   577.5 1104.59
   593.4 1106.73   621.3 1108.78   657.1 1109.18   688.6 1108.66   755.7 1106.13
#Mann= 4 ,-1 , 0
       0     .12       0   402.3    .045       0   422.2    .045       0
   424.9     .12       0
Bank Sta=402.3,422.2
XS Rating Curve= 0 ,0
Exp/Cntr=0.3,0.1

Type RM Length L Ch R = 1 ,51784.5 ,545.9,538.8,531.6
XS GIS Cut Line= 3
     2348780.738      379665.457     2349291.154      379814.762
     2349558.515      379759.207
#Sta/Elev= 30
       0 1087.78      40 1081.46      72 1078.16     120 1072.06     148 1070.47
   171.9  1069.8   187.9 1069.62   231.9 1070.32   255.9 1069.73   279.9 1067.81
   287.9 1066.31   295.9 1063.85   299.6 1063.22   307.9  1062.6   311.9 1062.19
   327.9 1062.84   343.9 1064.25   363.9 1067.05   375.9  1069.5   383.9 1070.35
   511.8 1071.71   527.8 1071.22   571.4 1074.05   587.2  1074.4   630.7 1078.02
   670.3 1080.28     702 1084.51   745.5 1089.33     793 1097.22   804.9 1100.03
#Mann= 4 ,-1 , 0
       0     .12       0   299.6    .045       0   307.9    .045       0
   327.9     .12       0
Bank Sta=307.9,327.9
XS Rating Curve= 0 ,0
Exp/Cntr=0.3,0.1

Type RM Length L Ch R = 1 ,51245.7 ,288.8,274.5,260.2
XS GIS Cut Line= 3
     2348655.738      380266.151     2349280.738      380247.054
     2349584.557      380212.332
#Sta/Elev= 30
       0 1101.01   119.5 1086.22   195.2 1074.07   270.8 1065.08   298.7 1060.46
   310.6 1060.22   330.6 1058.35   343.6 1055.28   350.5 1054.93   358.6 1055.07
   362.4 1055.44   366.4 1056.81   374.4 1061.35   378.4 1062.72   386.3  1063.5
   434.1 1062.17   477.9 1063.68   493.9 1062.91   557.6 1063.37   565.6 1062.64
   589.4 1063.96   621.3 1063.83     673 1066.08   720.6 1070.26   752.4 1071.72
   788.1  1075.6     804 1076.14   827.8 1078.49   859.6 1082.92   931.1  1095.4
#Mann= 3 ,-1 , 0
       0     .12       0   343.6    .045       0   358.6     .12       0
#XS Ineff= 2 , 0
                          388.92            1066
Permanent Ineff=
       F       F
Bank Sta=343.6,358.6
XS Rating Curve= 0 ,0
Exp/Cntr=0.3,0.1

Type RM Length L Ch R = 1 ,50971.2 ,284.7,287,289.3
XS GIS Cut Line= 5
     2348676.571      380608.165     2348987.335      380559.554
      2349096.71      380474.485     2349093.238      380326.915
     2349501.224      380278.304
#Sta/Elev= 30
       0 1101.63    19.9 1099.42    23.9 1098.18    31.8 1093.38    35.8 1091.92
    51.8 1088.17   119.4  1078.8   151.3  1073.5   191.1 1068.31     223 1065.32
   250.8 1064.53   258.8  1063.5   306.6 1060.99   338.3 1061.32   350.2 1059.61
   360.2 1055.43     366 1054.58   393.7 1056.11   401.6 1058.52   405.6 1058.78
   437.3 1059.33     489 1061.47   592.7 1060.52   656.6 1062.13   732.4 1061.63
   796.2 1062.38   887.9 1070.13   931.8 1073.18   991.6 1079.14  1011.6 1082.06
#Mann= 3 ,-1 , 0
       0     .12       0   360.2    .045       0   393.7     .12       0
#XS Ineff= 2 , 0
                          471.45         1063.64
Permanent Ineff=
       F       F
Bank Sta=360.2,393.7
XS Rating Curve= 0 ,0
Exp/Cntr=0.3,0.1

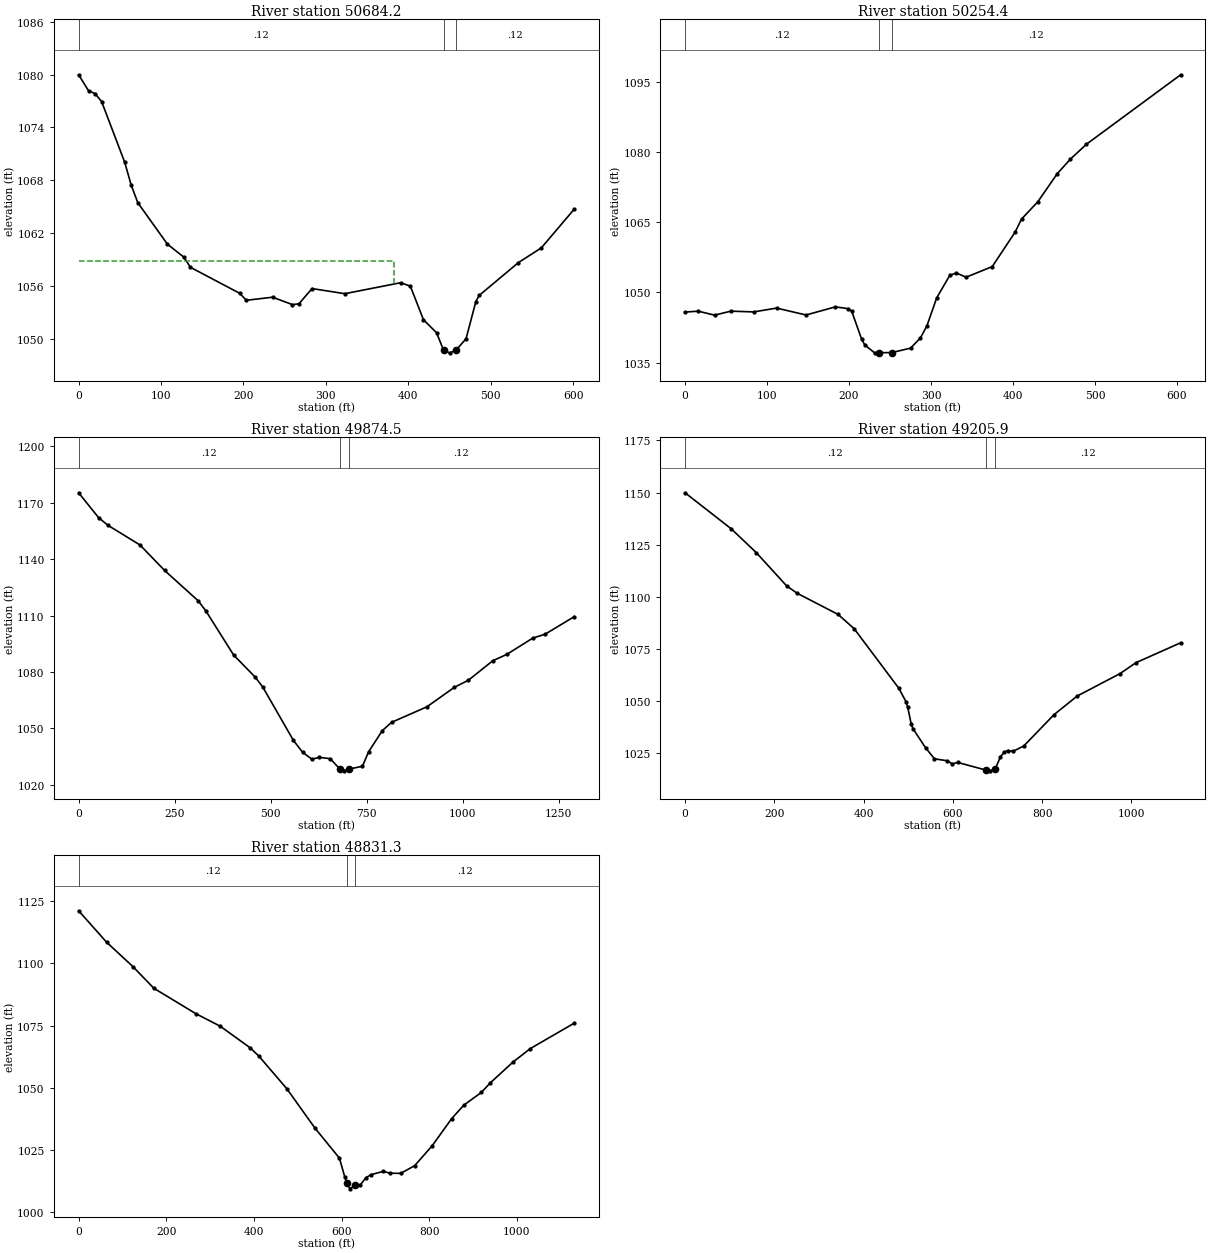
Type RM Length L Ch R = 1 ,50684.2 ,413.5,429.8,446
XS GIS Cut Line= 3
     2348853.654       380771.36     2349112.335      380752.262
     2349397.057      380563.026
#Sta/Elev= 30
       0 1079.97      12 1078.16      20 1077.83    27.9 1076.93    55.9 1070.05
    63.8 1067.45    71.8 1065.46   107.7 1060.76   127.7 1059.28   135.7 1058.13
   195.5 1055.18   203.5 1054.39   235.4 1054.74   259.4  1053.9   267.3 1053.99
   283.2 1055.72     323 1055.14   390.6 1056.38   402.5    1056   418.4 1052.19
   434.3 1050.71   442.9 1048.71   450.2 1048.43   457.9 1048.73   470.1 1050.03
     482 1054.25     486 1054.94   533.7 1058.67   561.5 1060.34   601.3 1064.72
#Mann= 3 ,-1 , 0
       0     .12       0   442.9    .045       0   457.9     .12       0
#XS Ineff= 2 , 0
          382.25 1058.83
Permanent Ineff=
       F       F
Bank Sta=442.9,457.9
XS Rating Curve= 0 ,0
Exp/Cntr=0.3,0.1

Type RM Length L Ch R = 1 ,50254.4 ,390.4,380,369.5
XS GIS Cut Line= 3
      2349105.39      381017.887     2349485.599       381061.29
     2349697.404      380995.318
#Sta/Elev= 30
       0 1045.78    15.9 1045.98    35.9 1045.13    55.8 1045.98    83.7 1045.82
   111.6 1046.64   147.5 1045.16   183.4  1046.9   199.3  1046.5   203.3 1045.94
   215.3 1040.02   219.2 1038.77   231.2 1037.08     237 1037.12     252 1037.13
     275 1038.08     287 1040.24     295 1042.85   306.9 1048.81   322.9 1053.63
   330.9 1054.13   342.8 1053.23   374.7  1055.5   402.5 1062.84   410.4 1065.64
   430.2 1069.33     454 1075.34   469.8 1078.41   489.6 1081.63   604.5 1096.46
#Mann= 3 ,-1 , 0
       0     .12       0     237    .045       0     252     .12       0
Bank Sta=237,252
XS Rating Curve= 0 ,0
Exp/Cntr=0.3,0.1

Type RM Length L Ch R = 1 ,49874.5 ,672.7,668.6,660.8
XS GIS Cut Line= 2
     2348692.716       381633.54     2349905.738      381193.235
#Sta/Elev= 30
       0 1175.32    51.9 1162.11    75.9 1158.06   159.8 1147.54   223.7 1134.01
   311.6 1117.78   331.6 1112.37   403.5    1089   459.4 1077.29   479.4 1071.98
   559.3 1043.54   583.3  1037.2   607.3 1033.53   627.2  1034.5   655.2 1033.79
   679.6 1028.44   691.2 1027.32   703.2  1028.2   739.1 1029.77   755.1 1037.43
   791.1 1048.78     815 1053.14   906.9 1061.39   978.8 1071.81  1014.8 1075.52
  1078.7 1085.94  1114.7 1089.26  1182.6 1097.97  1214.6 1100.02  1290.5 1109.37
#Mann= 3 ,-1 , 0
       0     .12       0   679.6    .045       0   703.2     .12       0
Bank Sta=679.6,703.2
XS Rating Curve= 0 ,0
Exp/Cntr=0.3,0.1

Type RM Length L Ch R = 1 ,49205.9 ,382,374.6,367.2
XS GIS Cut Line= 3
     2349144.743      382311.809     2349429.771      382114.051
     2349970.117      381575.094
#Sta/Elev= 30
       0 1149.87   103.7 1132.52   159.5 1121.15   227.3 1105.23   251.2 1101.64
   342.9 1091.49   378.9 1084.61   478.8 1056.08   494.8 1049.65   498.8 1046.96
   506.7 1038.72   510.7 1036.63   538.7 1027.52   558.7 1022.24   586.7 1021.32
   598.6 1019.81   610.6  1020.5   673.3 1016.87   682.6 1016.47   694.5  1017.2
   706.5 1023.24   714.5 1025.31   722.5 1026.22   734.5 1025.83   758.5 1028.35
   826.4 1043.41   878.3 1052.35   974.2  1063.1  1010.2 1068.38  1110.1  1077.9
#Mann= 3 ,-1 , 0
       0     .12       0   673.3    .045       0   694.5     .12       0
Bank Sta=673.3,694.5
XS Rating Curve= 0 ,0
Exp/Cntr=0.3,0.1

Type RM Length L Ch R = 1 ,48831.3 ,302.2,306.3,310.4
XS GIS Cut Line= 3
     2349458.689      382523.964     2349825.442       382304.78
     2350140.113       381675.44
#Sta/Elev= 30
       0 1121.05    63.9 1108.42   123.8 1098.66   171.7 1089.94   267.5 1079.75
   323.4 1074.69   391.3 1066.07   411.3 1062.72   475.2 1049.61   539.2 1033.84
   595.2 1021.76   607.2 1014.29   612.6 1011.73   619.2 1009.44   631.2 1010.92
   643.1 1011.09   655.1 1013.81   667.1 1015.12   695.1 1016.43   711.1 1015.72
   735.1 1015.65   767.1 1018.77   807.1  1026.8     851 1037.55     879 1043.03
     919 1048.12     939  1051.9     991 1060.28  1030.9 1065.75  1130.9 1075.93
#Mann= 3 ,-1 , 0
       0     .12       0   612.6    .045       0   631.2     .12       0
Bank Sta=612.6,631.2
XS Rating Curve= 0 ,0
Exp/Cntr=0.3,0.1