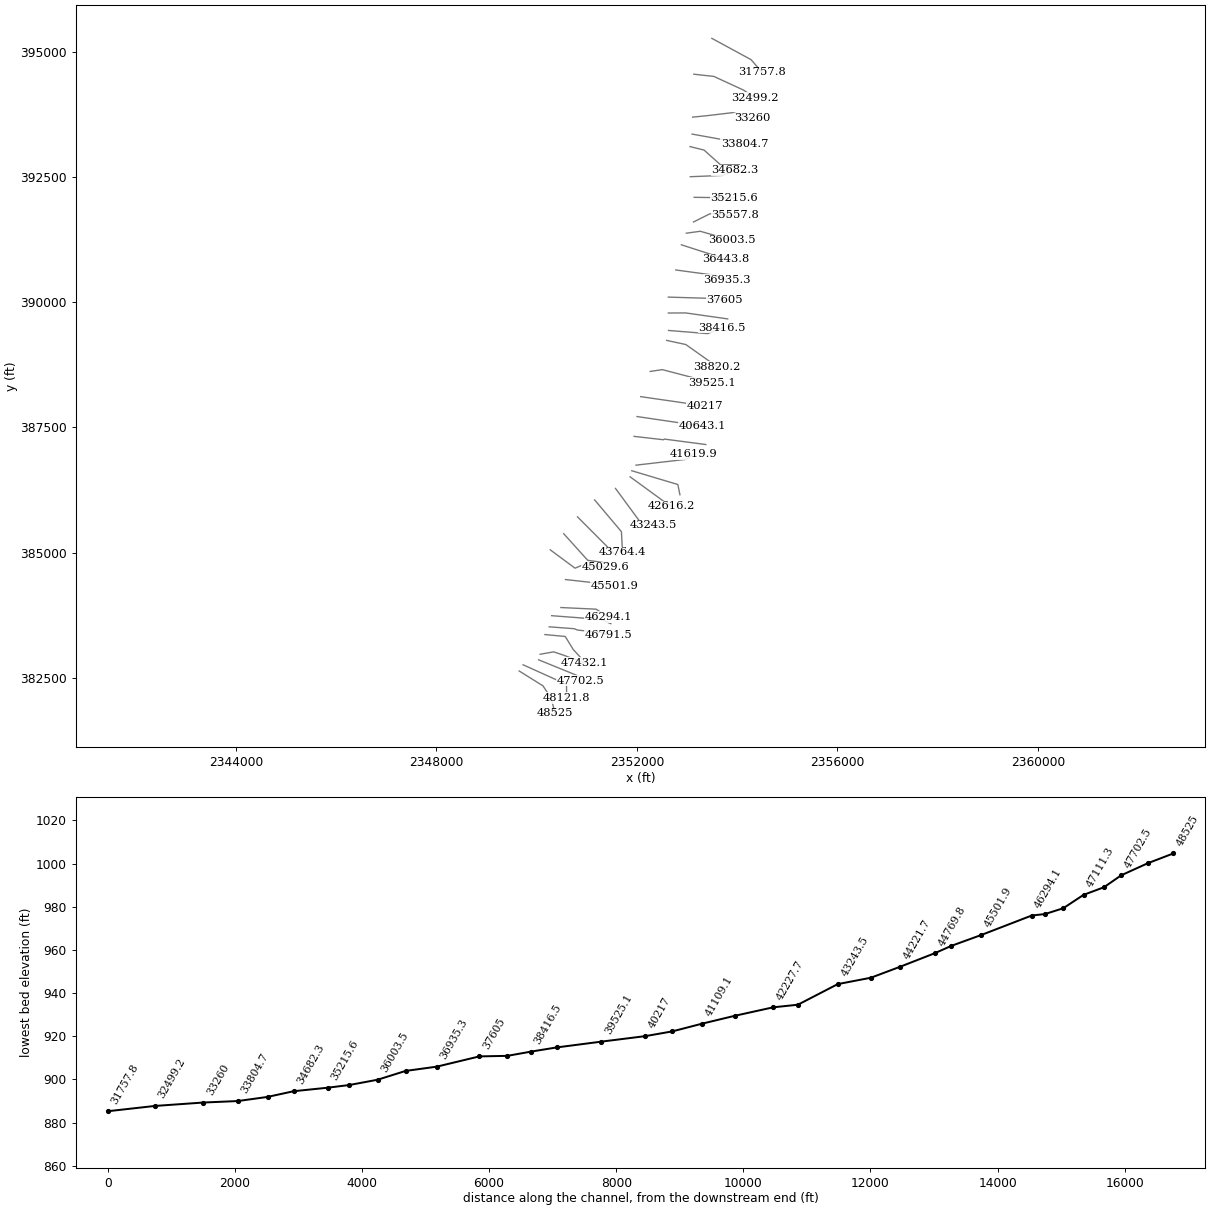
HEC-RAS study MEADOWBRCH.prj: MEADOWBRCH

--- MEADOWBRCH.g01 (geometry) --- (continued)

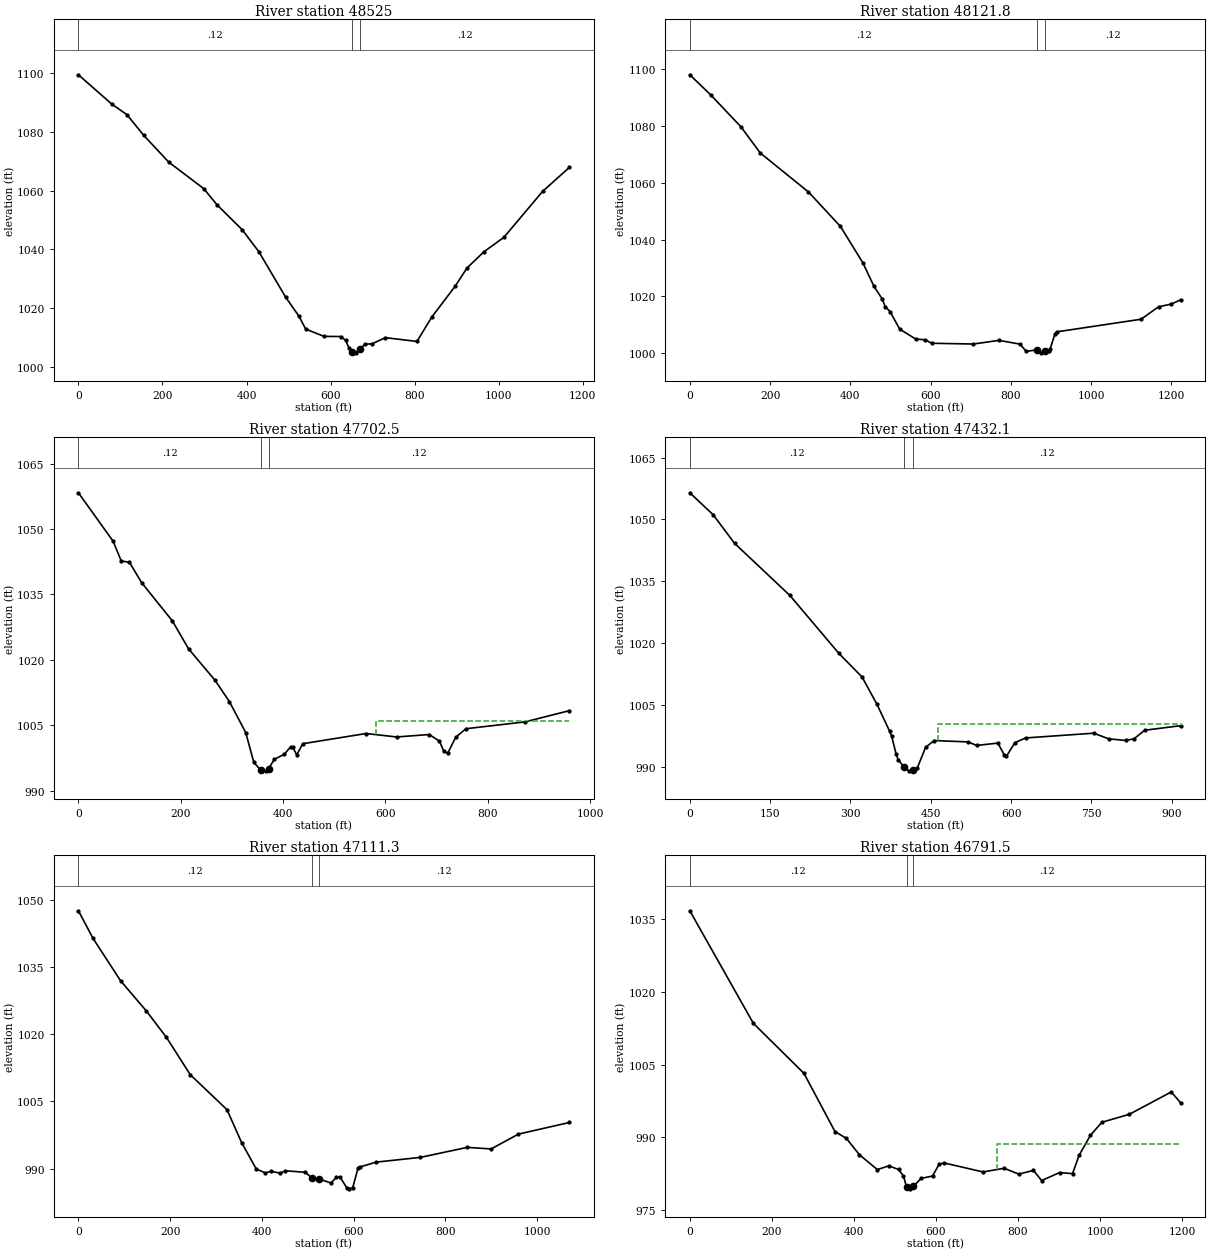
Type RM Length L Ch R = 1 ,48525   ,391.5,403.2,414.7
XS GIS Cut Line= 4
     2349651.831      382634.641     2350127.092      382337.332
     2350289.852      382089.936     2350367.977      381788.287
#Sta/Elev= 30
       0 1099.48    79.5 1089.48   115.3  1085.9   155.1 1078.88   214.7 1069.74
   298.2 1060.66     330 1055.11   389.6 1046.67   429.4 1039.15     493 1023.68
   524.8 1017.16   540.7  1012.8   584.3  1010.3   623.8 1010.25   635.6 1008.98
   643.5 1006.46   651.4 1005.11   659.3 1004.69   669.1 1006.11     683 1007.64
   698.8 1007.77   730.4 1009.87   805.4 1008.57   840.9 1016.91   896.7 1027.47
   924.6 1033.63   964.6 1039.11  1012.5  1044.1  1104.4 1059.72  1168.3 1067.94
#Mann= 3 ,-1 , 0
       0     .12       0   651.4    .045       0   669.1     .12       0
Bank Sta=651.4,669.1
XS Rating Curve= 0 ,0
Exp/Cntr=0.3,0.1

Type RM Length L Ch R = 1 ,48121.8 ,419.3,419.3,419
XS GIS Cut Line= 3
     2349729.956      382758.339     2350595.842      382367.714
     2350600.182      382094.276
#Sta/Elev= 30
       0 1097.96    51.9 1090.92   127.7  1079.6   175.6 1070.44   295.4 1056.76
   375.2 1044.64   431.1 1031.83     459  1023.5     479 1019.16   486.9 1016.39
   498.9 1014.67   522.8 1008.51   562.8    1005   586.7 1004.74   602.7 1003.52
   706.4 1003.25   770.3 1004.54   822.2 1003.22   838.2 1000.69   865.5 1001.19
   874.1 1000.15   886.1  1000.7     894 1000.63     898 1001.67     910  1006.9
     914 1007.53  1124.3 1011.97  1167.9 1016.36  1199.6  1017.3  1223.4 1018.84
#Mann= 3 ,-1 , 0
       0     .12       0   865.5    .045       0   886.1     .12       0
Bank Sta=865.5,886.1
XS Rating Curve= 0 ,0
Exp/Cntr=0.3,0.1

Type RM Length L Ch R = 1 ,47702.5 ,268.9,270.4,271.9
XS GIS Cut Line= 3
      2350040.16      382857.525     2350844.847        382529.4
     2350873.493      382443.463
#Sta/Elev= 30
       0 1058.31    67.8  1047.2    83.7 1042.67    99.7 1042.38   123.6 1037.69
   183.4 1028.96   215.3 1022.51   267.1 1015.29     295 1010.43   326.9 1003.33
   342.8  996.48   356.8  994.62   366.7  994.54   371.8  995.05   382.7  997.16
   402.6  998.37   414.6 1000.03   418.6 1000.04   426.5  998.19   438.5 1000.76
   562.1  1003.1   621.9 1002.31   685.6 1002.87   705.6 1001.34   713.6  999.15
   721.5  998.53   737.5 1002.28   757.4  1004.2     873 1005.77   959.6 1008.35
#Mann= 3 ,-1 , 0
       0     .12       0   356.8    .045       0   371.8     .12       0
#XS Ineff= 2 , 0
                          581.68         1006.08
Permanent Ineff=
       F       F
Bank Sta=356.8,371.8
XS Rating Curve= 0 ,0
Exp/Cntr=0.3,0.1

Type RM Length L Ch R = 1 ,47432.1 ,335.8,320.9,306.2
XS GIS Cut Line= 4
     2350070.495      382968.756     2350340.633      383016.585
     2350535.449      382950.853     2350945.495      382799.485
#Sta/Elev= 30
       0 1056.47    43.7 1051.13    83.5 1044.22   186.9 1031.56   278.3 1017.52
   321.8 1011.76   349.5 1005.16   373.2  998.61   377.1  997.36     385  993.22
     389  991.74   399.5  990.04   408.8  989.02   416.7  989.15   424.6  989.65
   440.4  994.73   456.2  996.36   519.7  996.04   535.6  995.18   575.3  995.75
   587.2  992.89   591.2  992.55   607.1  995.85     627     997   754.1  998.15
   781.9   996.8   813.7  996.38   829.6   996.8   849.5  998.87     917  999.98
#Mann= 3 ,-1 , 0
       0     .12       0   399.5    .045       0   416.7     .12       0
#XS Ineff= 2 , 0
                           464.1         1000.29
Permanent Ineff=
       F       F
Bank Sta=399.5,416.7
XS Rating Curve= 0 ,0
Exp/Cntr=0.3,0.1

Type RM Length L Ch R = 1 ,47111.3 ,304.9,319.8,334.8
XS GIS Cut Line= 4
     2350165.547      383361.985      2350571.41      383323.671
     2350730.264      383063.254     2350972.451      382800.233
#Sta/Elev= 30
       0 1047.57      32 1041.39    91.9 1031.95   147.9 1025.23   191.8 1019.32
   243.8 1010.98   323.7 1003.19   355.7  995.83   387.7  989.92   407.7  989.04
   419.6  989.42   439.4  989.01   451.2  989.53   494.8  989.19   509.7  987.82
   524.7  987.71   550.3   986.8   562.2  988.05   570.1  988.13   585.9  985.58
   589.9   985.5   597.8  985.75   609.7  990.23   613.7  990.39   649.3  991.47
   744.5  992.51   847.8  994.76   899.4   994.4     959  997.72  1070.2 1000.31
#Mann= 3 ,-1 , 0
       0     .12       0   509.7    .045       0   524.7     .12       0
Bank Sta=509.7,524.7
XS Rating Curve= 0 ,0
Exp/Cntr=0.3,0.1

Type RM Length L Ch R = 1 ,46791.5 ,279.5,286.4,292.9
XS GIS Cut Line= 5
      2350251.05      383516.499     2350754.522      383478.304
     2350811.814      383452.262      2351273.62      383403.651
     2351431.606      383356.776
#Sta/Elev= 30
       0 1036.78     155  1013.5   278.3 1003.17   353.8  991.15   381.7  989.73
   413.5  986.34   457.2  983.28     485  984.05   508.8   983.3   520.6  981.98
   528.5  979.66   536.4   979.3   544.8  979.81   563.9  981.46   591.7  981.95
   607.5  984.35   619.4  984.66   714.7  982.79   766.3  983.55     802  982.34
   837.7  983.12   857.6  981.01   901.2  982.66     933  982.45   948.9  986.23
   976.6  990.36  1004.4  993.06  1071.4  994.71  1173.5  999.32    1197  997.04
#Mann= 3 ,-1 , 0
       0     .12       0   528.5    .045       0   544.8     .12       0
#XS Ineff= 2 , 0
                           748.9          988.58
Permanent Ineff=
       F       F
Bank Sta=528.5,544.8
XS Rating Curve= 0 ,0
Exp/Cntr=0.3,0.1

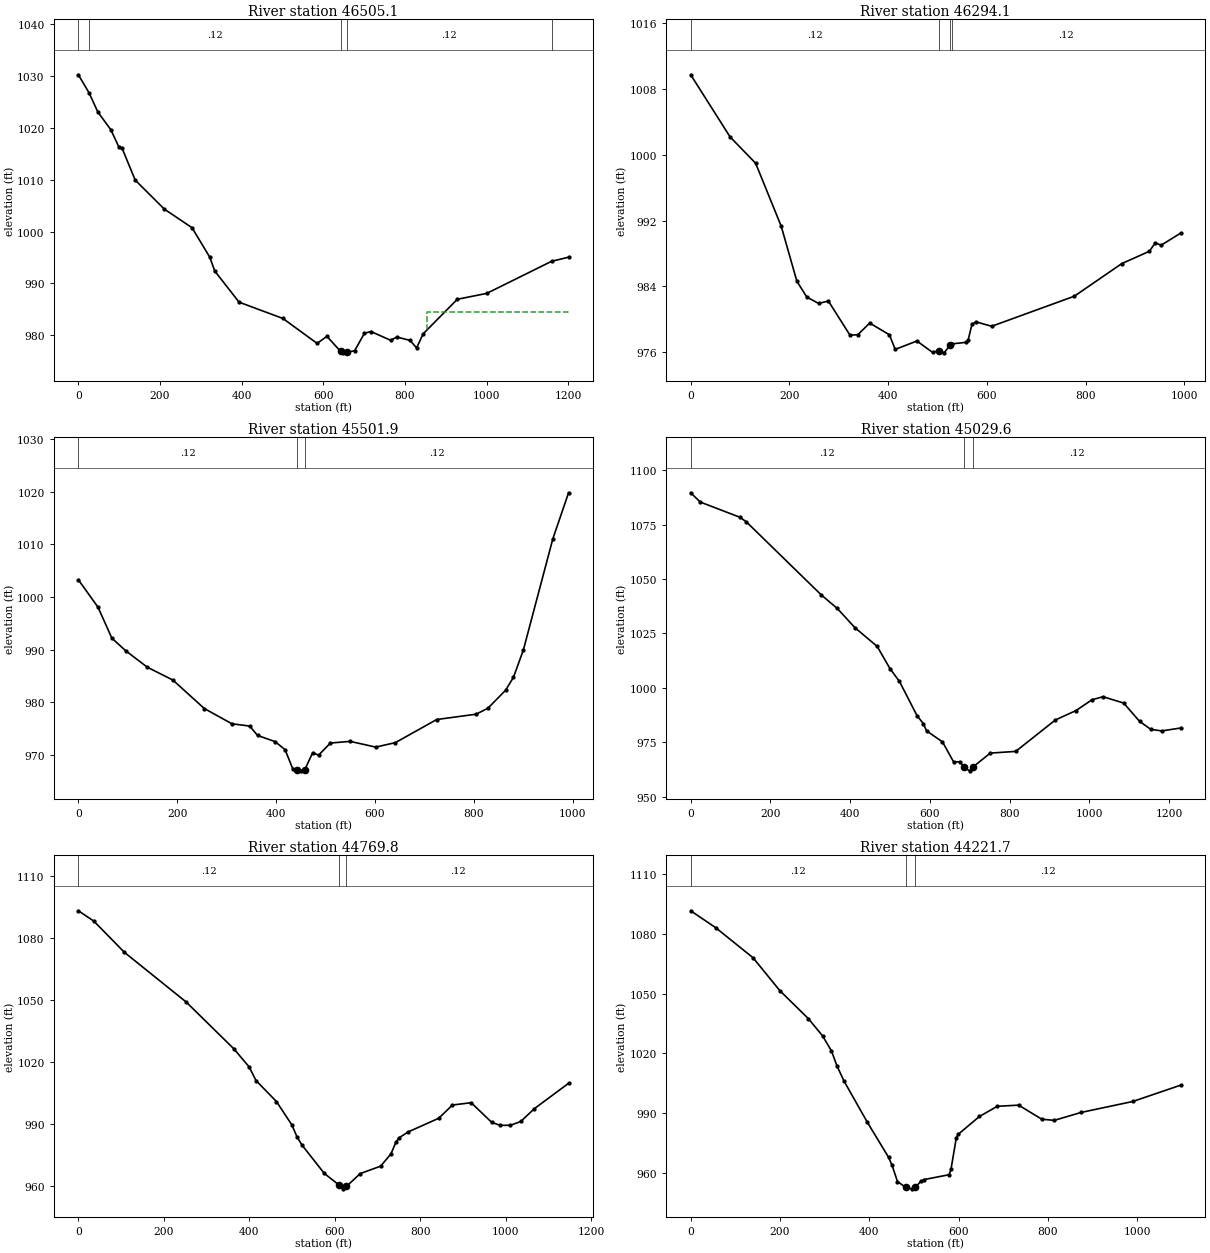
Type RM Length L Ch R = 1 ,46505.1 ,220,211,209.8
XS GIS Cut Line= 4
     2350299.661      383738.721     2350803.133      383700.526
     2351292.717      383660.596     2351480.217      383578.999
#Sta/Elev= 30
       0 1030.22   26.211026.741    47.7 1023.04    79.5 1019.63    99.4 1016.27
   107.3 1016.02   139.2 1009.91   210.7 1004.31   278.3 1000.74     322  995.03
     334  992.39   393.6  986.38   500.9  983.24   584.8  978.43   608.8   979.8
   642.3  976.88   648.7  976.61   657.3  976.71   676.6  977.01   700.6  980.38
   716.6  980.72   764.5  979.04   780.5  979.66   812.4     979   828.4  977.56
   844.4  980.27   928.2  986.94  1000.1  988.07 1158.91994.2548  1200.6  995.05
#Mann= 5 ,-1 , 0
       0     .06       0   26.21     .12       0   642.3    .045       0
   657.3     .12       0 1158.91     .06       0
#XS Ineff= 2 , 0
                          853.14           984.5
Permanent Ineff=
       F       F
Bank Sta=642.3,657.3
XS Rating Curve= 0 ,0
Exp/Cntr=0.3,0.1

Type RM Length L Ch R = 1 ,46294.1 ,783.5,792.1,794
XS GIS Cut Line= 3
     2350483.689      383901.481     2351188.116      383868.929
     2351429.435      383712.245
#Sta/Elev= 30
       0 1009.73    79.7 1002.18   131.5  998.97   183.3  991.32   215.1  984.61
   235.1   982.7     259  981.92   278.9  982.21   322.7  978.05   338.6  978.12
   362.6  979.53   402.4  978.11   414.3  976.33   458.2  977.35     490  975.96
     502  976.19   513.3  975.91   525.9  976.88   528.3  976.99   557.8  977.19
   561.8  977.42   569.7  979.38   577.7  979.68   609.6  979.14   777.1   982.8
     873  986.76     929  988.26     941  989.29   952.9     989   992.9  990.49
#Mann= 4 ,-1 , 0
       0     .12       0     502    .045       0   525.9    .045       0
   528.3     .12       0
Bank Sta=502,525.9
XS Rating Curve= 0 ,0
Exp/Cntr=0.3,0.1

Type RM Length L Ch R = 1 ,45501.9 ,461.4,472.3,481.7
XS GIS Cut Line= 3
     2350575.269      384460.509     2351410.338      384366.759
     2351554.992      384322.799
#Sta/Elev= 30
       0 1003.28    39.8  998.05    67.7  992.17    95.6  989.78   139.4  986.64
   191.2  984.19   254.9  978.76   310.6  975.87   346.5  975.43   362.4  973.65
   398.2  972.46   418.2  970.92   434.1  967.18   442.8  967.05     450  966.91
   457.8  967.09   473.9  970.36   485.9   969.9   509.8   972.2   549.6  972.52
   601.4  971.43   641.2  972.28   724.8  976.68   804.5  977.69   828.4  978.83
   864.2  982.26   880.1  984.73     900  989.89   959.7 1011.08   991.5 1019.84
#Mann= 3 ,-1 , 0
       0     .12       0   442.8    .045       0   457.8     .12       0
Bank Sta=442.8,457.8
XS Rating Curve= 0 ,0
Exp/Cntr=0.3,0.1

Type RM Length L Ch R = 1 ,45029.6 ,288,259.8,231.7
XS GIS Cut Line= 4
     2350271.449      385054.259      2350765.93      384687.383
     2350920.755      384752.176     2351364.888      384708.216
#Sta/Elev= 30
       0 1089.62      24 1085.36   123.9 1078.34   139.9 1076.22   327.8 1042.65
   367.8 1036.47   411.8 1027.67   467.8 1019.05   499.8 1008.88   523.8 1002.92
   567.7  987.27   583.7  983.54   591.7  980.24   631.7  975.16   659.7  965.94
   675.7  966.04   685.4   963.5   699.6  961.86   707.6  963.53   751.6  970.01
   815.4  970.79     915  985.24   966.9  989.57  1006.7   994.5  1034.6  995.92
  1086.4  992.99  1126.2   984.6  1154.2  980.93    1182   980.2  1229.9  981.56
#Mann= 3 ,-1 , 0
       0     .12       0   685.4    .045       0   707.6     .12       0
Bank Sta=685.4,707.6
XS Rating Curve= 0 ,0
Exp/Cntr=0.3,0.1

Type RM Length L Ch R = 1 ,44769.8 ,547.9,548.2,548.3
XS GIS Cut Line= 3
      2350540.16      385375.754     2351019.326      384844.504
     2351446.797      384783.426
#Sta/Elev= 30
       0 1093.25      36 1088.28   107.9 1073.08   251.8 1049.12   363.7 1026.38
   399.7 1017.57   415.7 1010.96   463.6 1000.78   499.6  989.48   511.6  983.68
   523.6  979.61   575.5  965.96   609.4  960.41   619.5  958.47   627.5  959.68
   659.5  965.85   707.4  969.47   731.4  975.35   743.4  981.19   751.4  983.32
   771.4  986.02   843.4  992.68   875.4   999.1   919.3 1000.22   967.3  990.69
   987.3  989.24  1011.3  989.28  1035.3  991.12  1067.3  997.36  1147.2 1009.62
#Mann= 3 ,-1 , 0
       0     .12       0   609.4    .045       0   627.5     .12       0
Bank Sta=609.4,627.5
XS Rating Curve= 0 ,0
Exp/Cntr=0.3,0.1

Type RM Length L Ch R = 1 ,44221.7 ,459.3,457.3,455.5
XS GIS Cut Line= 2
     2350816.201      385711.692     2351590.894      384934.467
#Sta/Elev= 30
       0 1091.46    55.9    1083   139.7  1067.9   199.5 1051.46   263.4 1037.44
   295.3 1028.76   315.2 1021.24   327.2 1013.87   343.2 1006.16     395  985.69
   442.9  967.98   450.9  963.87   462.9  955.83     481  952.94   494.8  952.16
   502.8  952.86   514.8  955.86   522.8  956.82   578.6  959.24   582.6  961.85
   594.6   977.7   598.6  979.42   646.4  988.42   686.4  993.52   734.2  994.09
   786.1  987.02     814  986.47   873.9  990.43   989.6  995.92  1097.4 1004.14
#Mann= 3 ,-1 , 0
       0     .12       0     481    .045       0   502.8     .12       0
Bank Sta=481,502.8
XS Rating Curve= 0 ,0
Exp/Cntr=0.3,0.1

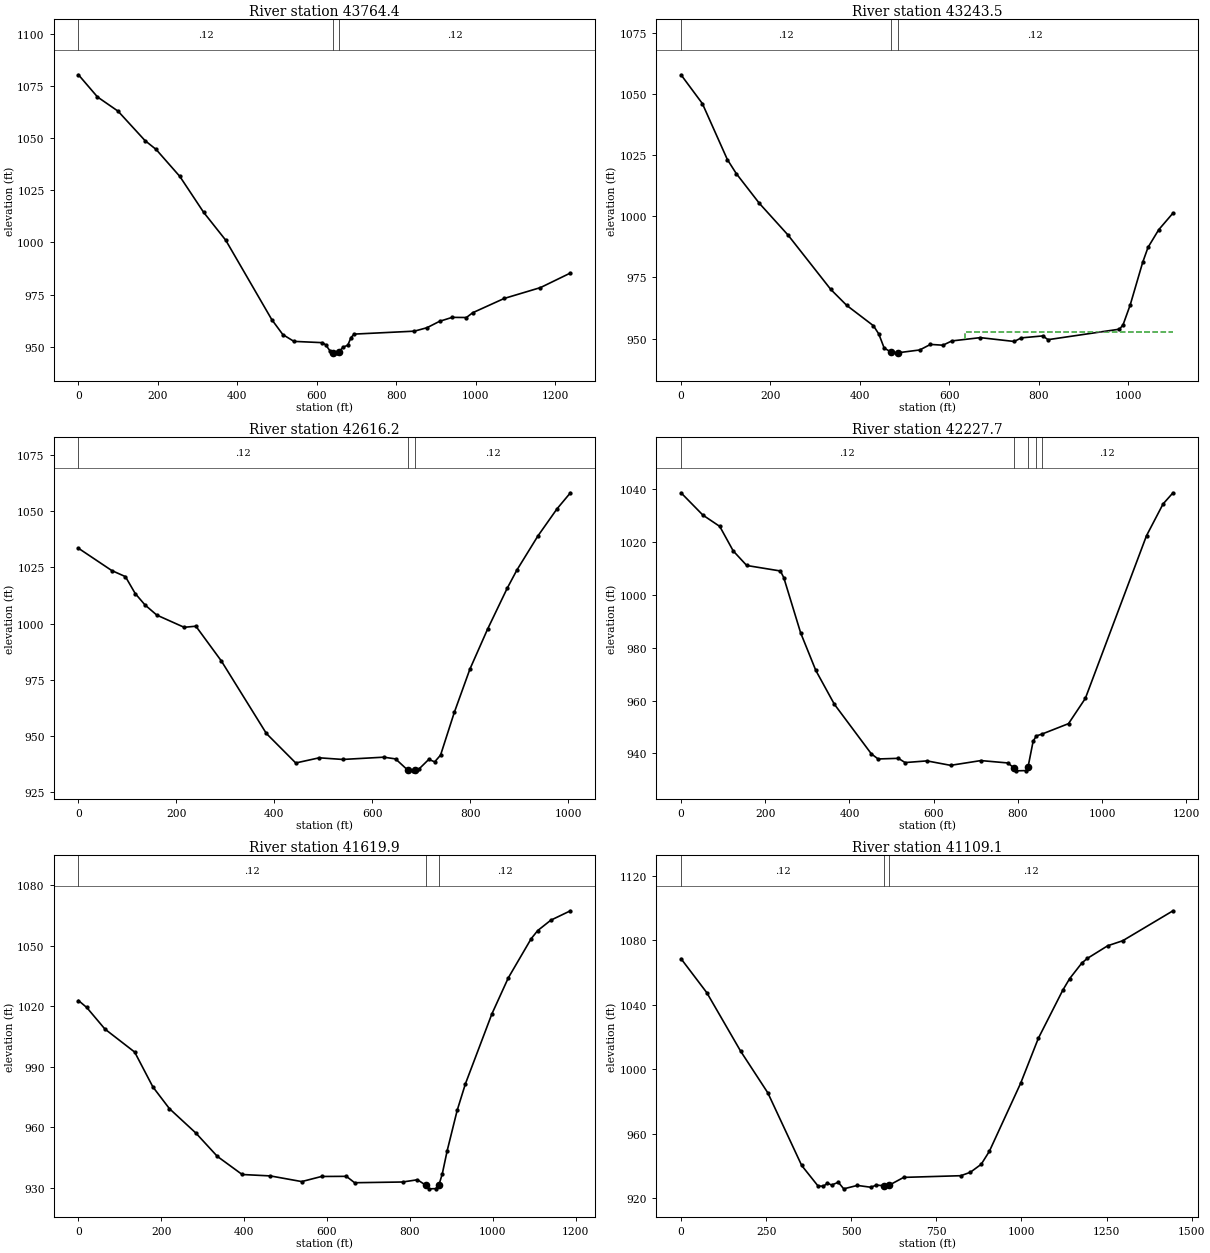
Type RM Length L Ch R = 1 ,43764.4 ,522.4,520.9,519.3
XS GIS Cut Line= 3
     2351157.347      386050.233     2351692.288      385416.095
     2351712.899      385007.865
#Sta/Elev= 30
       0 1080.27    47.9 1069.65    99.7 1062.84   167.5 1048.76   195.4 1044.53
   255.3 1031.56   315.1  1014.4   370.9    1001   486.6  963.03   514.5  955.84
   542.4   952.6   614.2  951.98   622.2  950.96   634.2  947.79   640.2  947.24
   650.2  947.11   655.2  947.51   666.1   949.8   678.1  950.81     686  954.43
     694  956.08   845.5  957.49   877.3  959.14     909  962.21   940.8   964.1
   976.5  964.02   992.3  966.31  1071.7  973.16    1163  978.36  1238.4  985.34
#Mann= 3 ,-1 , 0
       0     .12       0   640.2    .045       0   655.2     .12       0
Bank Sta=640.2,655.2
XS Rating Curve= 0 ,0
Exp/Cntr=0.3,0.1

Type RM Length L Ch R = 1 ,43243.5 ,620.2,627.3,634.4
XS GIS Cut Line= 3
     2351574.014        386279.4     2352052.815       385627.87
     2352331.034      385541.549
#Sta/Elev= 30
       0 1057.92    47.8 1046.12   103.6 1023.24   123.5 1017.51   175.2 1005.31
     239   992.4   334.6  970.14   370.4  963.58   430.2  955.24   442.1  951.88
   454.1  946.14   469.3  944.49   481.9  944.16   484.3  944.17   533.7  945.34
   557.6  947.61   585.5  947.28   605.4  949.03   669.1  950.38   744.8  948.81
   760.8  950.28   808.5  951.08   820.5  949.55   980.1  953.84   988.1   955.6
  1004.1  963.74    1032  981.17    1044  987.33  1067.9  994.54  1099.8 1001.34
#Mann= 3 ,-1 , 0
       0     .12       0   469.3    .045       0   484.3     .12       0
#XS Ineff= 2 , 0
                          635.61          952.86
Permanent Ineff=
       F       F
Bank Sta=469.3,484.3
XS Rating Curve= 0 ,0
Exp/Cntr=0.3,0.1

Type RM Length L Ch R = 1 ,42616.2 ,380.3,388.4,396.5
XS GIS Cut Line= 3
      2351865.68      386511.171     2352582.763      385988.547
     2352682.597      385926.966
#Sta/Elev= 30
       0  1033.5      68  1023.6    95.9  1020.9   115.9 1013.39   135.9 1008.32
   159.9 1003.82   215.8  998.38   239.8  998.87   291.8  983.42   383.7  951.21
   443.7   938.1   491.6   940.4   539.6  939.67   623.5  940.68   647.5  939.91
   672.7  934.87   683.5  934.61   687.7  934.77   695.5  935.46   715.4   939.7
   727.4   938.6   739.4   941.6   767.4  960.54   799.4  979.85   835.4  997.56
   875.3 1015.66   895.1 1023.76   938.2 1038.98   977.2 1051.02  1004.6 1058.15
#Mann= 3 ,-1 , 0
       0     .12       0   672.7    .045       0   687.7     .12       0
Bank Sta=672.7,687.7
XS Rating Curve= 0 ,0
Exp/Cntr=0.3,0.1

Type RM Length L Ch R = 1 ,42227.7 ,599,607.9,616.7
XS GIS Cut Line= 3
     2351898.277      386632.854     2352818.006      386357.905
     2352859.239      386153.912
#Sta/Elev= 30
       0 1038.58      52 1030.13      92 1025.86     124 1016.58     156 1011.08
     236    1009     244 1006.48     284  985.61     320   971.4     364  958.62
     452  939.81     468   937.9     516  938.14     532  936.54     584  937.17
     640  935.49     712  937.29     776  936.39   789.6  934.62     796  933.41
     820  933.51     824  934.91     836  944.59  843.61946.6183  856.12947.2621
     920  951.26     960  960.82  1105.2 1022.35  1144.5 1034.35  1168.1 1038.58
#Mann= 5 ,-1 , 0
       0     .12       0   789.6    .045       0     824     .12       0
  843.61     .06       0  856.12     .12       0
Bank Sta=789.6,824
XS Rating Curve= 0 ,0
Exp/Cntr=0.3,0.1

Type RM Length L Ch R = 1 ,41619.9 ,505.6,510.7,510.4
XS GIS Cut Line= 3
     2351982.503       386744.19     2352989.447      386861.377
     2353128.336      386965.544
#Sta/Elev= 30
       0 1022.84      20 1019.38    63.9 1008.68   135.7  997.27   179.6  980.01
   219.5  969.23   283.4  957.12   335.2  945.55   395.1  936.57     463  935.87
   538.8  933.06   586.7  935.59   646.6  935.66   666.5  932.49   782.3  932.85
   818.2  933.96   838.1  931.27   846.1  929.46   862.1  929.56   870.1  931.48
     878   936.8     890  948.44     914  968.35   933.9  981.53   997.8 1016.19
  1037.4 1034.06  1092.6 1053.48  1108.4 1057.52    1140 1062.66  1187.4 1067.33
#Mann= 3 ,-1 , 0
       0     .12       0   838.1    .045       0   870.1     .12       0
Bank Sta=838.1,870.1
XS Rating Curve= 0 ,0
Exp/Cntr=0.3,0.1

Type RM Length L Ch R = 1 ,41109.1 ,477.6,466,459.7
XS GIS Cut Line= 4
     2351944.978      387318.931     2352530.687      387251.619
      2352551.52      387264.639      2353375.52      387156.238
#Sta/Elev= 30
       0 1068.51    75.7 1047.45   175.3 1011.12     255  985.35   354.5  940.32
   402.3  927.65   418.3  927.44   430.2  929.38   442.2   928.2   462.1   929.9
     478  925.84   517.9  927.96   557.7  926.82   573.6  928.17   596.6  927.74
   611.6  928.12   654.1  932.94   821.9  933.98   849.9  936.11   881.8  941.06
   905.8  949.13   997.7  991.31  1049.7 1019.18  1121.6 1049.04  1141.6 1056.14
  1177.5 1065.84  1193.5 1068.67  1253.4 1076.52  1297.4 1079.62  1445.2  1098.2
#Mann= 3 ,-1 , 0
       0     .12       0   596.6    .045       0   611.6     .12       0
Bank Sta=596.6,611.6
XS Rating Curve= 0 ,0
Exp/Cntr=0.3,0.1

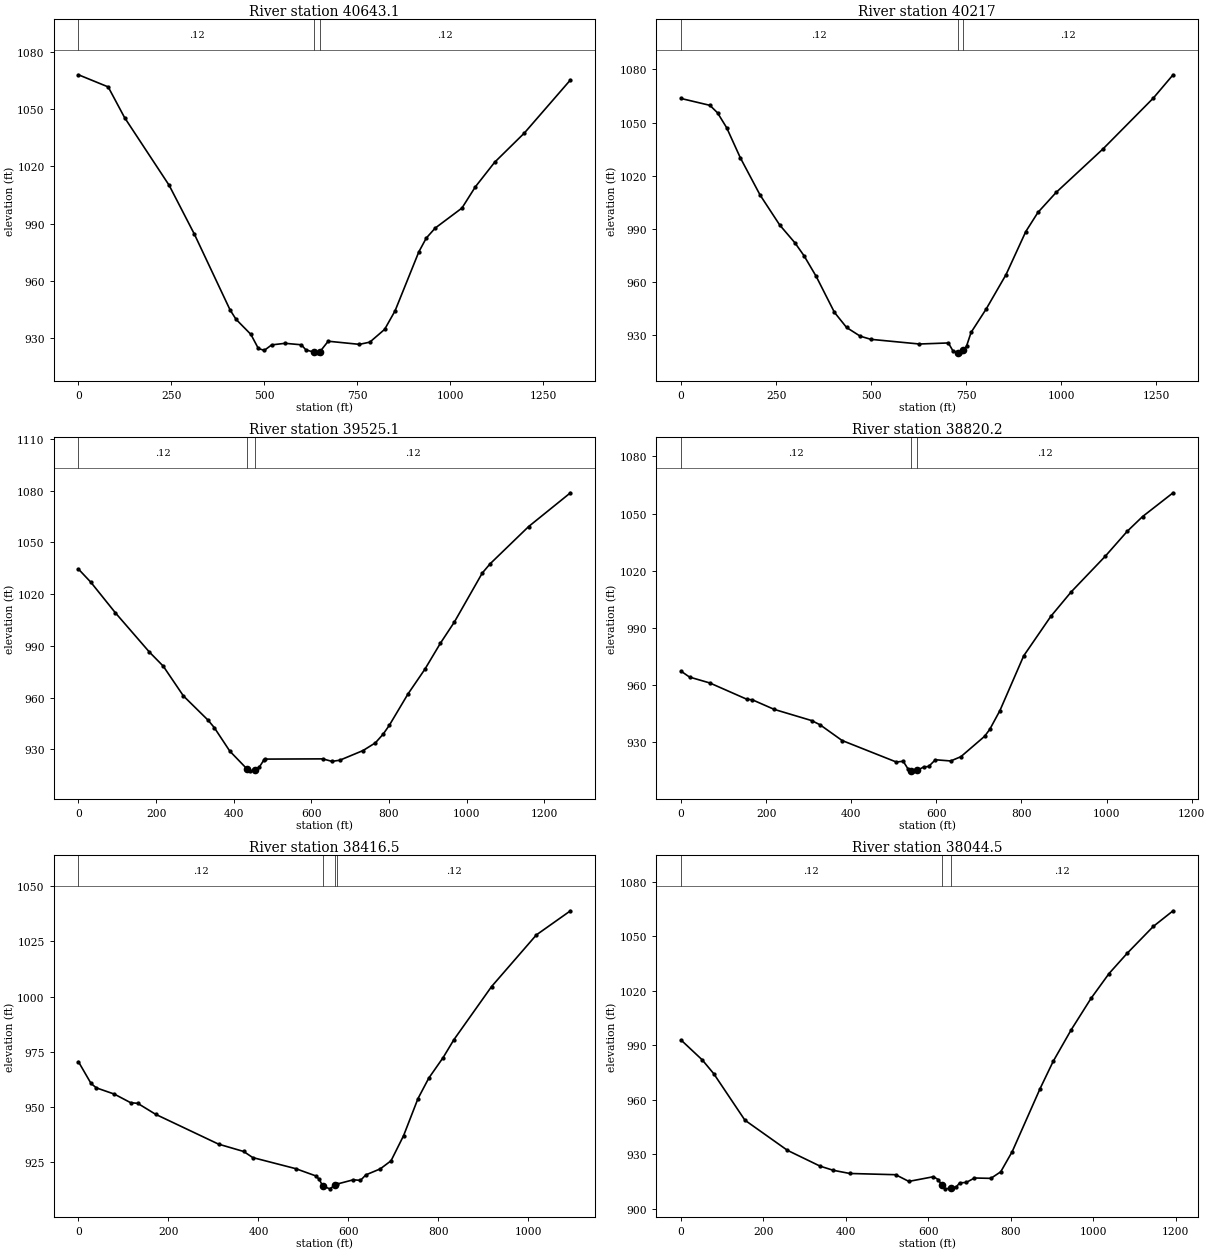
Type RM Length L Ch R = 1 ,40643.1 ,426.1,426.1,426.1
XS GIS Cut Line= 2
     2352003.824      387714.726     2353312.441      387521.838
#Sta/Elev= 30
       0 1068.06    79.9  1061.7   123.9 1045.64   243.8 1010.12   311.7  984.48
   407.6  944.79   423.6  939.87   463.6  931.94   483.6  924.58   499.5  923.56
   519.5  926.45   555.5  927.27   599.4   926.5   611.4  923.82   634.4  922.58
   643.4  922.28   649.4  922.92   671.4  928.37   755.3  926.73   783.3  927.89
   823.2  934.59   851.2   944.3   915.1  975.23   935.1  982.45   959.1  987.69
    1031  998.18    1067  1009.3    1119 1022.21  1198.9 1037.54  1322.8 1065.39
#Mann= 3 ,-1 , 0
       0     .12       0   634.4    .045       0   649.4     .12       0
Bank Sta=634.4,649.4
XS Rating Curve= 0 ,0
Exp/Cntr=0.3,0.1

Type RM Length L Ch R = 1 ,40217   ,694.4,691.9,689.2
XS GIS Cut Line= 2
     2352077.013      388112.065     2353358.371      387926.915
#Sta/Elev= 30
       0 1063.56    75.9 1059.69    95.9 1055.49   119.9 1047.11   155.8 1030.18
   207.8 1009.15   259.7  992.15   299.7  982.12   323.7  974.81   355.6  963.19
   403.6  942.91   435.6  934.37   471.5  929.46   499.5  927.69   627.4  925.05
   703.3  925.65   715.3  921.24     728  920.26   735.2  920.07     743  921.59
   751.2  923.86   763.2  931.61   803.2  944.91   855.1  964.19   907.1  988.47
     939  999.26     987 1010.57  1110.8 1035.21  1242.7 1063.78  1294.7 1076.93
#Mann= 3 ,-1 , 0
       0     .12       0     728    .045       0     743     .12       0
Bank Sta=728,743
XS Rating Curve= 0 ,0
Exp/Cntr=0.3,0.1

Type RM Length L Ch R = 1 ,39525.1 ,708.4,704.9,699
XS GIS Cut Line= 3
     2352266.722      388615.338     2352506.305      388651.796
     2353498.213      388392.679
#Sta/Elev= 30
       0  1034.5    31.8 1026.91    95.4 1009.08   182.8  986.38   218.5  978.21
   270.3  960.98   334.1  946.85     350  942.56   389.9  928.94   433.8  918.71
   441.8  917.52   454.9  918.12   465.7  919.61   477.7  923.82   481.7  924.33
   629.3  924.46   653.2     923   673.2  923.68     733  929.27   764.9  933.75
   784.9  938.78   800.8  943.93   848.7  962.03   892.6   976.5   932.4  991.51
   968.4 1003.81  1040.2 1032.18  1060.1 1037.48  1159.8 1059.19  1267.5 1078.75
#Mann= 3 ,-1 , 0
       0     .12       0   433.8    .045       0   454.9     .12       0
Bank Sta=433.8,454.9
XS Rating Curve= 0 ,0
Exp/Cntr=0.3,0.1

Type RM Length L Ch R = 1 ,38820.2 ,392.2,403.7,415.3
XS GIS Cut Line= 3
     2352594.847      389235.129     2352976.426      389153.044
     2353601.426      388710.335
#Sta/Elev= 30
       0  967.19    19.9   964.1    67.7  960.99   155.3  952.37   167.3  952.18
     219  947.11   306.7  941.25   326.6  939.03   378.4  930.77     506  919.45
     522  919.88   533.9  915.62   539.8   914.9   545.9  914.83   554.8  915.01
   569.8  916.84   581.8  917.12   597.7  920.65   633.6  920.02   657.6  922.27
   713.4     933   725.4  936.62   749.3   946.5   805.2  975.27     869  996.03
   916.9 1008.89   996.6 1027.52  1048.5  1040.7  1084.4 1048.41  1156.2 1060.93
#Mann= 3 ,-1 , 0
       0     .12       0   539.8    .045       0   554.8     .12       0
Bank Sta=539.8,554.8
XS Rating Curve= 0 ,0
Exp/Cntr=0.3,0.1

Type RM Length L Ch R = 1 ,38416.5 ,373.3,372.1,370.6
XS GIS Cut Line= 3
     2352631.808       389433.86     2353411.763      389370.542
     2353700.826      389485.126
#Sta/Elev= 30
       0  970.48      28  960.62    39.9  958.63    79.8  955.81   115.8  951.94
   131.8  951.62   171.7  946.64   311.4  933.14   367.3  929.81   387.3  927.06
   483.1  922.02     527  918.79     535  917.25     543   914.1   558.9  912.89
   570.9  914.74   575.1  915.07   610.8  916.99   626.8  916.73   638.8  919.22
   670.7  921.93   694.7   925.6   722.6     937   754.6  953.79   778.5  963.04
   810.4  972.35   834.4  980.47   918.1 1004.54  1017.7 1027.95  1093.5 1038.88
#Mann= 4 ,-1 , 0
       0     .12       0     543    .045       0   570.9    .045       0
   575.1     .12       0
Bank Sta=543,570.9
XS Rating Curve= 0 ,0
Exp/Cntr=0.3,0.1

Type RM Length L Ch R = 1 ,38044.5 ,435.1,439.5,443.3
XS GIS Cut Line= 3
     2352627.909      389782.001     2352973.388      389783.686
     2353813.232      389664.328
#Sta/Elev= 30
       0  992.91    51.6  981.93    79.4  974.34   154.9  948.76   258.1  932.15
   337.5  923.42   369.4  921.14   409.2   919.4   520.7  918.71   552.6  915.03
   612.3   917.6   624.3  915.99   632.2  912.94   640.2  910.93   655.7  911.32
   668.1  912.07     676  914.22     692  914.45   711.9   916.9   751.7   916.7
   775.6  920.31   803.5  931.44   871.2  966.19     903  981.22   946.8  998.62
   994.6 1015.82  1038.4 1029.54  1082.2 1040.65    1146 1055.53  1193.8 1064.12
#Mann= 3 ,-1 , 0
       0     .12       0   632.2    .045       0   655.7     .12       0
Bank Sta=632.2,655.7
XS Rating Curve= 0 ,0
Exp/Cntr=0.3,0.1

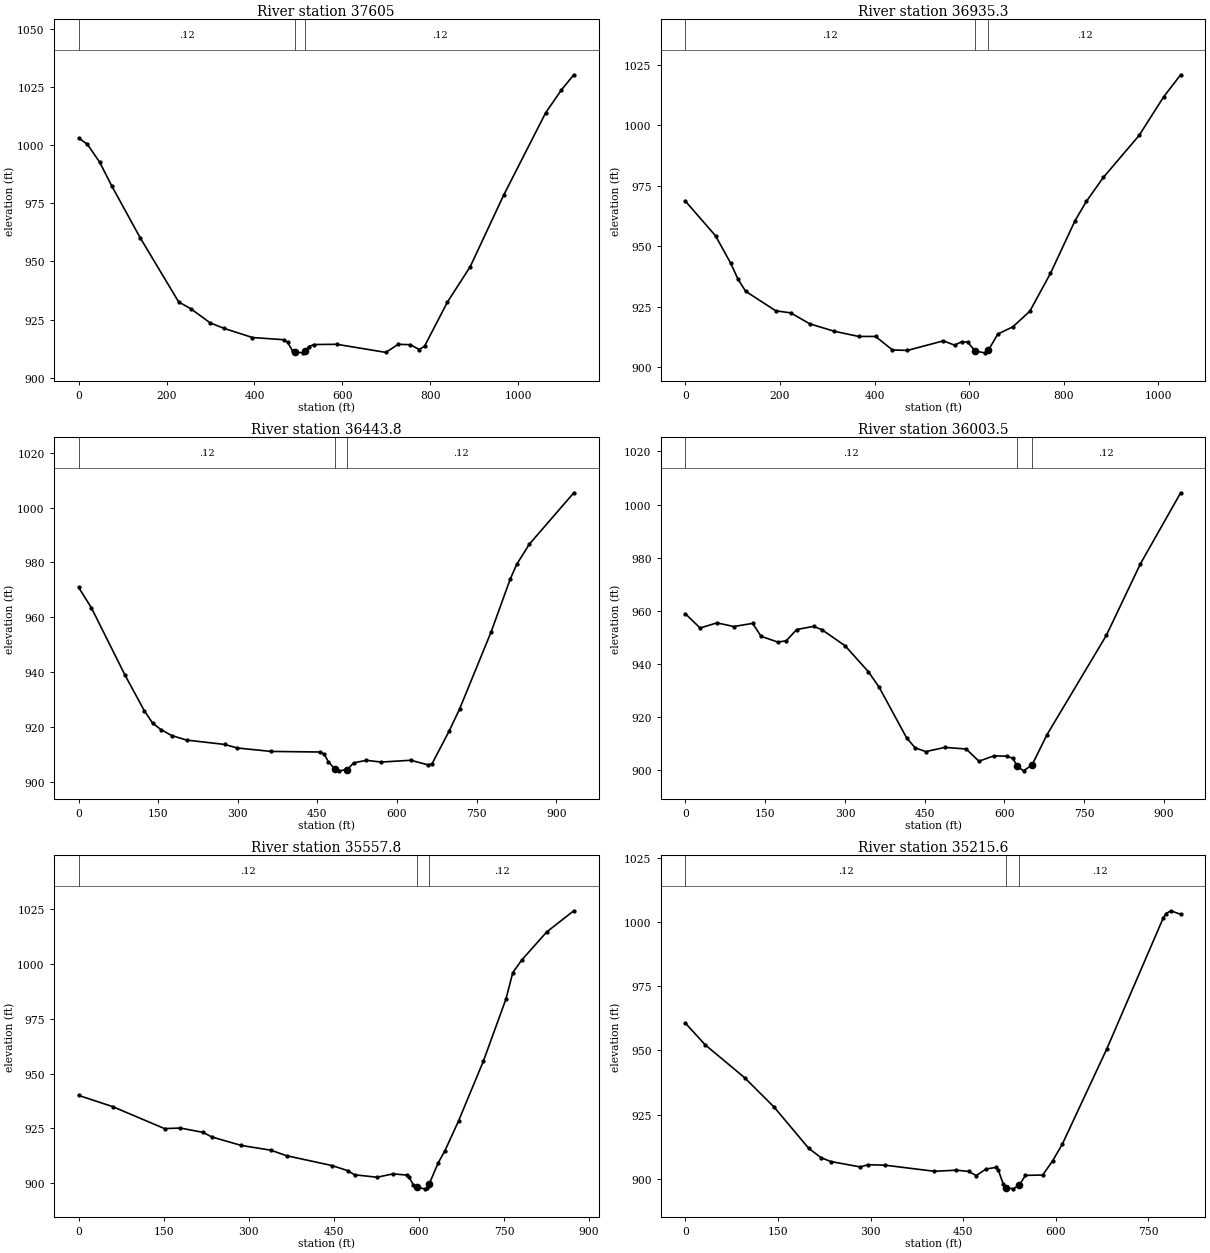
Type RM Length L Ch R = 1 ,37605   ,674.2,669.7,667.2
XS GIS Cut Line= 3
     2352627.909      390099.709     2353518.093      390072.749
     2353750.305      390032.001
#Sta/Elev= 30
       0 1003.14      20 1000.41    47.9  992.72    75.9  982.32   139.8  960.28
   227.6  932.58   255.6   929.6   299.5  923.55   331.5  921.17   395.4  917.27
   467.3  916.32   475.2  915.23   487.2  911.36   491.2  911.04   510.7  910.68
   515.2  911.31   523.2  913.32   535.2  914.25   587.1  914.36   698.9  910.87
   726.8  914.34   754.8  914.19   774.8   912.1   786.8  913.51   838.7  932.46
   890.6   947.7   966.5   978.4  1062.4 1013.98  1098.4 1023.87  1126.4 1030.34
#Mann= 3 ,-1 , 0
       0     .12       0   491.2    .045       0   515.2     .12       0
Bank Sta=491.2,515.2
XS Rating Curve= 0 ,0
Exp/Cntr=0.3,0.1

Type RM Length L Ch R = 1 ,36935.3 ,493.2,491.6,487.8
XS GIS Cut Line= 3
     2352777.139      390641.379     2353558.023      390535.422
     2353802.388      390448.667
#Sta/Elev= 30
       0  968.64    63.7   954.3    95.5  943.05   111.4  936.27   127.4  931.36
     191  923.31   222.9  922.45   262.7  917.94   314.4  914.87   366.2  912.71
     402  912.71   437.8  907.12   469.6  906.94   545.3  910.88   569.1  909.12
   585.1  910.57     597  910.32   612.9  906.67   632.8  905.93   640.8  907.06
   660.7  913.69   692.5   916.7   728.3  923.12   772.1  938.83   823.9  960.53
   847.9  968.55   883.8  978.45   959.6  995.86  1011.4 1011.78  1047.4 1020.92
#Mann= 3 ,-1 , 0
       0     .12       0   612.9    .045       0   640.8     .12       0
Bank Sta=612.9,640.8
XS Rating Curve= 0 ,0
Exp/Cntr=0.3,0.1

Type RM Length L Ch R = 1 ,36443.8 ,438.9,440.3,441.3
XS GIS Cut Line= 2
     2352888.326       391143.98     2353776.347      390857.521
#Sta/Elev= 30
       0  970.87    23.9  963.48    87.7  938.76   123.6  925.94   139.6   921.3
   155.5  918.95   175.4  916.82   203.4  915.17   275.1  913.58   299.1  912.28
   362.9  911.03   454.6  910.82   462.6  910.04   470.5  907.32   482.5  904.64
   490.5  903.95   506.4  904.43   518.4  906.86   542.3  907.79   570.2  907.15
     626  907.81   657.9  906.15   665.9  906.51   697.8  918.31   717.8  926.47
   777.6  954.77   813.4  973.95   825.4  979.22   849.3  986.62   933.1 1005.37
#Mann= 3 ,-1 , 0
       0     .12       0   482.5    .045       0   506.4     .12       0
Bank Sta=482.5,506.4
XS Rating Curve= 0 ,0
Exp/Cntr=0.3,0.1

Type RM Length L Ch R = 1 ,36003.5 ,440.9,445.7,450.5
XS GIS Cut Line= 3
     2352987.284      391375.751     2353265.055      391414.328
      2353890.93      391235.126
#Sta/Elev= 30
       0  958.91    27.6  953.58    59.2  955.51    90.8  954.14   126.4  955.32
   142.2  950.47   173.8  948.28   189.6  948.78   209.3  953.01   240.9   954.2
   256.7  952.95   300.4  946.88   344.3   937.1   364.3  931.32   416.2   912.2
   432.2  908.49   452.2  907.11   488.1  908.69   528.1  908.08     552  903.48
     580   905.5     604  905.38   615.9  904.59   623.9  901.64   635.9  899.87
   651.9  902.07   679.8  913.36   791.7  950.81   855.6  977.64   931.5 1004.43
#Mann= 3 ,-1 , 0
       0     .12       0   623.9    .045       0   651.9     .12       0
Bank Sta=623.9,651.9
XS Rating Curve= 0 ,0
Exp/Cntr=0.3,0.1

Type RM Length L Ch R = 1 ,35557.8 ,340.9,342.2,343.5
XS GIS Cut Line= 3
     2353130.513      391599.709     2353458.638      391763.771
     2353963.847      391729.917
#Sta/Elev= 30
       0  940.03    59.8  934.94   151.5  924.89   179.4  925.14   219.3  923.18
   235.3  921.04   287.1  917.19   338.9  915.04   366.8  912.52   446.6  908.05
   474.5  905.73   486.5  903.83   526.3  902.71   554.2  904.24   578.2  903.71
   582.2  902.97   590.1  899.31   596.8  898.11   610.1  897.42     614  897.73
     618  899.52     634  909.22   645.9  914.76   669.9  928.36   713.7  955.63
   753.6  984.02   765.6  996.02   781.5  1001.8   825.4 1014.57   873.2 1024.22
#Mann= 3 ,-1 , 0
       0     .12       0   596.8    .045       0     618     .12       0
Bank Sta=596.8,618
XS Rating Curve= 0 ,0
Exp/Cntr=0.3,0.1

Type RM Length L Ch R = 1 ,35215.6 ,532.4,533.3,531.5
XS GIS Cut Line= 2
     2353143.534      392091.896     2353945.617       392081.48
#Sta/Elev= 30
       0  960.61    31.9   952.2    95.8  939.41   143.7  927.94   199.5  911.98
   219.5   908.3   235.5  906.79   283.4  904.68   295.3  905.55   323.2  905.38
   403.1     903     439  903.42   458.9  902.95   470.9  901.32   486.9  903.87
   502.8  904.51   506.8  903.49   514.8  898.02   518.8  896.64   530.8  896.17
   540.8  897.58   550.7   901.4   578.7  901.55   594.6  906.98   610.6   913.6
   682.4  950.53   774.2 1001.65   778.2 1003.18   786.2 1004.33   802.2 1002.95
#Mann= 3 ,-1 , 0
       0     .12       0   518.8    .045       0   540.8     .12       0
Bank Sta=518.8,540.8
XS Rating Curve= 0 ,0
Exp/Cntr=0.3,0.1

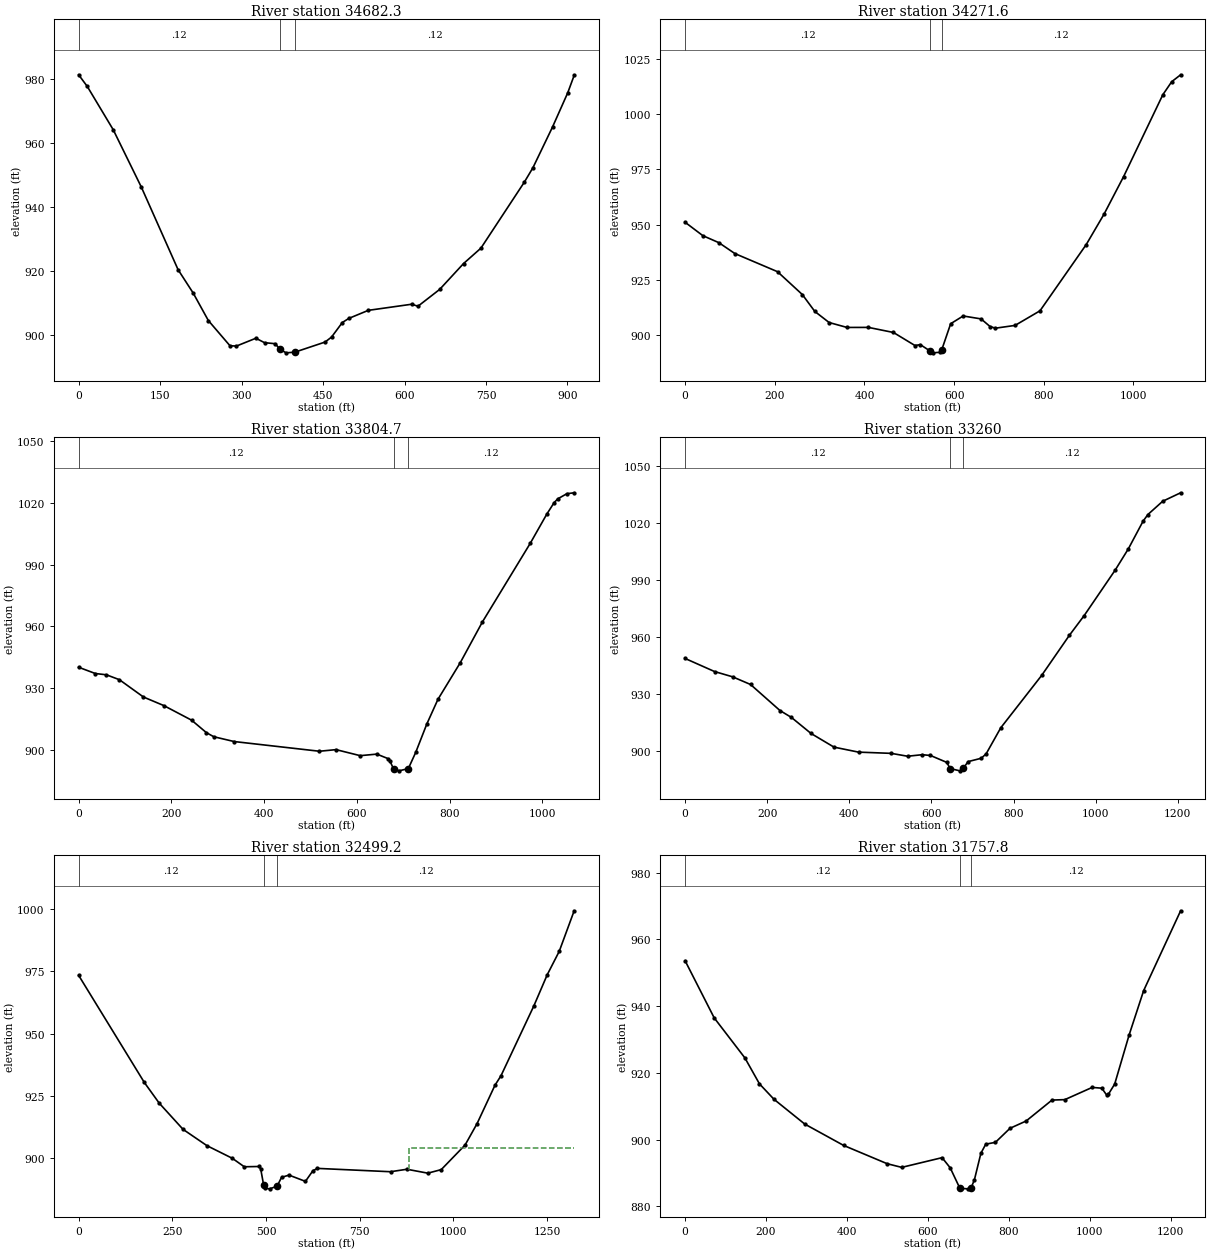
Type RM Length L Ch R = 1 ,34682.3 ,429,410.8,395
XS GIS Cut Line= 3
      2353066.27      392503.304     2353706.461      392529.346
     2353958.197      392631.342
#Sta/Elev= 30
       0   981.2    15.9  977.57    63.7  964.07   115.4  946.22   183.1  920.46
   210.9  913.18   238.8  904.62   278.6  896.76   290.5  896.66   326.3   899.1
   342.2  897.72   362.2  897.39   370.1   895.7     382  894.55     398  894.76
   453.7  897.91   465.6  899.46   485.5     904   497.4  905.28   533.3  907.79
   612.9  909.69   624.8  909.08   664.7  914.32   708.6  922.37   740.6  927.17
   820.5  947.73   836.4  952.24   872.4  964.91   900.4  975.56   912.3  981.02
#Mann= 3 ,-1 , 0
       0     .12       0   370.1    .045       0     398     .12       0
Bank Sta=370.1,398
XS Rating Curve= 0 ,0
Exp/Cntr=0.3,0.1

Type RM Length L Ch R = 1 ,34271.6 ,454.4,466.8,479.3
XS GIS Cut Line= 4
     2353060.201      393104.917      2353341.01      393035.422
     2353670.871      392740.283     2354044.135      392742.453
#Sta/Elev= 30
       0  951.04    39.6  944.97    75.3   941.8     111  936.87   206.1  928.66
   261.5   918.3   289.3  910.66   321.2  905.64   361.1  903.41   408.9  903.43
   464.7  901.13   512.6  895.23   524.6  895.63   546.5  892.72   552.5  891.91
   568.4  892.17   572.4  893.27   592.3   905.1   620.2   908.6   660.1  907.28
   680.1  903.83     692  903.07   735.9  904.33   791.5  910.94   894.7  940.96
   934.4  954.73   978.1  971.76  1065.5  1008.8  1085.3  1014.7  1105.2 1017.83
#Mann= 3 ,-1 , 0
       0     .12       0   546.5    .045       0   572.4     .12       0
Bank Sta=546.5,572.4
XS Rating Curve= 0 ,0
Exp/Cntr=0.3,0.1

Type RM Length L Ch R = 1 ,33804.7 ,538,544.7,551.4
XS GIS Cut Line= 3
     2353102.294      393354.433      2353979.03      393196.012
     2354152.642       393156.95
#Sta/Elev= 30
       0  940.23      36  937.19    59.9  936.57    87.9   934.2   139.8   925.8
   183.8  921.64   243.7  914.56   275.7   908.5   291.6  906.53   335.6   904.2
   519.4   899.5   555.3  900.28   607.3  897.36   643.2  898.11   667.2  895.95
   671.2  894.91   679.2  890.98   691.2     890   711.2  891.11   727.1  898.94
   751.1  912.74   775.1  924.69     823  942.36     871  962.22     974 1000.26
  1009.6 1014.38  1025.4 1019.97  1033.3 1021.86  1053.1 1024.38  1068.9 1024.83
#Mann= 3 ,-1 , 0
       0     .12       0   679.2    .045       0   711.2     .12       0
Bank Sta=679.2,711.2
XS Rating Curve= 0 ,0
Exp/Cntr=0.3,0.1

Type RM Length L Ch R = 1 ,33260   ,773.6,760.8,747.9
XS GIS Cut Line= 4
     2353113.145      393692.974     2353410.454      393723.356
     2353916.697      393783.399     2354298.041      393669.103
#Sta/Elev= 30
       0  948.64    71.7  941.74   115.6  938.96   159.4   934.9   231.1  921.14
     259   917.5   306.8  909.03   362.6  901.83   422.3  899.19     502  898.54
   541.8  897.02   577.6  897.83   597.6  897.42   637.4  893.76   645.4  890.52
   669.2  889.31   677.2  890.58   689.2  894.18     721  895.94     733  898.24
   768.8  912.05   868.4  939.71     936  960.91   971.9  971.29  1047.5  995.33
  1079.4  1006.5  1115.2 1021.08  1127.1 1024.64    1163 1031.63  1206.8 1036.12
#Mann= 3 ,-1 , 0
       0     .12       0   645.4    .045       0   677.2     .12       0
Bank Sta=645.4,677.2
XS Rating Curve= 0 ,0
Exp/Cntr=0.3,0.1

Type RM Length L Ch R = 1 ,32499.2 ,740.3,741.4,740.7
XS GIS Cut Line= 4
     2353137.017      394550.179     2353536.763      394505.959
     2354129.691      394232.384     2354351.867      394084.084
#Sta/Elev= 30
       0  973.43   175.2  930.45     215  922.13   278.7   911.6   342.4  905.06
   410.2  899.98     442  896.59   481.8   896.7   485.8  895.76   493.8  889.14
   497.8  887.98   509.7  887.73   529.6   888.8   541.5  892.35   561.4  893.24
   605.2  890.73   625.2  895.01   637.1  895.94   832.2   894.6     876  895.59
   931.8  894.02   967.6  895.45  1031.3  905.34  1063.2  913.92    1111  929.33
    1127  933.12  1214.7  961.16  1250.5   973.7  1282.4  983.06  1322.3  999.35
#Mann= 3 ,-1 , 0
       0     .12       0   493.8    .045       0   529.6     .12       0
#XS Ineff= 2 , 0
                          881.63             904
Permanent Ineff=
       F       F
Bank Sta=493.8,529.6
XS Rating Curve= 0 ,0
Exp/Cntr=0.3,0.1

Type RM Length L Ch R = 1 ,31757.8 ,701.3,683.8,668.5
XS GIS Cut Line= 3
     2353495.889      395266.379      2354278.51      394840.978
     2354497.694      394589.242
#Sta/Elev= 30
       0  953.61    71.9  936.49   147.8  924.49   183.8  916.72   219.7   912.1
   295.6  904.69   391.5   898.3   499.3  892.81   535.3  891.71   635.1  894.62
   655.1  891.58   679.1  885.43     699  885.28     707  885.63     715  888.01
     731  895.94     743  898.66   766.9  899.21   802.9  903.41   842.8   905.6
   906.7  911.87   938.4     912    1006  915.66  1029.8  915.43  1041.8  913.37
  1045.7  913.54  1061.6  916.66  1097.4  931.42  1133.2  944.66  1224.6  968.57
#Mann= 3 ,-1 , 0
       0     .12       0   679.1    .045       0     707     .12       0
Bank Sta=679.1,707
XS Rating Curve= 0 ,0
Exp/Cntr=0.3,0.1