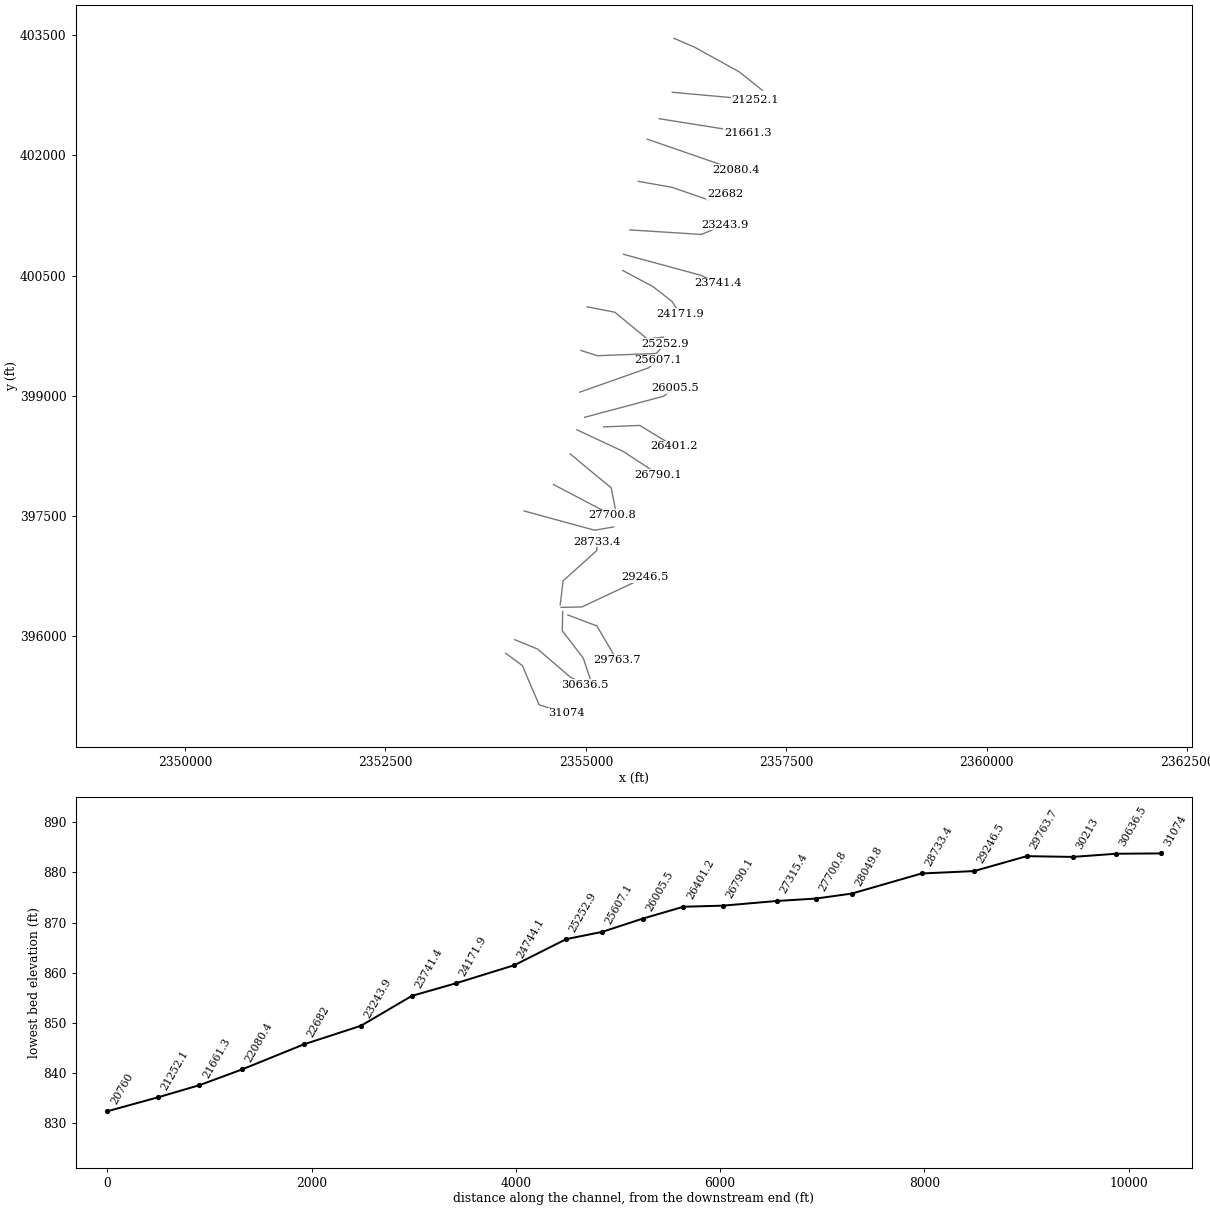
HEC-RAS study MEADOWBRCH.prj: MEADOWBRCH

--- MEADOWBRCH.g01 (geometry) --- (continued)

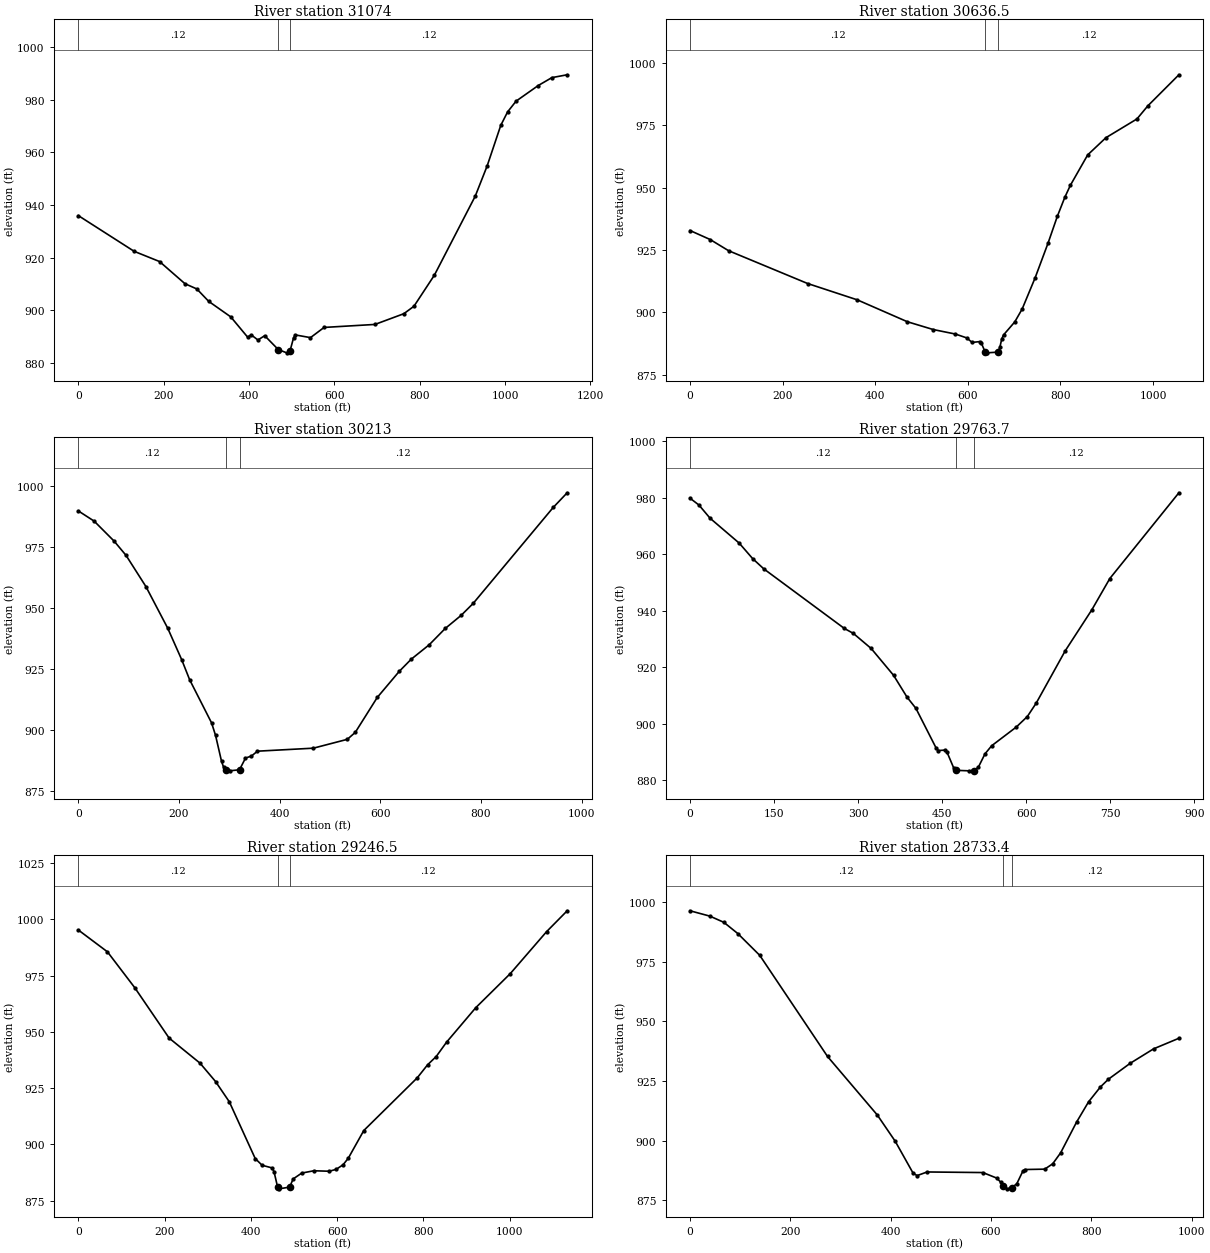
Type RM Length L Ch R = 1 ,31074   ,426.4,437.5,447.8
XS GIS Cut Line= 4
     2354000.305      395789.813     2354207.329      395636.117
     2354416.972      395146.584     2354755.513      395039.813
#Sta/Elev= 30
       0  935.94   130.9  922.36   190.4  918.48   249.9  910.06   277.7  908.07
   305.5  903.36   357.2  897.46   396.9  889.73   404.9  890.66   420.8  888.68
   436.7  890.31   468.5  885.05   488.3   883.8   496.3  884.68   504.2  889.44
   508.2  890.61     544  889.58   575.8  893.45     695  894.59   762.6  898.66
   786.4   901.5   834.2  913.29     930  943.33   957.9  954.81   989.8  970.22
  1005.8  975.33  1025.7  979.42  1077.6  985.35  1109.5  988.35  1145.4  989.43
#Mann= 3 ,-1 , 0
       0     .12       0   468.5    .045       0   496.3     .12       0
Bank Sta=468.5,496.3
XS Rating Curve= 0 ,0
Exp/Cntr=0.3,0.1

Type RM Length L Ch R = 1 ,30636.5 ,428.4,423.5,418.5
XS GIS Cut Line= 5
     2354112.284      395959.084     2354398.742      395841.896
     2354801.947      395495.058     2354806.457      395491.592
     2354992.492      395396.584
#Sta/Elev= 30
       0   932.8    43.6  929.18    83.3   924.7     254  911.54   361.5  904.97
   469.5   896.2   525.4  893.07   573.4  891.26   597.4  889.74   609.4   887.9
   625.4  888.24   629.4  887.57   637.4   884.1   641.4  883.73   665.4  884.02
   669.4   886.1   673.4  889.36   677.4  890.97   701.4  896.13   717.4  901.31
   745.4  913.83   773.4  927.79   793.4  938.51   809.4  946.07   821.4   950.9
   858.9  963.13   898.3  970.03   965.3  977.55   988.9  982.82  1055.9  995.27
#Mann= 3 ,-1 , 0
       0     .12       0   637.4    .045       0   665.4     .12       0
Bank Sta=637.4,665.4
XS Rating Curve= 0 ,0
Exp/Cntr=0.3,0.1

Type RM Length L Ch R = 1 ,30213   ,451.6,449.2,446.6
XS GIS Cut Line= 4
     2354710.367      396310.162     2354706.027      396069.276
     2354967.132       395729.84     2355062.805      395443.459
#Sta/Elev= 30
       0  989.67    31.6  985.46    71.1  977.29    94.8  971.45   134.3  958.65
   177.7  941.54   205.4  928.66   221.2  920.44   264.7  902.77   272.6  897.67
   284.5  887.01   288.5  884.63   292.5  883.42   300.4   883.1   320.2  883.54
   332.1  888.33     344  889.18   355.9  891.16   466.9  892.39   534.4  896.02
   550.2  898.88   593.8  913.18   637.4  923.86   661.2  928.85     697  934.78
   728.8  941.46   760.5  946.85   784.4  951.75   943.3  991.08   971.1   997.1
#Mann= 3 ,-1 , 0
       0     .12       0   292.5    .045       0   320.2     .12       0
Bank Sta=292.5,320.2
XS Rating Curve= 0 ,0
Exp/Cntr=0.3,0.1

Type RM Length L Ch R = 1 ,29763.7 ,484.2,517.3,550.5
XS GIS Cut Line= 3
     2354775.471      396266.759     2355137.885       396130.04
      2355383.11      395711.203
#Sta/Elev= 30
       0  979.86      16  977.42    35.9  972.74    87.8  963.94   111.8  958.45
   131.8   954.8   275.5   933.7   291.5  931.96   323.4   926.6   363.4  917.09
   387.3  909.39   403.3  905.38   439.1  891.42     443  890.44     455   890.6
     459  889.76   470.9  884.19   474.9  883.43   498.7  883.25   506.7  883.34
   514.6  884.49   526.6  889.28   538.5  892.14   582.3  898.74   602.2   902.5
   618.1  907.28   669.8  925.78   717.5  940.37   749.4  951.39   872.7  981.77
#Mann= 3 ,-1 , 0
       0     .12       0   474.9    .045       0   506.7     .12       0
Bank Sta=474.9,506.7
XS Rating Curve= 0 ,0
Exp/Cntr=0.3,0.1

Type RM Length L Ch R = 1 ,29246.5 ,506.8,513,519.3
XS GIS Cut Line= 3
     2354690.836      396362.245     2354949.082      396366.585
     2355741.332       396738.88
#Sta/Elev= 30
       0  995.28    67.6  985.57   131.1  969.59   210.6  947.25   282.3   936.1
   318.2  927.96   350.2  918.93   410.2  893.74   426.2  890.74   450.1  889.53
   454.1  887.68   462.1  881.08   466.1  880.27   490.1  881.06   498.1  884.66
   518.1  887.27   546.1   888.3     582  888.09     598  888.94     614  890.98
     626  893.87     662  906.18   785.9  929.59   809.9  935.38   829.9  939.06
   853.8  945.41   921.8  960.79  1001.7   975.9  1085.7  994.51  1133.6 1003.81
#Mann= 3 ,-1 , 0
       0     .12       0   462.1    .045       0   490.1     .12       0
Bank Sta=462.1,490.1
XS Rating Curve= 0 ,0
Exp/Cntr=0.3,0.1

Type RM Length L Ch R = 1 ,28733.4 ,707.4,683.6,659.7
XS GIS Cut Line= 4
     2354679.851      396393.253     2354715.878      396692.973
     2355135.714       397069.71     2355140.055      397178.217
#Sta/Elev= 30
       0  996.45    39.7   994.2    67.5   991.6    95.3  986.89     139  977.76
   274.1  935.34   373.4  910.76   409.1  899.75   444.9  886.31   452.8  885.35
   472.7  886.87   583.9  886.62   611.7  884.28   619.7  882.48   623.6  880.85
   631.6  879.79   641.1  880.29   651.4   881.9   663.4  887.16   667.3  887.89
   707.1  888.05     723  890.29   738.8  894.88   770.6  907.78   794.5  916.28
   818.3  922.57   834.2   925.8   877.6  932.47   924.1  938.52   974.6  942.96
#Mann= 3 ,-1 , 0
       0     .12       0   623.6    .045       0   641.1     .12       0
Bank Sta=623.6,641.1
XS Rating Curve= 0 ,0
Exp/Cntr=0.3,0.1

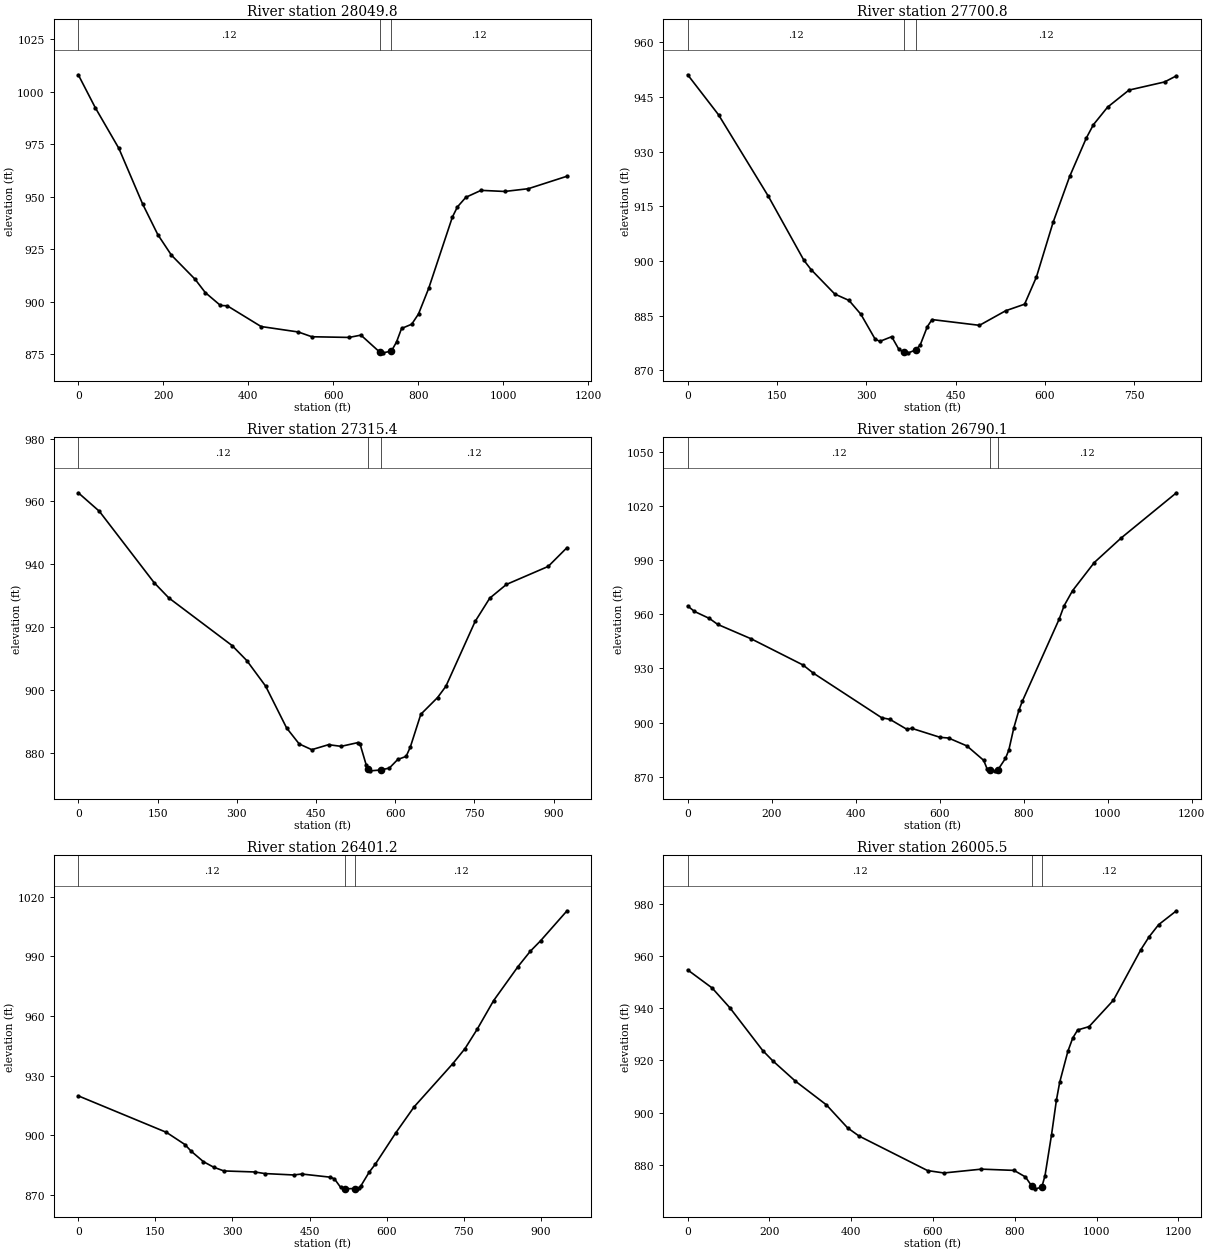
Type RM Length L Ch R = 1 ,28049.8 ,353.9,349,344.2
XS GIS Cut Line= 3
     2354229.765       397564.26      2355109.68      397323.667
     2355344.048      397364.849
#Sta/Elev= 30
       0 1008.18    39.8  992.58    95.6  973.09   151.4  946.66   187.2  932.05
   219.1  922.31   274.9  910.81   298.8  904.49   334.6  898.34   350.6  898.18
   430.2  888.31   517.8  885.71   549.7  883.44   637.4  883.12   665.2  884.22
   709.1  876.18     717  875.78   736.9  876.62   748.9  880.93   760.8  887.38
   784.7  889.42   800.7   894.3   824.6  906.46   880.4  940.42   892.3  945.28
   912.2  949.85   947.9  953.15  1003.4  952.62    1059  953.93  1150.2  959.88
#Mann= 3 ,-1 , 0
       0     .12       0   709.1    .045       0   736.9     .12       0
Bank Sta=709.1,736.9
XS Rating Curve= 0 ,0
Exp/Cntr=0.3,0.1

Type RM Length L Ch R = 1 ,27700.8 ,389.7,385.3,381
XS GIS Cut Line= 2
      2354595.35      397894.363     2355322.346      397512.419
#Sta/Elev= 30
       0  951.09    51.8  940.12   135.5  917.76   195.3  900.18   207.3  897.64
   247.2  890.92   271.1  889.17     291  885.38   314.9  878.57   322.9  877.94
   342.8  879.22   354.8  875.76   362.8  874.99   370.8  874.79   383.3  875.59
   390.7  876.94   402.6  881.96   410.6  883.92   490.3  882.34   534.2  886.33
   566.1  888.14     586  895.61   613.9  910.56   641.8  923.18   669.7   933.7
   681.7  937.39   705.6  942.22   741.5  946.89   801.3  949.12   821.2   950.8
#Mann= 3 ,-1 , 0
       0     .12       0   362.8    .045       0   383.3     .12       0
Bank Sta=362.8,383.3
XS Rating Curve= 0 ,0
Exp/Cntr=0.3,0.1

Type RM Length L Ch R = 1 ,27315.4 ,521.4,525.3,528.5
XS GIS Cut Line= 4
     2354803.683      398276.308     2355048.909      398072.315
     2355315.836      397853.131     2355365.749      397597.054
#Sta/Elev= 30
       0  962.74    39.9  956.85   143.5  934.17   171.4   929.3   291.1  914.16
     319  909.38   354.7  901.24   394.4  887.94   418.2  882.86     442  881.03
   473.8  882.62   497.6  882.09   529.4  883.28   533.4  882.84   545.3  876.06
   549.2   874.9   553.2   874.3   572.5  874.57   588.9  875.18   604.8  877.91
   620.7   878.9   628.6  881.86   648.5  892.29   680.2  897.61     696   901.2
   751.3  921.81     779  929.22   810.6  933.59   889.7  939.32   925.3   945.3
#Mann= 3 ,-1 , 0
       0     .12       0   549.2    .045       0   572.5     .12       0
Bank Sta=549.2,572.5
XS Rating Curve= 0 ,0
Exp/Cntr=0.3,0.1

Type RM Length L Ch R = 1 ,26790.1 ,388.1,388.9,389.6
XS GIS Cut Line= 3
     2354888.319      398575.787     2355465.576       398306.69
     2355906.114      398018.061
#Sta/Elev= 30
       0   964.6    15.9  961.59    51.8  957.67    71.6  954.38   151.3   946.4
   274.7  931.92   298.6  927.52   461.8  902.76   481.6  901.85   521.5  896.39
   533.4  896.89   601.1   891.9     621  891.53   664.8  887.16   704.7  879.18
   712.7  874.57   720.7  873.69   732.7  873.37     739  874.09   756.6  880.26
   764.6  884.88   776.5  897.16   788.5  906.84   796.5  911.74   884.3  957.24
   896.2  964.71   916.2  973.01   968.1  988.64  1031.9 1002.18  1163.6 1027.22
#Mann= 3 ,-1 , 0
       0     .12       0   720.7    .045       0     739     .12       0
Bank Sta=720.7,739
XS Rating Curve= 0 ,0
Exp/Cntr=0.3,0.1

Type RM Length L Ch R = 1 ,26401.2 ,377.4,395.7,414.1
XS GIS Cut Line= 3
     2355221.659       398612.73      2355672.18      398630.959
     2356099.263      398370.542
#Sta/Elev= 30
       0  919.88   171.6  901.53   207.5  895.42   219.5  892.11   243.4  886.83
   263.4  884.03   283.3  882.15   343.2  881.63   363.1  880.83     419  880.12
   434.9   880.6   490.6     879   498.5  878.16   510.4  873.93   518.4  873.15
   538.8  873.32   546.2  873.71   550.1   874.7     566   881.5   577.9   885.5
   617.6  901.19   653.4  914.32   728.8  936.06   752.6  943.64   776.4  953.42
   808.2  967.74   855.8  984.88   879.6  992.55   899.5  997.78   951.1  1012.9
#Mann= 3 ,-1 , 0
       0     .12       0   518.4    .045       0   538.8     .12       0
Bank Sta=518.4,538.8
XS Rating Curve= 0 ,0
Exp/Cntr=0.3,0.1

Type RM Length L Ch R = 1 ,26005.5 ,397,398.4,399.8
XS GIS Cut Line= 3
     2354983.805      398732.037     2355966.878      398994.624
     2356112.277       399096.62
#Sta/Elev= 30
       0   954.7    59.9  947.76   103.8  940.07   183.6  923.78   207.5  919.95
   263.4  912.07   339.2  902.99     391  894.18     419  891.04   586.6   877.8
   626.5  876.88   718.3  878.35   798.1  877.87     826  875.36     842  871.76
   849.9   870.8   865.9  871.42   873.9   875.9   889.8  891.53   901.8  904.86
   909.8  911.67   929.8  923.53   941.7  928.61   953.7  931.68   981.6  932.97
  1041.2   943.1  1108.3  962.48    1128   967.3  1151.7  972.04  1195.2  977.36
#Mann= 3 ,-1 , 0
       0     .12       0     842    .045       0   865.9     .12       0
Bank Sta=842,865.9
XS Rating Curve= 0 ,0
Exp/Cntr=0.3,0.1

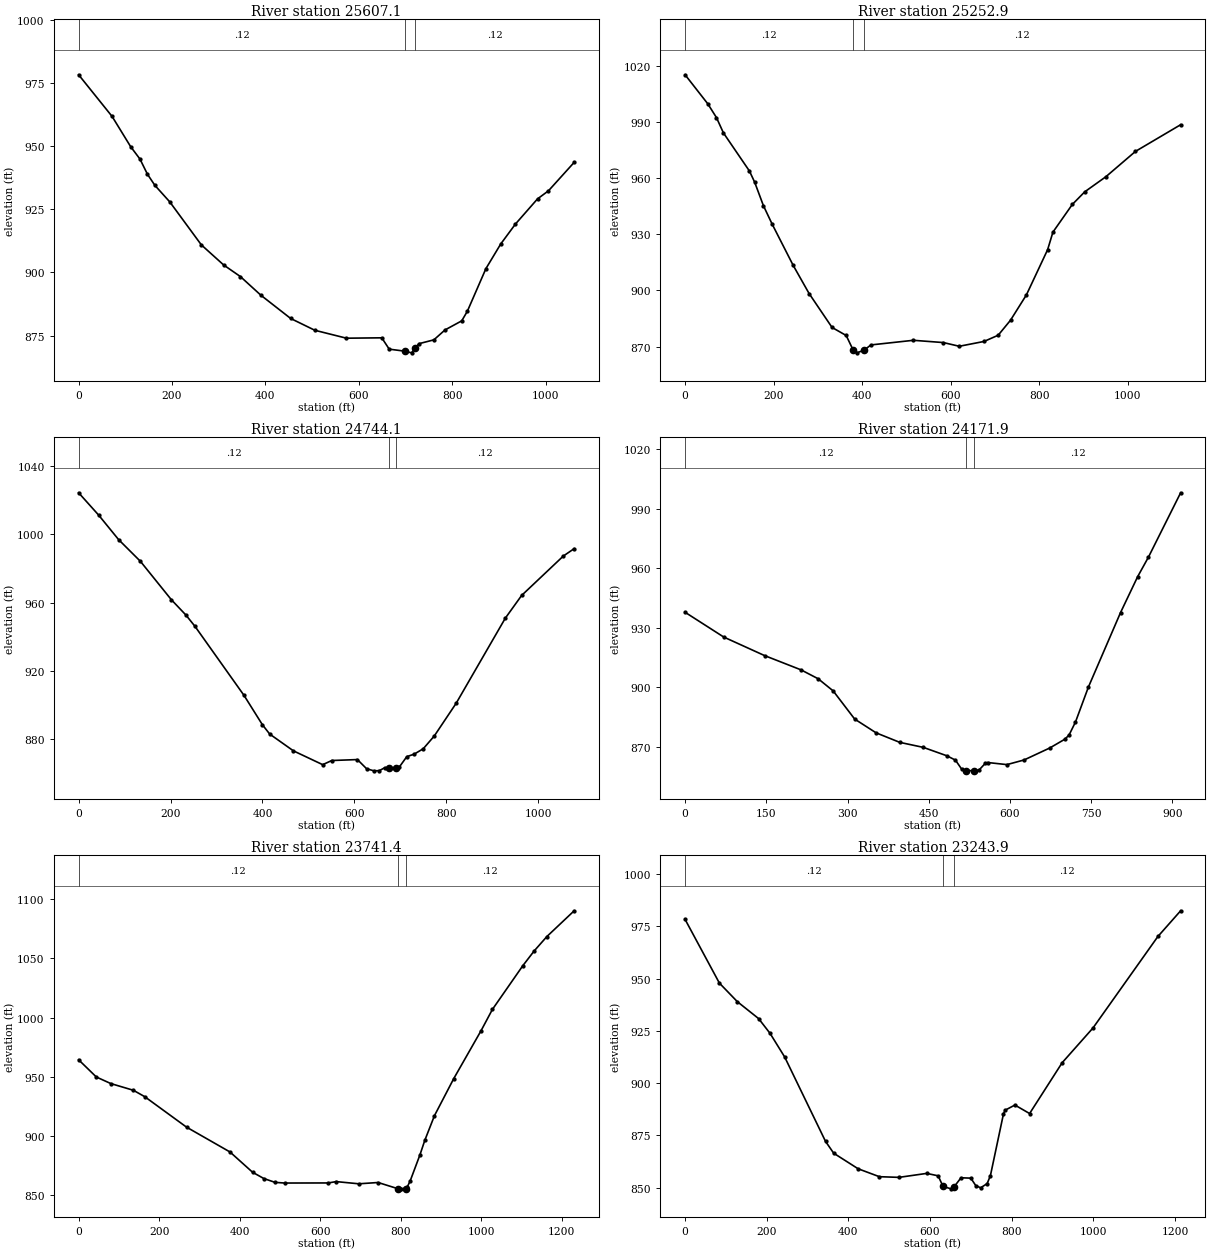
Type RM Length L Ch R = 1 ,25607.1 ,362,354.2,346.4
XS GIS Cut Line= 3
     2354924.118      399045.779     2355780.246      399348.356
     2355901.773      399441.672
#Sta/Elev= 30
       0  978.28    71.7  961.77   111.5  949.78   131.4  944.88   147.4  938.88
   163.3  934.48   195.2  927.93   262.8   910.9   310.6  902.94   346.5  898.34
   390.3  890.96     454  881.76   505.8  877.08   573.5  873.94   649.2  874.09
   665.1   869.6   698.6   868.8   712.9  868.14   720.8  870.06   728.8  871.77
   760.7  873.28   784.6  877.21   820.4  880.81   832.4   884.6   872.2   901.5
     904  911.28   935.5  919.17   982.7  929.12  1006.2  932.33  1061.2  943.59
#Mann= 3 ,-1 , 0
       0     .12       0   698.6    .045       0   720.8     .12       0
Bank Sta=698.6,720.8
XS Rating Curve= 0 ,0
Exp/Cntr=0.3,0.1

Type RM Length L Ch R = 1 ,25252.9 ,525.2,508.8,492.5
XS GIS Cut Line= 4
     2354938.232       399565.37     2355144.395      399500.266
     2355878.064      399528.617     2355992.919      399652.176
#Sta/Elev= 30
       0 1015.28    51.1  999.81    70.8  992.42    86.5  984.24   145.4  963.81
   157.2  957.82   176.9  945.31   196.5  935.51   244.1  913.42     280  898.39
   331.9  880.24   363.8  875.95   379.8  868.04   387.8  866.68     404  868.09
   419.7  870.91   515.5  873.38   583.3  872.17   619.2  870.19   675.1  872.77
     707  876.08   734.9  884.11   770.8  897.65   818.7  921.81   830.7   931.2
   874.6  946.02   902.5  952.72   950.4  960.82  1017.1  974.34  1119.1  988.59
#Mann= 3 ,-1 , 0
       0     .12       0   379.8    .045       0     404     .12       0
Bank Sta=379.8,404
XS Rating Curve= 0 ,0
Exp/Cntr=0.3,0.1

Type RM Length L Ch R = 1 ,24744.1 ,571.3,572.1,572.9
XS GIS Cut Line= 4
     2355016.357      400110.075     2355361.789       400042.33
     2355767.225      399708.599     2355966.878      399732.471
#Sta/Elev= 30
       0 1024.36    43.5  1011.3      87  996.92   134.5  984.18   201.7  961.73
   233.4  952.74   253.1  946.14     360  905.61   399.8   888.5   415.7  883.02
   467.4  873.17     531  865.09   550.9  867.52   606.6  868.07   626.5  862.72
   642.4  861.47   654.4  861.59   666.3  863.36   676.2  862.85   691.2  862.97
   698.1  863.84     714  869.79   729.9  871.23   749.8   874.4   773.7  881.84
   821.4  901.04   928.4  950.91   963.9  964.22  1054.6   987.3  1078.2  991.63
#Mann= 3 ,-1 , 0
       0     .12       0   676.2    .045       0   691.2     .12       0
Bank Sta=676.2,691.2
XS Rating Curve= 0 ,0
Exp/Cntr=0.3,0.1

Type RM Length L Ch R = 1 ,24171.9 ,421.6,430.5,439.4
XS GIS Cut Line= 4
     2355459.065      400563.634     2355836.669      400361.811
     2356071.044      400179.519     2356179.551      400023.269
#Sta/Elev= 30
       0  937.81    71.4  925.32   146.7  915.99   214.1  908.78   245.8  904.29
   273.5  898.17   313.2  883.97   352.8  877.02   396.4  872.23     440  869.69
   483.6  865.44   499.4  863.25   511.3  858.54   519.2  858.02   534.2  857.88
     535  857.86     543  858.28   554.8  861.74   558.8  862.06   594.4     861
   626.1  863.34   673.6  869.39   701.3  873.79   709.2  875.91   721.1   882.5
   744.9  900.08   804.3  937.67     836  955.82   855.9  965.65   915.3  998.07
#Mann= 3 ,-1 , 0
       0     .12       0   519.2    .045       0   534.2     .12       0
Bank Sta=519.2,534.2
XS Rating Curve= 0 ,0
Exp/Cntr=0.3,0.1

Type RM Length L Ch R = 1 ,23741.4 ,492.7,497.5,502.3
XS GIS Cut Line= 3
     2355470.817      400764.773     2356435.628       400502.87
     2356643.961      400403.044
#Sta/Elev= 30
       0  964.36      44  949.82      80  944.27     136   938.6     164  933.24
   267.9  907.49   375.9  886.49   431.9  869.39   459.9  864.07   487.9  860.81
   511.9  860.25   619.8  860.33   639.8  861.46   695.8  859.61   743.8   860.7
   792.8  855.47   799.8  855.35   811.8  855.63   815.8  856.65   823.8  862.37
   847.8  884.18   859.8  896.38   883.8  917.22   931.7  948.53   999.7  989.09
  1027.6  1006.9  1103.3 1043.91  1131.2 1056.24    1163 1068.51  1230.7 1090.24
#Mann= 3 ,-1 , 0
       0     .12       0   792.8    .045       0   811.8     .12       0
Bank Sta=792.8,811.8
XS Rating Curve= 0 ,0
Exp/Cntr=0.3,0.1

Type RM Length L Ch R = 1 ,23243.9 ,568.6,561.9,555.2
XS GIS Cut Line= 3
     2355548.041      401069.276     2356442.138      401012.853
     2356735.107      401136.551
#Sta/Elev= 30
       0  978.29      84  947.83     128  938.94     180  930.86     208  923.81
     244  912.45     344   872.1     364  866.44   423.9  858.99   475.9   855.2
   523.9  854.88   591.9  856.78   619.9  855.62   631.9  850.52   651.9  849.39
   658.3  850.21   675.9  854.68   699.9  854.51   711.9  850.98   723.9  849.88
   739.9   851.9   747.9   855.7   779.9  885.25   783.9  887.02   807.9  889.48
   843.9  885.42   923.7  909.74   999.2  926.36  1158.2  970.13  1213.9  982.43
#Mann= 3 ,-1 , 0
       0     .12       0   631.9    .045       0   658.3     .12       0
Bank Sta=631.9,658.3
XS Rating Curve= 0 ,0
Exp/Cntr=0.3,0.1

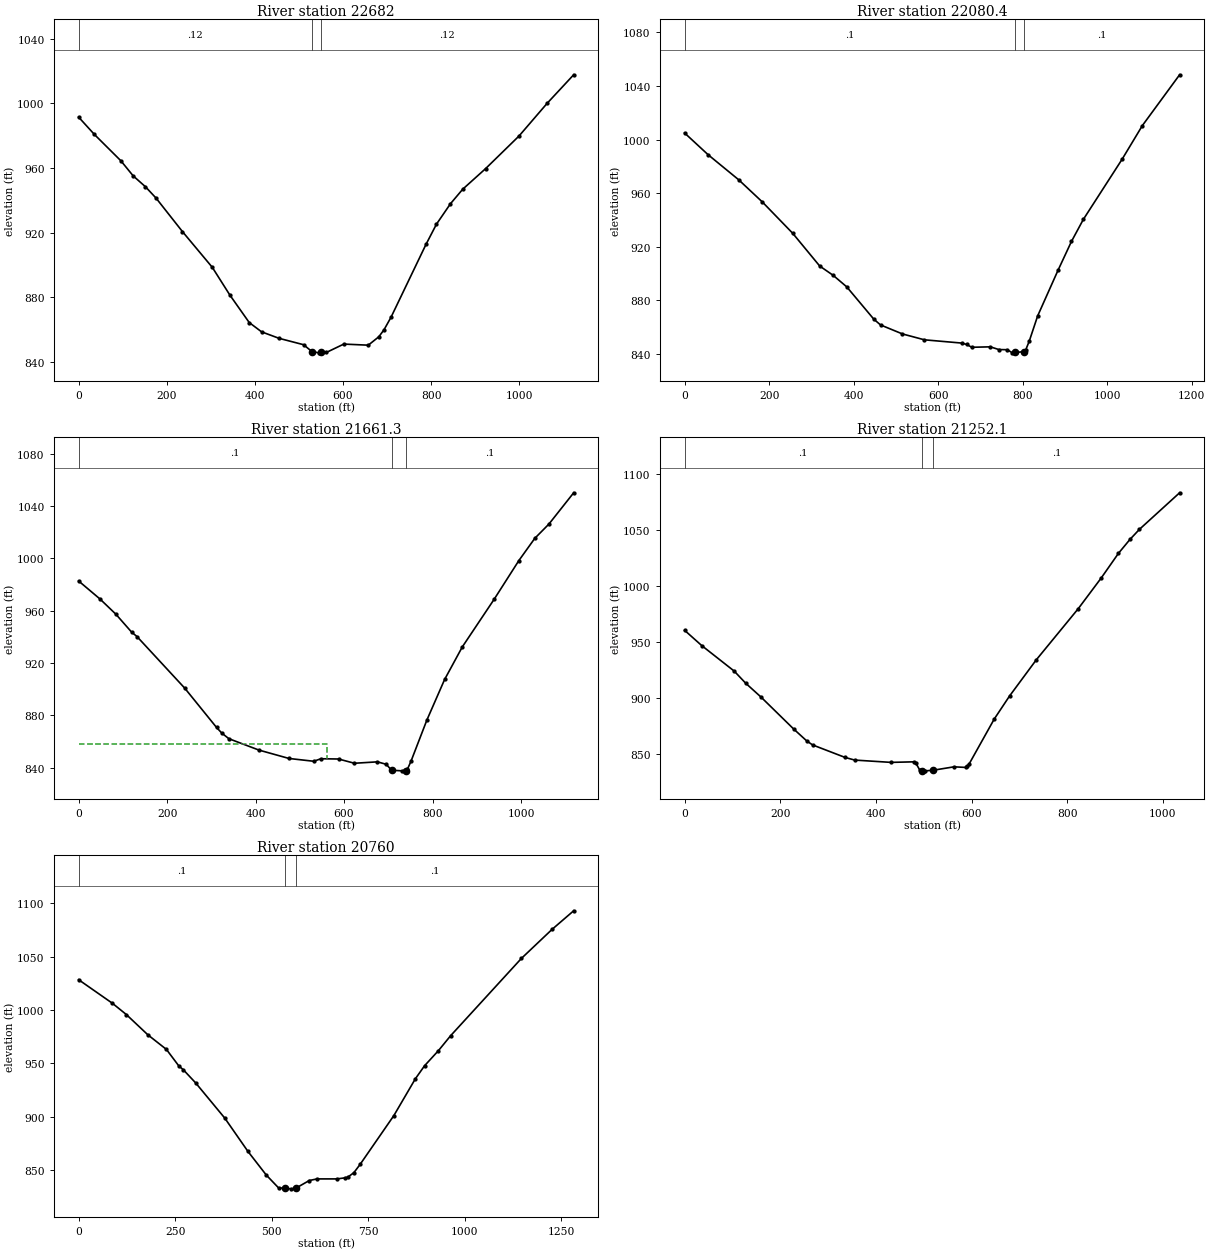
Type RM Length L Ch R = 1 ,22682   ,596.9,601.6,602.6
XS GIS Cut Line= 4
     2355654.378      401674.745     2356071.044       401600.96
     2356521.647      401446.579     2356735.107      401514.155
#Sta/Elev= 30
       0  991.56    35.9  980.81    95.8  964.56   123.8   955.2   151.7  948.45
   175.6  941.48   235.5  920.75   303.4  898.57   343.3  881.39   387.2   864.4
   415.2  858.66   454.9  854.64   510.5  850.69   529.8  846.37   546.2  845.66
   550.2  845.93   562.1  845.89   601.8  851.08   657.3   850.4   681.2  855.59
   693.1  859.96   708.9  867.67   788.3  912.79   812.1  925.31   843.9  937.97
   871.7  946.95   923.4  959.64   999.4  979.87  1063.4 1000.16  1123.4 1017.76
#Mann= 3 ,-1 , 0
       0     .12       0   529.8    .045       0   550.2     .12       0
Bank Sta=529.8,550.2
XS Rating Curve= 0 ,0
Exp/Cntr=0.3,0.1

Type RM Length L Ch R = 1 ,22080.4 ,415.1,419.1,423.1
XS GIS Cut Line= 2
     2355764.894      402201.068     2356871.826      401817.974
#Sta/Elev= 30
       0 1004.91      56  988.57   127.9  969.98   183.9  953.41   255.9  929.97
   319.8  905.51   351.8  898.53   383.8  889.95   447.8  865.83   463.7  861.52
   515.7  854.78   567.7   850.4   655.6  847.98   667.6  846.93   679.6  844.83
   723.6  845.17   743.6  843.14   763.6  843.01   775.6  840.68     781  840.94
   803.6  841.55   807.6  843.13   815.6  849.38   835.5  868.24   883.5  902.19
   915.5  923.86   943.5  940.28  1035.4  985.29  1083.4 1010.46  1171.4 1048.34
#Mann= 3 , 0 , 0
       0      .1       0     781    .045       0   803.6      .1       0
Bank Sta=781,803.6
XS Rating Curve= 0 ,0
Exp/Cntr=0.3,0.1

Type RM Length L Ch R = 1 ,21661.3 ,407.7,409.2,410.7
XS GIS Cut Line= 2
      2355914.25      402456.094     2357019.395      402280.214
#Sta/Elev= 30
       0  982.77      48  969.08    83.9  957.47   119.9   943.6   131.9  940.27
   239.8   900.8   311.7  870.74   323.7  866.38   339.7   862.1   407.7  853.39
   475.6  846.98   531.6  844.84   547.5  846.77   587.5  846.57   623.5  843.32
   675.4   844.4   695.4  842.52   707.4  837.96   731.4  837.52   739.4  837.67
   743.4  838.87   751.4  844.93   787.3  876.45   827.3  907.42   867.3  932.34
   939.2  968.74   995.2  998.42  1031.1 1015.37  1063.1 1026.32    1119 1050.24
#Mann= 3 , 0 , 0
       0      .1       0   707.4    .045       0   739.4      .1       0
#XS Ineff= 2 , 0
          561.67  858.21
Permanent Ineff=
       F       F
Bank Sta=707.4,739.4
XS Rating Curve= 0 ,0
Exp/Cntr=0.3,0.1

Type RM Length L Ch R = 1 ,21252.1 ,502.7,492.1,481.2
XS GIS Cut Line= 2
     2356077.555      402785.856     2357108.371       402692.54
#Sta/Elev= 30
       0   960.7      36  946.99   103.9  924.18   127.9  913.36   159.8  901.03
   227.8   872.6   255.8  861.68   267.8  858.22   335.7  847.05   355.7   844.7
   431.6  842.64   479.6  843.13   483.6  841.97   491.5  835.95   495.5  835.18
   503.5  835.08   519.5   835.6   563.5  838.67   587.4  838.14   591.4  839.31
   595.4  841.55   647.4  881.33   679.4  901.91   735.3  934.25   823.2  980.05
   871.2 1007.47   907.2 1029.48   931.1 1041.83   951.1 1050.92    1035 1083.56
#Mann= 3 , 0 , 0
       0      .1       0   495.5    .045       0   519.5      .1       0
Bank Sta=495.5,519.5
XS Rating Curve= 0 ,0
Exp/Cntr=0.3,0.1

Type RM Length L Ch R = 1 ,20760   ,532.2,523.2,514.4
XS GIS Cut Line= 4
     2356098.776      403458.442     2356355.332      403347.922
      2356913.13      403040.298     2357199.517      402811.898
#Sta/Elev= 30
       0 1028.51    87.8 1006.33   123.7  995.81   179.6  976.75   227.5  963.12
   259.4  947.74   271.4  943.98   303.2  931.73   378.9  898.58   438.6   867.5
   486.4  845.21   518.2  833.18   534.2  832.94   550.1  832.32     562  832.77
   597.8  840.14   617.8  841.63   669.5  841.64   689.4  842.59   697.4  843.24
   713.3  847.53   729.2  855.16   816.8  901.04   872.6   935.6   896.4   947.8
   932.3  961.96   964.1  976.05  1147.3 1048.48  1226.9 1075.77  1282.7 1093.16
#Mann= 3 , 0 , 0
       0      .1       0   534.2    .045       0     562      .1       0
Bank Sta=534.2,562
XS Rating Curve= 0 ,0
Exp/Cntr=0.3,0.1