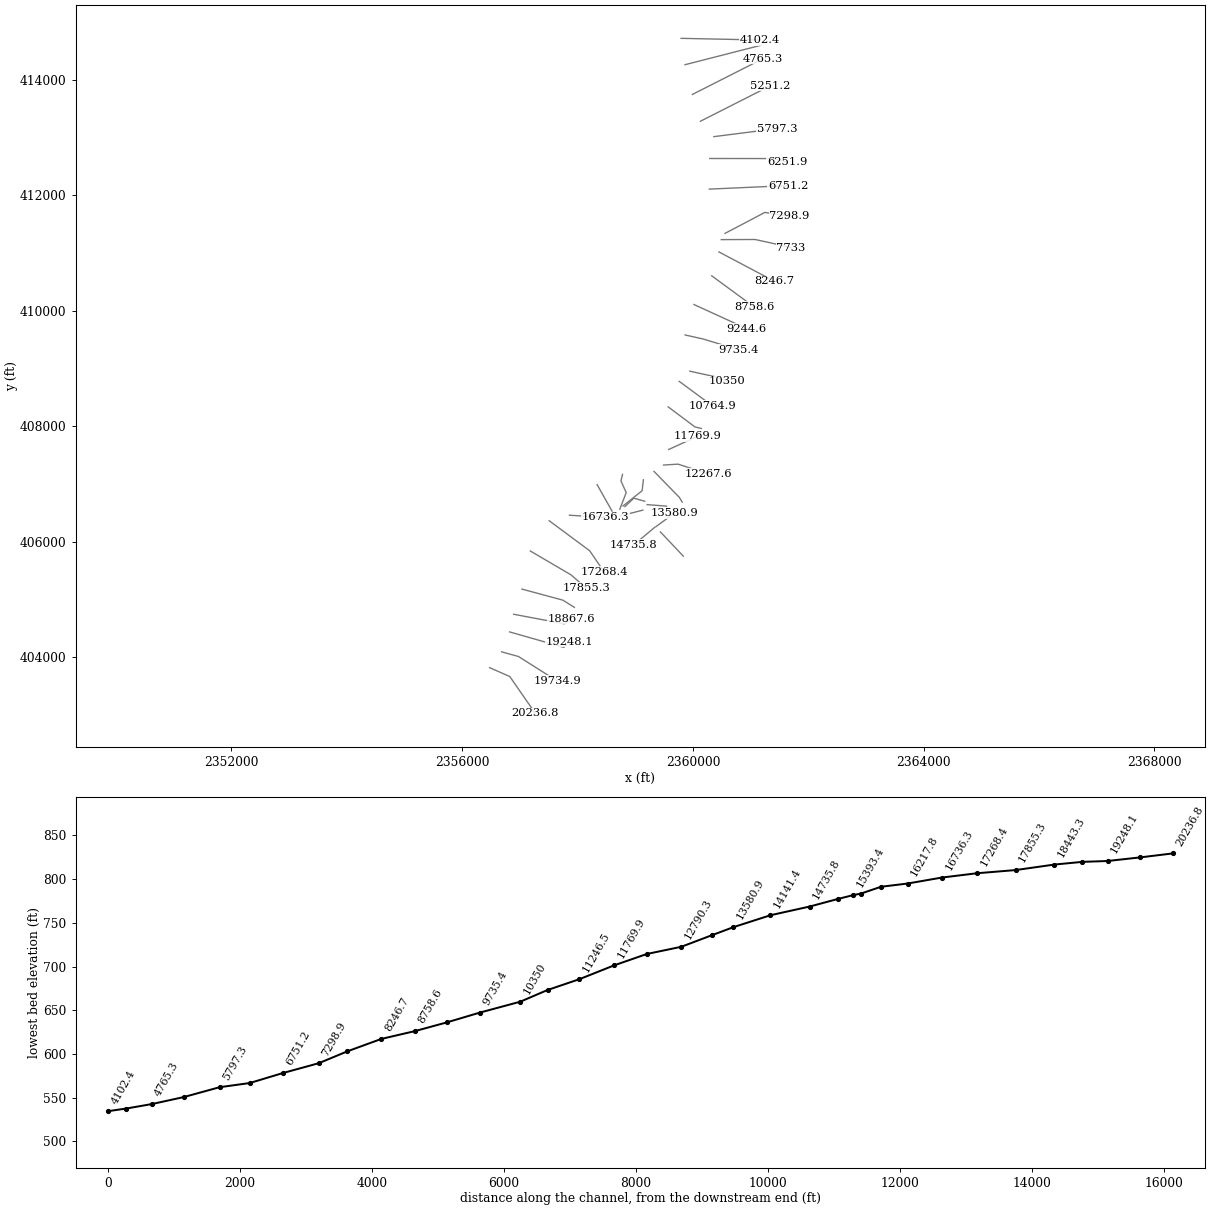
HEC-RAS study MEADOWBRCH.prj: MEADOWBRCH

--- MEADOWBRCH.g01 (geometry) --- (continued)

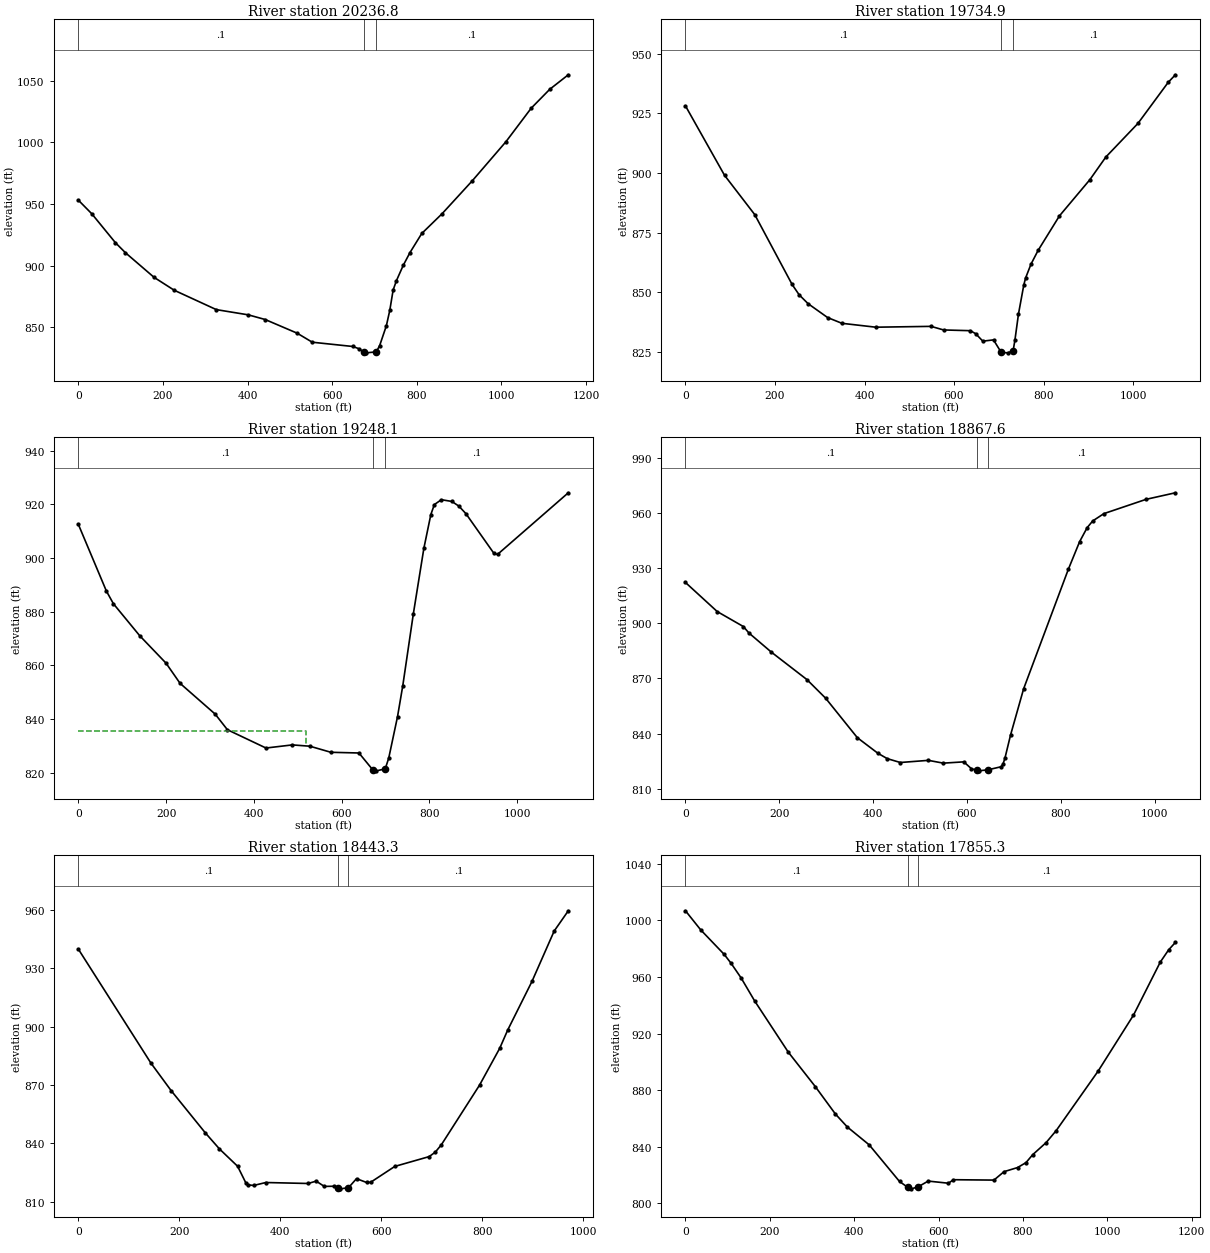
Type RM Length L Ch R = 1 ,20236.8 ,492.7,501.9,510.9
XS GIS Cut Line= 3
      2356476.86      403816.672     2356826.253      403662.592
     2357268.961      403024.571
#Sta/Elev= 30
       0  953.13    31.8  942.09    87.5  918.71   111.4  910.49     179  890.56
   226.7  880.09   326.2  864.39   401.8  860.15   441.6  856.38   517.3  845.29
   553.1  837.96   648.7  834.51   664.6  832.56   674.2  829.76   680.5  829.35
   704.4  830.12   712.4  835.25   728.3  851.38   736.3  863.78   744.3  880.34
   752.2  887.98   768.2  900.31   784.1  910.66     812  926.14   859.8  942.07
   931.4  968.84  1011.1 1000.58  1070.8 1027.75  1114.6 1043.03  1158.4 1054.79
#Mann= 3 , 0 , 0
       0      .1       0   674.2    .045       0   704.4      .1       0
Bank Sta=674.2,704.4
XS Rating Curve= 0 ,0
Exp/Cntr=0.3,0.1

Type RM Length L Ch R = 1 ,19734.9 ,480.4,486.9,493.3
XS GIS Cut Line= 3
     2356685.194       404090.11     2356975.992      404009.815
     2357646.565      403586.637
#Sta/Elev= 30
       0  928.09    87.3  899.03   154.8  882.58   238.2  853.37     254  849.02
   273.9  845.32   317.6   839.5   349.5   837.1   425.2  835.47   548.7  835.82
   576.6  834.32   636.4  834.01   648.3  832.76   664.3  829.63   688.2  830.16
   705.4  824.92   720.1  824.74     732   825.6     736  830.03     744  841.02
   755.9  853.17   759.9  856.08   771.9  861.84   787.8  867.61   835.6  882.08
   903.4  897.19   939.2   906.7  1010.9  920.76  1078.7     938  1094.6  941.11
#Mann= 3 , 0 , 0
       0      .1       0   705.4    .045       0     732      .1       0
Bank Sta=705.4,732
XS Rating Curve= 0 ,0
Exp/Cntr=0.3,0.1

Type RM Length L Ch R = 1 ,19248.1 ,378.8,380.5,382.9
XS GIS Cut Line= 3
     2356823.916      404435.262     2357761.582      404168.235
     2357865.749      404263.721
#Sta/Elev= 30
       0  912.49    63.9  887.64    79.9  882.92   139.8  871.01   199.8  860.78
   231.8  853.26   311.7  841.81   339.6  835.99   427.5  829.17   487.5  830.33
   527.4  829.85   575.4  827.58   639.3  827.32   671.3  820.95   679.3  820.67
   699.2  821.41   707.2  825.44   727.2  840.86   739.2  852.41   763.2  879.11
   787.2  903.55   803.1  916.14   811.1  919.86   827.1  921.68   851.1  921.03
   867.1  919.27     883  916.49     947  901.65     955  901.29  1116.3  924.26
#Mann= 3 , 0 , 0
       0      .1       0   671.3    .045       0   699.2      .1       0
#XS Ineff= 2 , 0
          517.58  835.43
Permanent Ineff=
       F       F
Bank Sta=671.3,699.2
XS Rating Curve= 0 ,0
Exp/Cntr=0.3,0.1

Type RM Length L Ch R = 1 ,18867.6 ,426.7,424.3,421.5
XS GIS Cut Line= 3
     2356893.527      404741.151     2357770.263      404576.221
     2357893.961      404665.196
#Sta/Elev= 30
       0  922.24    67.7  906.41   123.5  898.24   135.4  894.71   183.2   884.3
   258.9  869.38   298.7  859.26   366.4  837.74   410.2  829.26   430.1  826.34
     458  824.23   517.8   825.4   549.6  823.88   593.4  824.58   609.4  820.89
   621.3  819.88   625.3  819.69   645.2  820.27   673.1  821.93     677  823.43
     681  826.53     693  839.16   720.9  864.36   816.4  929.54   840.3  944.48
   856.3  952.08   868.2  955.75   892.1  959.74     982  967.51  1044.5  971.08
#Mann= 3 , 0 , 0
       0      .1       0   621.3    .045       0   645.2      .1       0
Bank Sta=621.3,645.2
XS Rating Curve= 0 ,0
Exp/Cntr=0.3,0.1

Type RM Length L Ch R = 1 ,18443.3 ,592.7,588,582.5
XS GIS Cut Line= 3
     2357036.756      405177.349     2357746.135      404985.601
     2357946.044      404860.509
#Sta/Elev= 30
       0  939.82   143.8  881.24   183.7  867.14   251.6  845.37   279.6  837.11
   315.5  828.22   331.5  819.85   335.5  818.66   347.4  818.35   371.4  819.86
   455.3  819.36   471.2  820.58   487.2  817.86   507.2  817.95   515.2  816.84
   519.2  816.61   535.2   817.2   551.1  821.84   571.1  819.88   579.1  819.98
     627  828.14   694.9  833.17   706.9  835.41   718.9  839.14   794.8   869.9
   834.8  888.84   850.8  898.32   898.7  923.21   942.7  949.12   970.7  959.54
#Mann= 3 , 0 , 0
       0      .1       0   515.2    .045       0   535.2      .1       0
Bank Sta=515.2,535.2
XS Rating Curve= 0 ,0
Exp/Cntr=0.3,0.1

Type RM Length L Ch R = 1 ,17855.3 ,589.1,586.8,585
XS GIS Cut Line= 3
     2357182.155      405837.071      2357885.28      405424.745
     2358147.867      405199.051
#Sta/Elev= 30
       0 1006.83      36  993.38    91.9  975.97   107.9  969.81   131.9  959.37
   163.8   943.2   243.7  906.92   307.7   882.6   355.6  863.13   383.6  854.04
   435.5   841.4   507.4   815.5   527.4  811.28   535.4  810.31   551.2  811.69
   575.4  815.79   623.3  814.28   635.3  816.76   731.2  816.49   755.2  822.46
   787.1  825.34   807.1  828.82   823.1  834.45   854.9  842.99   878.8  851.48
   978.3  893.57  1061.9  933.03  1125.5  970.55  1145.4  979.25  1161.4  984.49
#Mann= 3 , 0 , 0
       0      .1       0   527.4    .045       0   551.2      .1       0
Bank Sta=527.4,551.2
XS Rating Curve= 0 ,0
Exp/Cntr=0.3,0.1

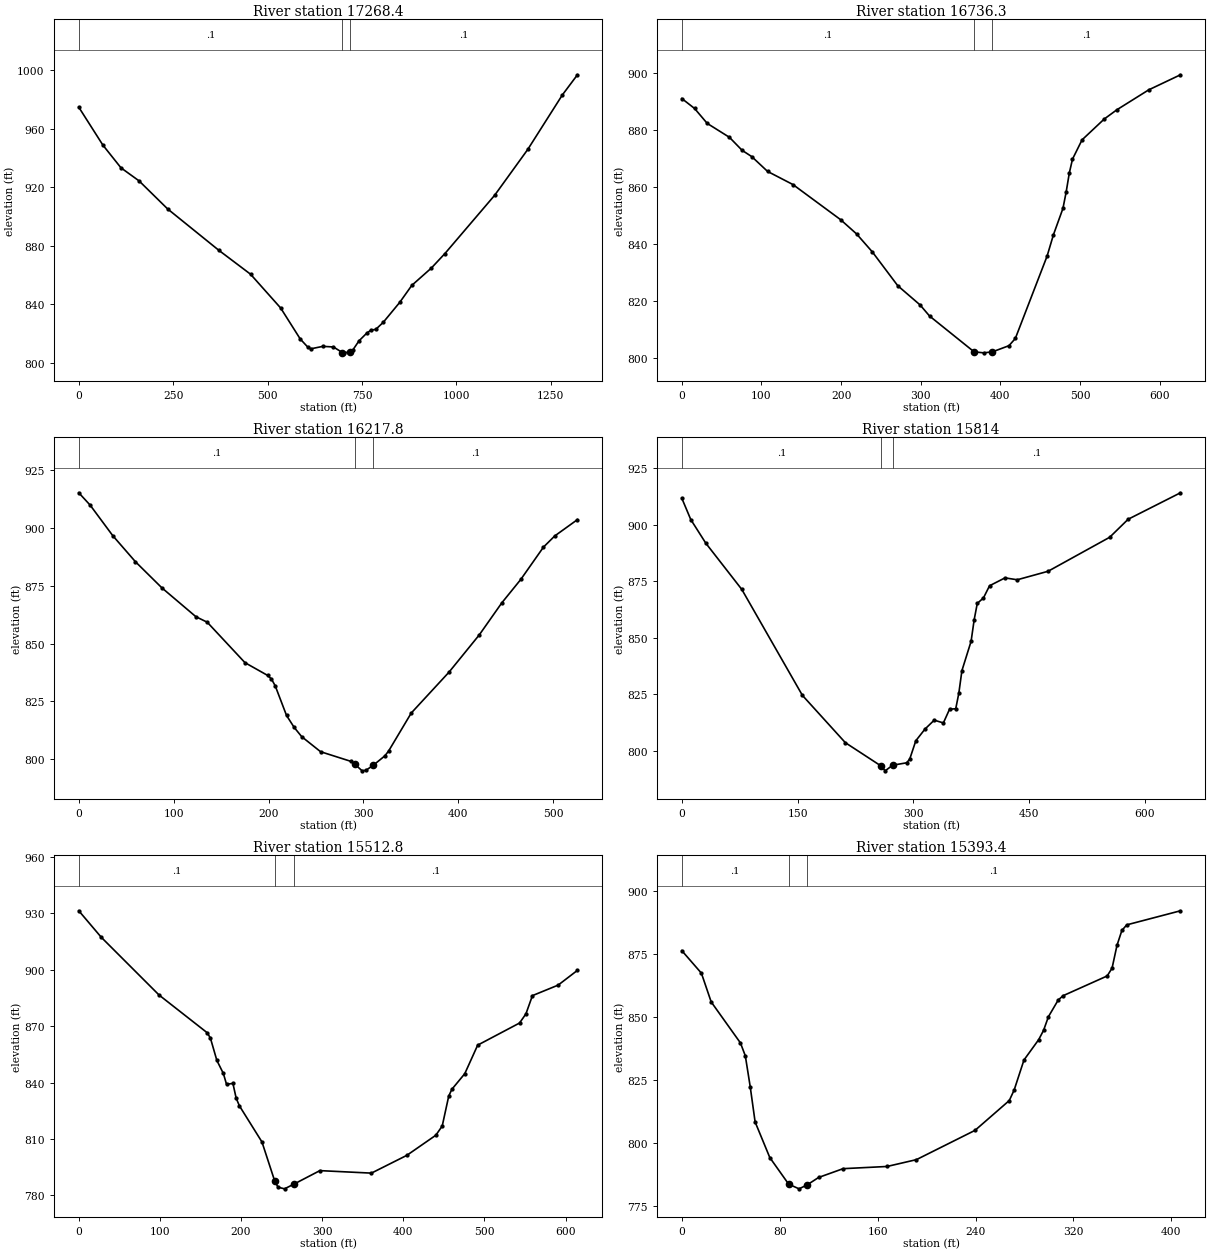
Type RM Length L Ch R = 1 ,17268.4 ,519.3,532.1,544.9
XS GIS Cut Line= 3
     2357508.566      406361.353     2358210.801      405841.412
     2358462.537      405472.488
#Sta/Elev= 30
       0  974.66    63.8  948.76   111.7  933.21   159.6  924.28   235.4  905.06
     371  876.76   454.8  860.43   534.6   837.3   586.5  816.08   606.4  810.57
   614.4   809.4   646.4  811.09   674.3  810.66   697.7  806.88   702.2  806.65
   718.2  807.45   726.2  808.83   742.1  814.89     762     820     774  822.26
     786  822.62   805.9  827.44   849.8  841.16   881.8   852.8   933.6  864.66
   969.5  874.58  1101.1  914.41  1188.8  945.78  1280.5   983.1  1320.4  996.86
#Mann= 3 , 0 , 0
       0      .1       0   697.7    .045       0   718.2      .1       0
Bank Sta=697.7,718.2
XS Rating Curve= 0 ,0
Exp/Cntr=0.3,0.1

Type RM Length L Ch R = 1 ,16736.3 ,541.9,518.5,495.1
XS GIS Cut Line= 2
     2357860.235      406456.874     2358485.235      406417.811
#Sta/Elev= 30
       0  891.05      16  887.57    31.9  882.32    59.8  877.43    75.8  872.84
    87.8  870.66   107.7  865.45   139.6  860.83   199.4   848.5   219.4  843.51
   239.3  837.16   271.2  825.29   299.2  818.55   311.1  814.65     367  802.08
   378.9  801.72   389.9  802.05   410.8  804.23   418.8  806.76   458.7   835.7
   466.7  843.23   478.6  852.45   482.6  858.14   486.6  864.89   490.6  869.77
   502.6  876.54   530.5  883.87   546.4  887.12   586.3   894.1   626.2   899.4
#Mann= 3 , 0 , 0
       0      .1       0     367    .045       0   389.9      .1       0
Bank Sta=367,389.9
XS Rating Curve= 0 ,0
Exp/Cntr=0.3,0.1

Type RM Length L Ch R = 1 ,16217.8 ,405.3,403.8,401.8
XS GIS Cut Line= 2
     2358339.836      406986.388     2358598.082      406528.489
#Sta/Elev= 30
       0  915.23      12  909.87    35.8  896.68    59.7   885.4    87.6  874.09
   123.5  861.59   135.4  859.22   175.2  841.71   199.1  836.19   203.1  834.64
   207.1  831.67     219  818.87     227  813.73     235  809.69   254.9  803.18
   286.8  799.01   290.7  797.89   298.7   794.9   302.7  795.13   310.5  797.34
   322.6  801.36   326.6  803.46   350.5  819.92   390.3  837.61   422.2  853.73
     446  867.62     466  877.75   489.9  891.73   501.8  896.56   525.7  903.62
#Mann= 3 , 0 , 0
       0      .1       0   290.7    .045       0   310.5      .1       0
Bank Sta=290.7,310.5
XS Rating Curve= 0 ,0
Exp/Cntr=0.3,0.1

Type RM Length L Ch R = 1 ,15814   ,331.4,301.2,271
XS GIS Cut Line= 4
     2358780.105      407163.949     2358752.761      407050.667
     2358844.297      406848.107     2358732.872      406561.941
#Sta/Elev= 30
       0  911.65    11.6  902.23    31.1  891.77    77.7  871.35   156.2  824.53
   211.8  803.63     258  793.34   263.4  791.18     273  793.67   291.2  794.73
   295.2  796.37   303.1  804.48     315  809.65   326.9  813.57   338.8  812.36
   346.8  818.42   354.8  818.62   358.8  825.49   362.8  835.46   374.7  848.44
   378.7     858   382.7  865.17   390.7  867.59   398.6  872.97   418.6  876.45
   434.5  875.62   474.4  879.37   554.2   894.4   578.1  902.36   645.9  914.06
#Mann= 3 , 0 , 0
       0      .1       0     258    .045       0     273      .1       0
Bank Sta=258,273
XS Rating Curve= 0 ,0
Exp/Cntr=0.3,0.1

Type RM Length L Ch R = 1 ,15512.8 ,140.8,119.4,97.8
XS GIS Cut Line= 3
     2359141.682      407070.036     2359119.981      406881.234
      2358787.95      406616.477
#Sta/Elev= 30
       0  931.34    27.7  917.25      99  886.51   158.4  866.43   162.3  863.55
   170.2  851.74   178.2  844.81   182.1  839.07     190   839.5     194  831.66
     198  827.58   225.8  808.37   241.6  787.48   245.6  784.33   253.6  783.44
   265.4  785.99   297.2  793.13   360.7   791.8   404.4  801.26   440.1  811.94
     448  816.85     456  832.74   459.9   836.4   475.8  844.69   491.7  859.87
   543.3  871.63   551.2  876.52   559.2  886.21   590.9   891.8   614.7  899.66
#Mann= 3 , 0 , 0
       0      .1       0   241.6    .045       0   265.4      .1       0
Bank Sta=241.6,265.4
XS Rating Curve= 0 ,0
Exp/Cntr=0.3,0.1

Type RM Length L Ch R = 1 ,15393.4 ,212.1,224.6,236.5
XS GIS Cut Line= 3
     2359164.903      406698.986     2358976.535      406751.937
     2358822.021      406606.972
#Sta/Elev= 30
       0  876.21      16  867.27      24  855.85    47.9  839.57    51.9  834.44
    55.9  822.17    59.9  808.18    71.9  794.05    87.3   783.5    95.8  781.63
   102.3  783.17   111.8  786.15   131.8  789.64   167.7  790.51   191.7  793.22
   239.6  804.85   267.6  816.69   271.6  820.89   279.6  832.79   291.6  840.85
   295.6  844.54   299.6  849.99   307.6  856.62   311.6  858.32   347.6  866.16
   351.6  869.27   355.6  878.28   359.6  884.22   363.6  886.45   407.5  892.04
#Mann= 3 , 0 , 0
       0      .1       0    87.3    .045       0   102.3      .1       0
Bank Sta=87.3,102.3
XS Rating Curve= 0 ,0
Exp/Cntr=0.3,0.1

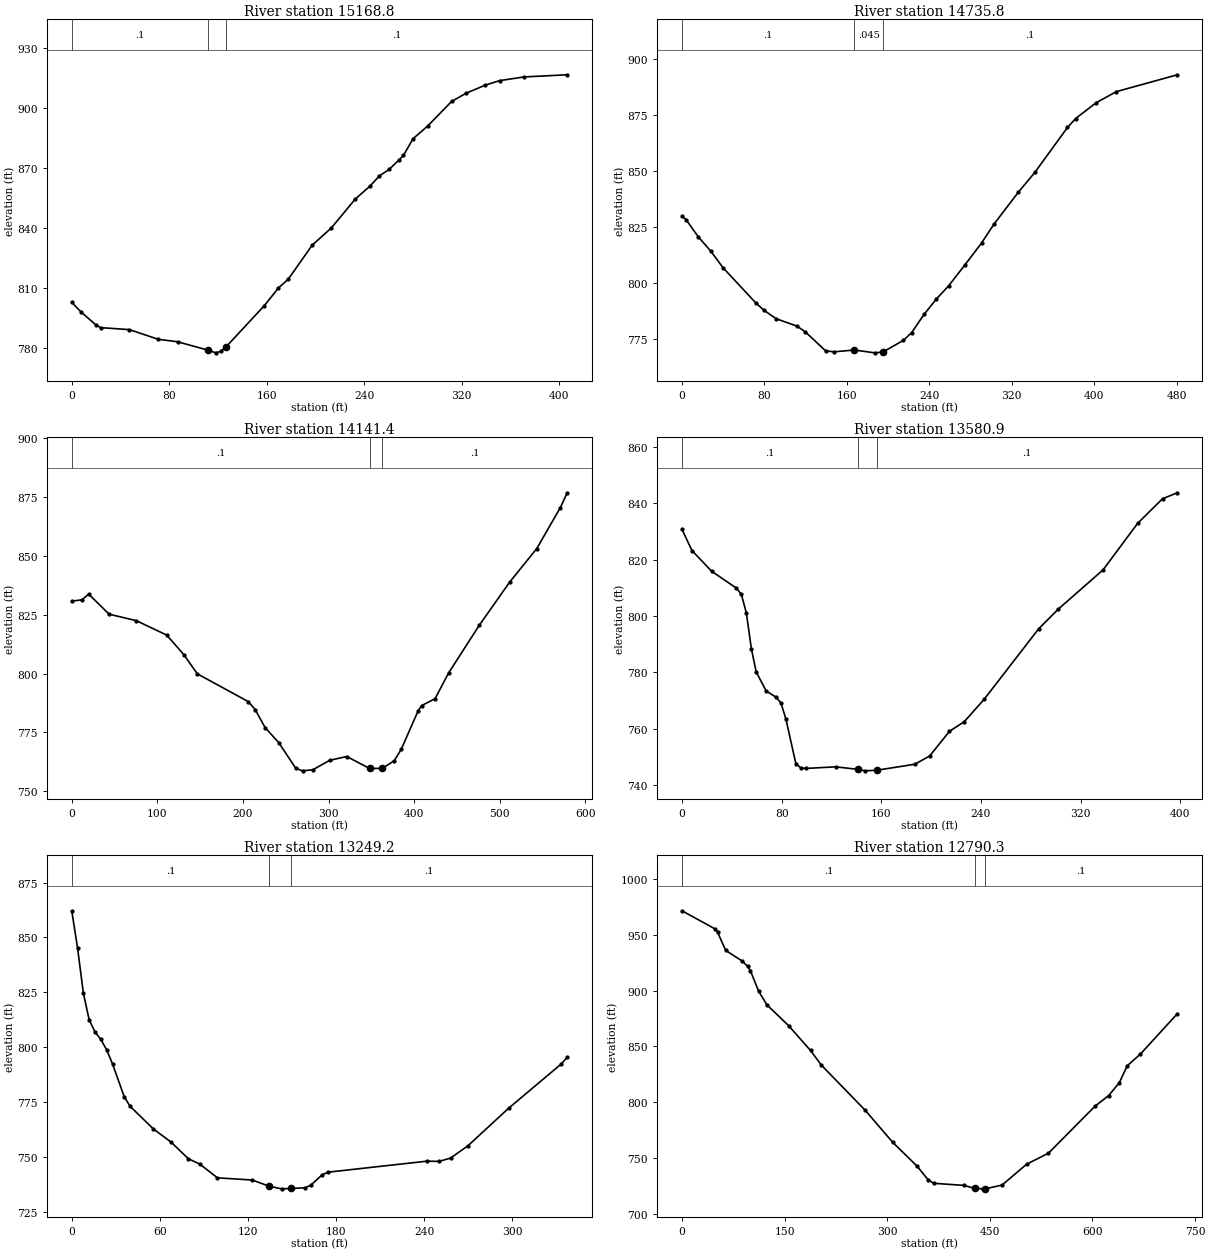
Type RM Length L Ch R = 1 ,15168.8 ,422.7,433,443
XS GIS Cut Line= 3
     2359133.002      406544.862     2358861.734      406475.418
     2358738.036      406449.376
#Sta/Elev= 30
       0  802.68     7.9  797.71    19.7  791.46    23.7  790.02    47.3  789.03
      71  784.17    86.8  782.94   111.4   778.8   118.3  777.39   122.3  778.18
   126.4  780.27   157.8  800.93   169.6  809.94   177.5  814.23   197.2  831.32
     213  840.03   232.7  854.56   244.5  860.86   252.4  866.09   260.3  869.31
   268.2  873.92   272.1  876.38     280  884.73   291.9  891.02   311.6  903.39
   323.5   907.5   339.3  911.59   351.1  913.83   370.9  915.67   406.4  916.76
#Mann= 3 , 0 , 0
       0      .1       0   111.4    .045       0   126.4      .1       0
Bank Sta=111.4,126.4
XS Rating Curve= 0 ,0
Exp/Cntr=0.3,0.1

Type RM Length L Ch R = 1 ,14735.8 ,557.1,594.4,632
XS GIS Cut Line= 3
     2359337.533      406246.558      2359065.94      406019.133
     2358965.363      405942.559
#Sta/Elev= 30
       0  829.81       4   828.2    15.9   820.5    27.9  814.16    39.8  806.72
    71.6  790.97    79.6  787.64    91.5  783.86   111.4  780.59   119.4  778.12
   139.3  769.52   147.3  769.06   167.2  769.87   187.1  768.61     195  768.99
   214.9  774.22   222.9  777.68   234.8  785.77   246.8  792.69   258.7  798.58
   274.6  808.01   290.6  817.72   302.5  826.07   326.4  840.53   342.3  849.31
     374  869.46   381.9  873.46   401.6  880.45   421.4  885.49   480.6  893.03
#Mann= 3 , 0 , 0
       0      .1       0   167.2    .045       0     195      .1       0
Bank Sta=167.2,195
XS Rating Curve= 0 ,0
Exp/Cntr=0.3,0.1

Type RM Length L Ch R = 1 ,14141.4 ,526.7,560.5,593.7
XS GIS Cut Line= 3
     2359436.301       406167.66     2359744.634      405842.475
     2359833.609      405746.989
#Sta/Elev= 30
       0  830.82    11.9   831.4    19.8  833.82    43.6  825.28    75.4  822.53
     111  816.37   130.9  808.07   146.7   799.9   206.2   788.1   214.2  784.72
     226  776.96   241.9   770.6   261.7  759.69   269.7  758.66   281.6  759.12
   301.4  763.15   321.2  764.75   347.8  759.67   362.8   759.7   376.7     763
   384.7  767.74   404.5  784.13   408.5  786.37   424.3  789.33   440.2  800.32
   475.8  820.48   511.4   838.9     543  853.14   570.7  870.63   578.6  876.91
#Mann= 3 , 0 , 0
       0      .1       0   347.8    .045       0   362.8      .1       0
Bank Sta=347.8,362.8
XS Rating Curve= 0 ,0
Exp/Cntr=0.3,0.1

Type RM Length L Ch R = 1 ,13580.9 ,347.4,331.6,315.8
XS GIS Cut Line= 2
     2359358.696      406258.404     2359679.877      406492.779
#Sta/Elev= 30
       0   830.8       8  823.26    23.9  815.87    43.7  809.91    47.7  807.66
    51.7  801.08    55.7  788.43    59.6  780.15    67.6   773.4    75.5  771.22
    79.5   769.1    83.5  763.31    91.4  747.63    95.4   746.1    99.4  745.91
   123.3  746.48   141.4  745.58   147.1  745.06   156.4  745.28   186.9   747.4
   198.8  750.34   214.7  759.08   226.6  762.52   242.5  770.43   286.3  795.49
   302.2  802.52     338  816.41   365.8  832.94   385.7  841.64   397.6  843.75
#Mann= 3 , 0 , 0
       0      .1       0   141.4    .045       0   156.4      .1       0
Bank Sta=141.4,156.4
XS Rating Curve= 0 ,0
Exp/Cntr=0.3,0.1

Type RM Length L Ch R = 1 ,13249.2 ,475.4,459,442.5
XS GIS Cut Line= 2
     2359206.786      406640.348     2359543.158      406614.307
#Sta/Elev= 30
       0  862.14       4  845.02     7.9  824.72    11.9  812.44    15.9  806.96
    19.8  803.64    23.8  798.88    27.8  792.43    35.7  777.63    39.7  773.24
    55.6  762.92    67.5     757    79.4  749.38    87.3  746.89    99.2  740.69
     123  739.68   134.6  736.83   142.9  735.68   149.6  735.85   158.8  736.16
   162.7  737.27   170.7  742.15   174.6  743.26   242.1  748.28   250.1  748.15
     258  749.66   269.9  755.31   297.7  772.44   333.4  792.47   337.4  795.53
#Mann= 3 , 0 , 0
       0      .1       0   134.6    .045       0   149.6      .1       0
Bank Sta=134.6,149.6
XS Rating Curve= 0 ,0
Exp/Cntr=0.3,0.1

Type RM Length L Ch R = 1 ,12790.3 ,511.8,522.7,533.6
XS GIS Cut Line= 3
     2359326.144      407215.435     2359764.512      406766.216
     2359814.425      406683.751
#Sta/Elev= 30
       0  971.45      48  955.36      52  952.33      64  935.92      88   926.5
      96  921.64     100  917.85   111.9   899.7   123.9  887.45   155.9  868.61
   187.9  846.43   203.9  833.22   267.9  792.86   307.8  764.38   343.8  742.76
   359.8  730.64   367.8  727.54   411.8  725.68   428.2  722.96   439.8  722.57
   443.2  722.63   467.8   725.9   503.7  744.59   535.7  754.48   603.7  796.52
   623.7  806.05   639.2  817.52   650.8   832.7   670.1   843.2   724.1  879.33
#Mann= 3 , 0 , 0
       0      .1       0   428.2    .045       0   443.2      .1       0
Bank Sta=428.2,443.2
XS Rating Curve= 0 ,0
Exp/Cntr=0.3,0.1

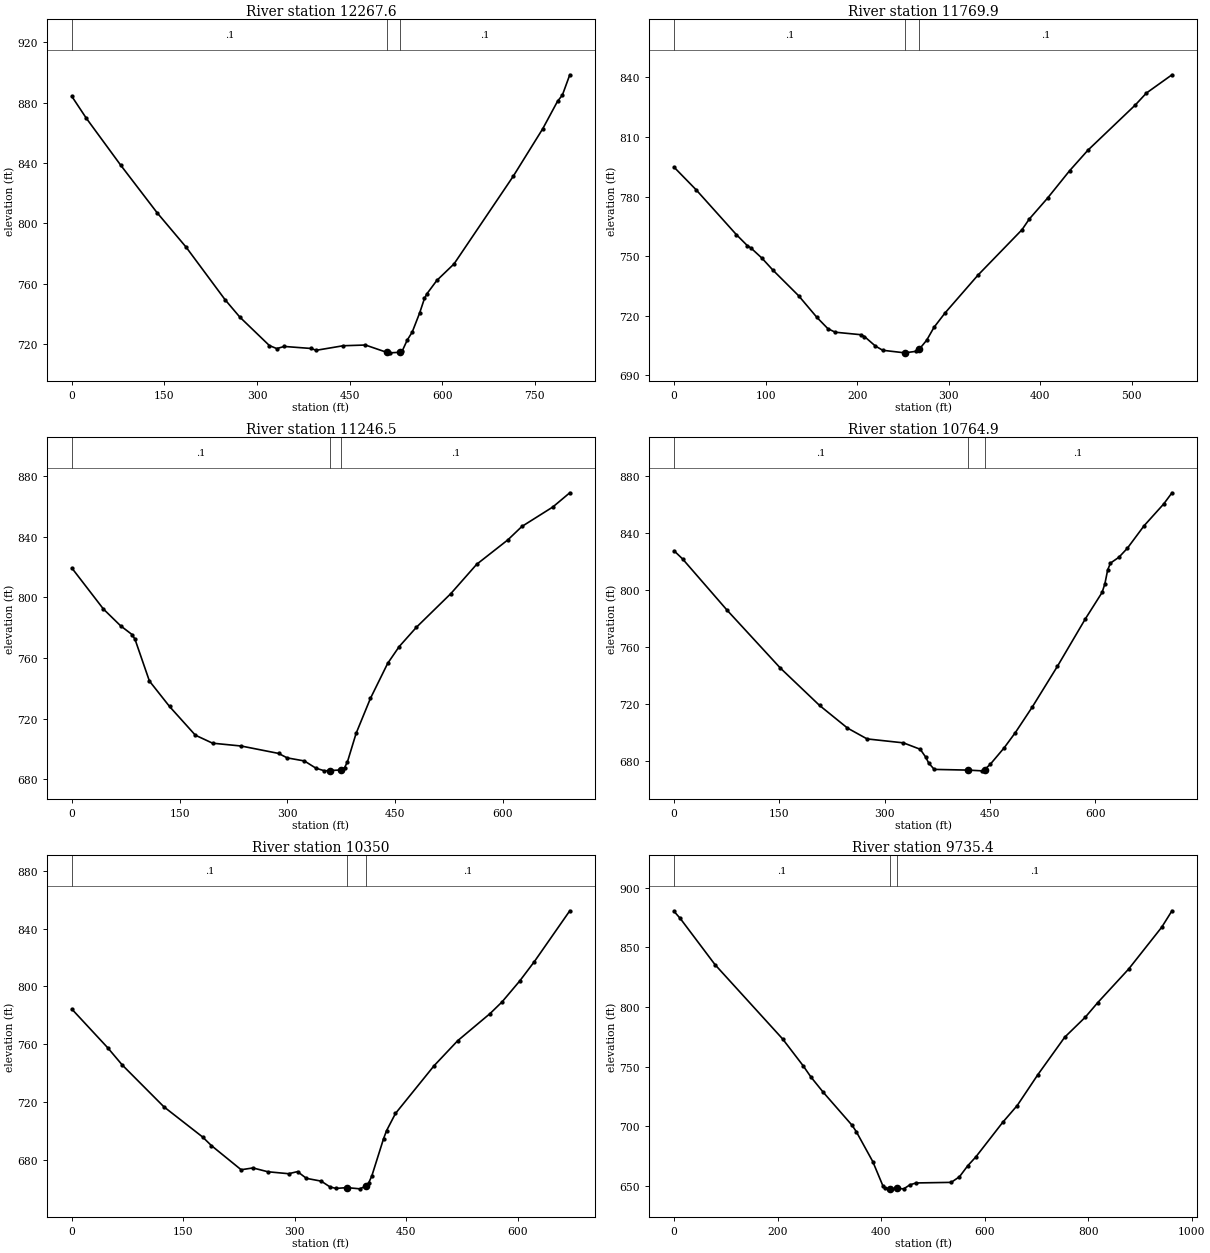
Type RM Length L Ch R = 1 ,12267.6 ,480.8,497.6,514.2
XS GIS Cut Line= 3
     2359491.075      407326.112     2359742.811      407341.303
     2360270.155      407169.862
#Sta/Elev= 30
       0  884.02    23.6  869.47    78.8  838.69   137.9  807.14   185.2  784.21
   248.2  749.49   272.1  737.98     320  719.14     332  717.13     344  718.55
   387.8   717.2   395.8     716   439.7  719.02   475.6  719.49   510.6  714.58
   515.5  714.32   531.4  714.69   535.4  715.73   543.4  722.81   551.4  728.04
   563.4  740.65   571.3  750.38   575.3  753.44   591.3  762.25   619.2  773.19
     715  831.15   762.8  862.58   786.8  880.78   794.7  884.91   806.7  898.35
#Mann= 3 , 0 , 0
       0      .1       0   510.6    .045       0   531.4      .1       0
Bank Sta=510.6,531.4
XS Rating Curve= 0 ,0
Exp/Cntr=0.3,0.1

Type RM Length L Ch R = 1 ,11769.9 ,548.2,523.4,498.5
XS GIS Cut Line= 2
      2359580.05      407595.209     2360074.842      407820.904
#Sta/Elev= 30
       0  794.77      24  783.43      68  760.82      80  755.27      84  754.05
      96  748.94     108   742.9     136  730.03     156  719.11     168  713.42
     176  711.64   203.9  710.39   207.9  709.47   219.9  704.66   227.9  702.54
   251.9  701.25   263.9  701.99   267.9  703.14   275.9  707.63   283.9  714.11
   295.9  721.32   331.9   740.4   379.9  763.23   387.9  768.63   407.9   779.2
   431.9  792.95   451.9   803.3   503.8  826.14   515.8  832.11   543.8  841.33
#Mann= 3 , 0 , 0
       0      .1       0   251.9    .045       0   267.9      .1       0
Bank Sta=251.9,267.9
XS Rating Curve= 0 ,0
Exp/Cntr=0.3,0.1

Type RM Length L Ch R = 1 ,11246.5 ,481.5,481.7,481.7
XS GIS Cut Line= 3
      2359571.37      408333.057      2360035.78      407985.834
     2360146.457      407959.793
#Sta/Elev= 30
       0  819.37      44  792.28      68   781.2      84  775.41      88  772.27
     108  744.81     136  728.02     172  709.06     196  703.77   235.9   701.9
   287.9  697.02   299.9  694.08   323.9  692.04   339.9  687.29   351.9  685.52
     360  685.71     375  686.13   379.9  687.63   383.9   691.5   395.9   710.2
   415.9  733.35   439.9  756.44   455.9   767.5   479.9  780.26   527.9   802.5
   563.9  821.84   607.3  837.96   626.9  846.82     670  859.68   693.6  869.05
#Mann= 3 , 0 , 0
       0      .1       0     360    .045       0     375      .1       0
Bank Sta=360,375
XS Rating Curve= 0 ,0
Exp/Cntr=0.3,0.1

Type RM Length L Ch R = 1 ,10764.9 ,405.4,414.9,424.1
XS GIS Cut Line= 2
     2359762.342      408775.765     2360333.089      408354.758
#Sta/Elev= 30
       0  827.75      12  822.12    75.7  785.93   151.4  745.36   207.2  719.13
     247  703.22   274.9   695.6   326.7  692.83   350.6  688.32   358.6  682.67
   362.6  678.67   370.6  674.18   418.4  673.69   438.3  673.17   442.3  674.08
   450.2  677.68   470.2  689.37   486.1  700.05     510  717.86   545.9  746.52
   585.7  779.87   609.6  798.48   613.6  804.54   617.6  814.37   621.6  819.14
   633.5  823.19   645.5  829.48   669.4  845.34   697.3  860.62   709.2  868.53
#Mann= 3 , 0 , 0
       0      .1       0   418.4    .045       0   442.3      .1       0
Bank Sta=418.4,442.3
XS Rating Curve= 0 ,0
Exp/Cntr=0.3,0.1

Type RM Length L Ch R = 1 ,10350   ,616.3,614.6,613
XS GIS Cut Line= 3
     2359946.804      408951.546     2360411.214       408849.55
     2360591.335      408775.765
#Sta/Elev= 30
       0  784.25      48  757.62    67.9   745.5   123.9  716.56   175.8  695.73
   187.8  689.71   227.8  672.98   243.7  674.23   263.7  671.59   291.7  670.23
   303.7  671.68   315.6  667.02   335.6  665.08   347.6     661   355.6  660.05
   370.3   660.6   387.6  659.75   395.6  661.69   399.6  664.05   403.6  668.57
   419.5  694.54   423.5  700.05   435.5  711.96   487.4  745.01   519.2  762.36
   562.9  781.22   578.8  789.18   602.6  803.68   622.5  817.23   670.1  852.39
#Mann= 3 , 0 , 0
       0      .1       0   370.3    .045       0   395.6      .1       0
Bank Sta=370.3,395.6
XS Rating Curve= 0 ,0
Exp/Cntr=0.3,0.1

Type RM Length L Ch R = 1 ,9735.4  ,492.3,490.8,489
XS GIS Cut Line= 3
     2359864.339      409578.716     2360176.839      409509.272
     2360790.988       409322.64
#Sta/Elev= 30
       0  880.29    11.9  874.38      79  835.62   209.5  773.27     249  750.84
   264.8  740.95   288.5  728.21     344  700.57     352  695.32   383.9  670.14
   403.8   649.4   407.8   647.7   416.6  647.49   431.6  647.54   443.7  647.24
   455.7  650.61   467.6  652.19   535.4  652.67   551.4  657.39   567.3  666.59
   583.2  674.15   635.1  703.19     663  717.24   702.9  743.19   754.7  774.59
   794.6  791.48   818.5  803.65   878.3  831.89   942.1  866.98     962  880.81
#Mann= 3 , 0 , 0
       0      .1       0   416.6    .045       0   431.6      .1       0
Bank Sta=416.6,431.6
XS Rating Curve= 0 ,0
Exp/Cntr=0.3,0.1

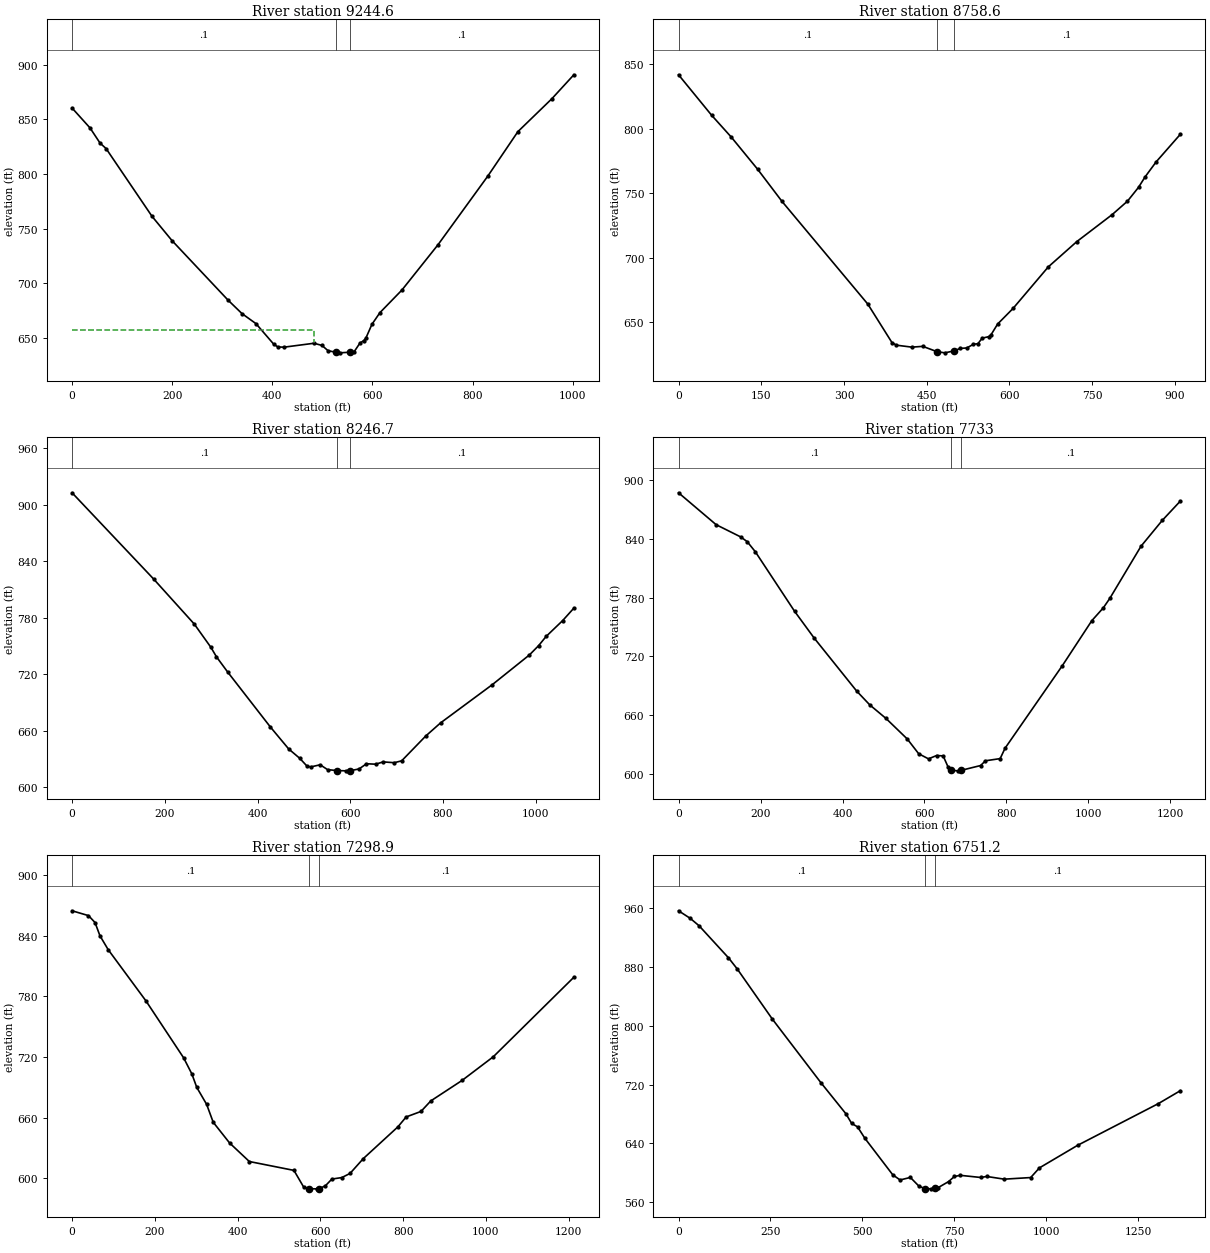
Type RM Length L Ch R = 1 ,9244.6  ,490.6,486,481.3
XS GIS Cut Line= 2
     2360018.418       410106.06     2360929.877      409689.394
#Sta/Elev= 30
       0  860.39    35.9  842.15    55.9  828.28    67.9   823.3   159.7  761.22
   199.6  739.01   311.4  684.56   339.4  672.15   367.3  662.97   403.3  643.88
   411.2  641.64   423.2  641.42   483.1  645.01   499.1  643.04   511.1  638.26
   527.4  636.68     535  636.24     555  636.83     563  636.99     575  645.21
   582.9  647.53   586.9  649.81   598.9  662.34   614.9  673.06   658.8  693.74
   730.7  735.11   830.5  798.17   890.4  838.76   958.3  868.91  1002.2  890.83
#Mann= 3 , 0 , 0
       0      .1       0   527.4    .045       0     555      .1       0
#XS Ineff= 2 , 0
          482.98  657.14
Permanent Ineff=
       F       F
Bank Sta=527.4,555
XS Rating Curve= 0 ,0
Exp/Cntr=0.3,0.1

Type RM Length L Ch R = 1 ,8758.6  ,508.6,512,515.3
XS GIS Cut Line= 2
     2360326.578      410603.022     2361060.085      410064.828
#Sta/Elev= 30
       0  841.75    59.8  810.47    95.8  793.36   143.6  768.41   187.5  743.65
   343.2  663.98     387  634.15     395  632.15     423  630.63   442.9  631.23
   468.6  627.12   482.8  626.21   498.8  627.65   510.8  629.63   522.7     630
   534.7  632.87   542.7  633.26   550.6  637.59   562.6  638.78   566.6  640.23
   578.6  648.56   606.5  660.62   670.4  692.83   722.2  712.47   786.1  733.32
     814  743.79     834  754.49   845.9  762.59   865.9  774.21   909.8   795.6
#Mann= 3 , 0 , 0
       0      .1       0   468.6    .045       0   498.8      .1       0
Bank Sta=468.6,498.8
XS Rating Curve= 0 ,0
Exp/Cntr=0.3,0.1

Type RM Length L Ch R = 1 ,8246.7  ,507.4,513.6,519.8
XS GIS Cut Line= 2
     2360450.276      411017.519     2361407.307      410511.876
#Sta/Elev= 30
       0  912.55   175.7  821.07   263.6  773.13   299.6   748.3   311.5  738.29
   335.5  722.26   427.4  664.01   467.3  640.44   491.3  630.44   507.2  621.98
   515.2  621.42   535.2  623.63   551.2  618.48   571.2  617.52   591.1  617.21
   599.1  617.26   619.1  619.23   635.1  624.74     655  624.27     671  626.71
     695  625.85     711  627.86   762.9   654.2   794.8   668.1   906.7  708.84
   986.5   740.3  1006.5  750.25  1022.5  759.93  1058.4  776.88  1082.4  790.02
#Mann= 3 , 0 , 0
       0      .1       0   571.2    .045       0   599.1      .1       0
Bank Sta=571.2,599.1
XS Rating Curve= 0 ,0
Exp/Cntr=0.3,0.1

Type RM Length L Ch R = 1 ,7733    ,418.3,434.2,450
XS GIS Cut Line= 4
     2360491.509      411230.192     2361077.446      411232.362
       2361298.8      411184.619     2361700.276      411093.473
#Sta/Elev= 30
       0  887.24    91.7  854.64   151.5  842.15   167.4  837.34   187.3  826.99
     283  766.18   330.8  738.79   434.5  684.62   466.4   670.5   506.2  656.56
     558   635.6   585.9   620.5   609.8   615.3   629.6  618.72   645.5  618.31
   657.4  607.14   665.4  603.66   681.3  603.05   689.2  603.53   736.9  608.48
   748.8  613.34   784.6  615.55   796.5  626.16   936.3  710.57  1008.2  756.53
  1036.2  769.62  1052.2  779.38  1128.2  832.62  1180.1  859.04  1224.1  878.74
#Mann= 3 , 0 , 0
       0      .1       0   665.4    .045       0   689.2      .1       0
Bank Sta=665.4,689.2
XS Rating Curve= 0 ,0
Exp/Cntr=0.3,0.1

Type RM Length L Ch R = 1 ,7298.9  ,557.6,547.7,537.7
XS GIS Cut Line= 4
     2360556.613      411338.699     2360925.536      411531.841
      2361246.49      411701.782     2361674.234      411633.838
#Sta/Elev= 30
       0  864.57    39.7  859.78    55.5  852.94    67.4  839.82    87.2  826.16
   178.5  775.44   269.7  719.01   289.5  703.14   301.4  689.79   325.2  673.04
   341.1  655.34   380.7  634.82   428.4  616.47   536.2   607.7   560.1  590.91
   571.7   589.5     592  589.44     596  589.51     612  592.37   627.9  599.11
   651.9  600.59   671.8  604.69   703.8  619.34   787.5   650.8   807.4  660.58
   843.2  666.01     867  676.45   942.5   696.7    1018  720.13  1212.7   798.8
#Mann= 3 , 0 , 0
       0      .1       0   571.7    .045       0     596      .1       0
Bank Sta=571.7,596
XS Rating Curve= 0 ,0
Exp/Cntr=0.3,0.1

Type RM Length L Ch R = 1 ,6751.2  ,500.3,499.3,498.2
XS GIS Cut Line= 2
     2360283.809      412105.086     2361647.432      412166.373
#Sta/Elev= 30
       0  956.41    31.9  946.08    55.9  936.02   135.7  892.54   159.6  877.32
   255.4  808.89   387.2  722.58     455  680.43     471  667.07   486.9  662.46
   506.9  646.86   582.7  597.22   602.7  590.15   630.6  593.63   654.6  581.44
   670.5  578.54   686.5   578.1   698.5  579.37   706.4   579.8   734.4  587.92
   750.4  594.89   766.3  596.49   822.2  593.55   838.2  594.95     886  591.27
   957.9  593.45   981.8  606.64  1085.6  637.31  1305.1  694.02    1365  711.61
#Mann= 3 , 0 , 0
       0      .1       0   670.5    .045       0   698.5      .1       0
Bank Sta=670.5,698.5
XS Rating Curve= 0 ,0
Exp/Cntr=0.3,0.1

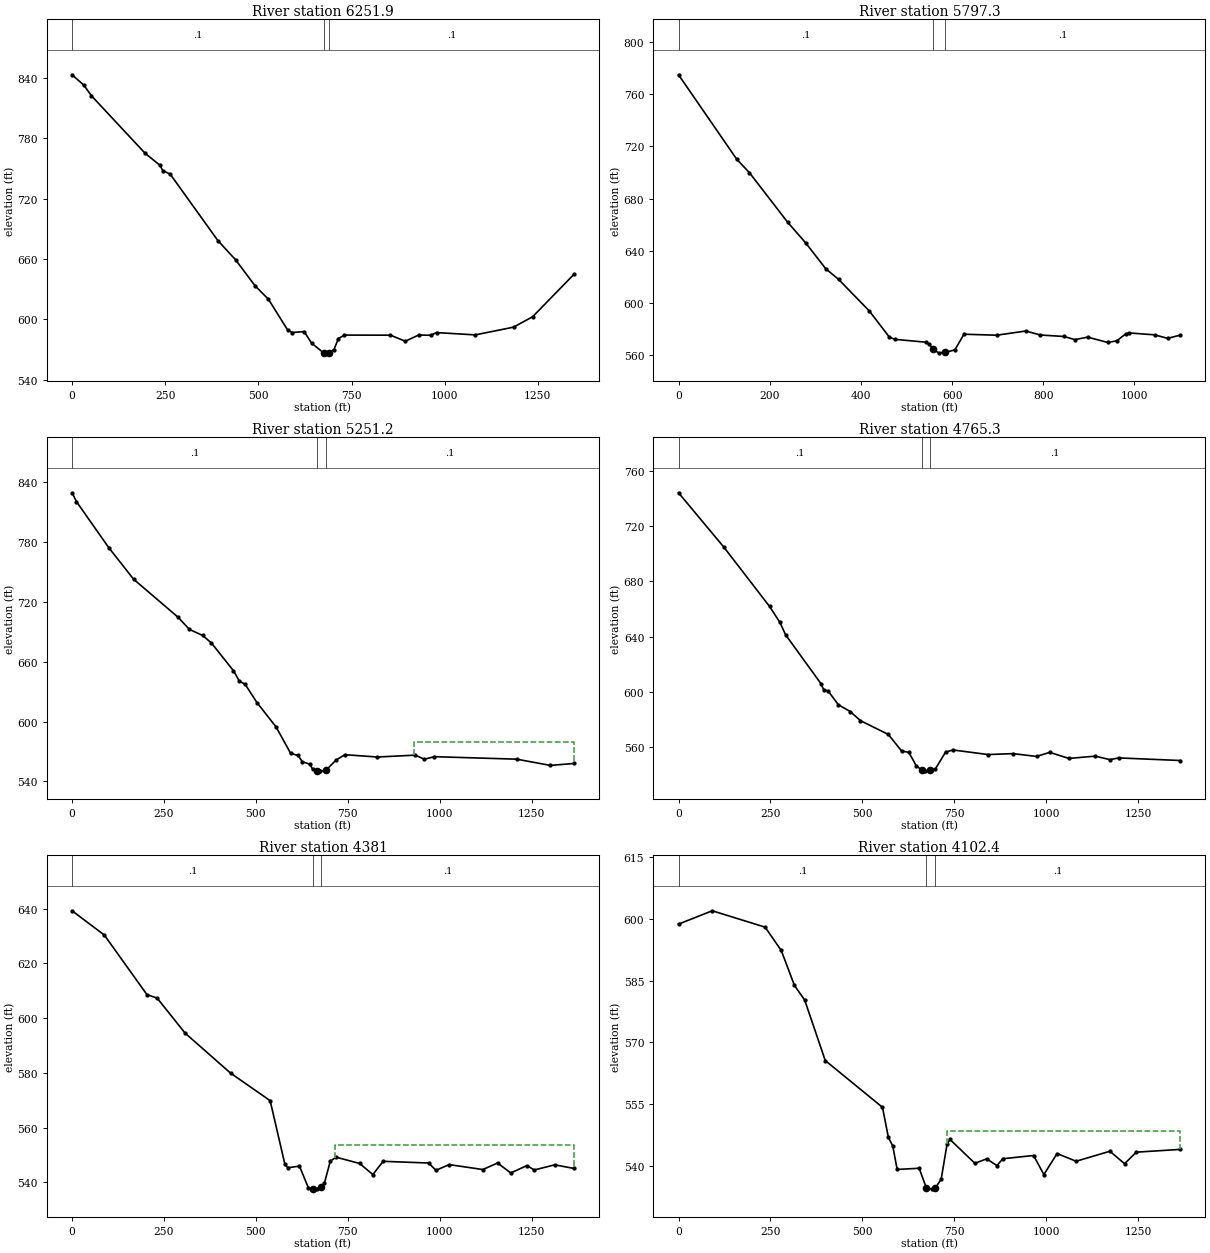
Type RM Length L Ch R = 1 ,6251.9  ,451.8,454.7,457.5
XS GIS Cut Line= 3
     2360291.695      412635.456     2361385.606      412634.272
     2361630.832      412573.508
#Sta/Elev= 30
       0  843.13    31.9  832.72    51.9  822.28   195.6  765.26   235.6  753.22
   243.5  747.93   263.5   744.3   391.2  678.37   439.2  659.05   491.1  633.37
     527  620.02   578.9   589.2   590.9  586.96   622.8  587.86   642.8  576.42
   674.7  566.75     675  566.75     690  567.03   702.7  569.79   714.6  580.87
   730.6  584.39   854.4   584.3   894.3  578.29   930.2  584.48   962.2   584.2
   978.1  586.89  1081.9  584.59  1184.7  592.26    1236  602.64  1346.6   644.7
#Mann= 3 , 0 , 0
       0      .1       0     675    .045       0     690      .1       0
Bank Sta=675,690
XS Rating Curve= 0 ,0
Exp/Cntr=0.3,0.1

Type RM Length L Ch R = 1 ,5797.3  ,538.3,546.1,553.8
XS GIS Cut Line= 2
     2360363.471      413014.046     2361455.425      413152.721
#Sta/Elev= 30
       0  774.91   127.6  710.26   155.5  699.94   239.3  662.02   279.2  646.08
     323  626.33     351  618.26   418.8  593.93   462.6  573.96   474.6  572.34
   542.4  570.13   550.4  568.55   558.3  564.76   570.3  561.99   584.1  562.26
   606.2  564.25   626.1  576.25   697.9  575.49   761.7   578.7   793.6  575.64
   845.5  574.52   869.4  572.09   897.3  574.02   941.2  569.97   961.1  571.14
   981.1  576.56   989.1  577.21  1044.9  575.76  1072.8  573.05  1100.7   575.6
#Mann= 3 , 0 , 0
       0      .1       0   558.3    .045       0   584.1      .1       0
Bank Sta=558.3,584.1
XS Rating Curve= 0 ,0
Exp/Cntr=0.3,0.1

Type RM Length L Ch R = 1 ,5251.2  ,485.5,485.9,485.7
XS GIS Cut Line= 2
     2360129.854      413280.365     2361347.394      413897.473
#Sta/Elev= 30
       0  829.18      12  820.32    99.8  774.21   167.6  742.52   287.4  704.82
   319.3  692.34   355.2  686.28   379.2  678.66     439  650.97     455  640.65
     471  637.22   502.9  619.09   554.8  594.69   594.7  568.12   614.6  566.08
   626.6  559.69   646.6  557.37   654.6  552.26   666.5  550.97   674.5  550.66
     690  551.04   718.4  561.56   742.4  566.83   830.2  564.51     934  566.38
   957.9  562.26   985.8  564.84  1209.3  562.35  1301.1  556.11    1365  558.03
#Mann= 3 , 0 , 0
       0      .1       0   666.5    .045       0     690      .1       0
#XS Ineff= 2 , 0
                           929.9             580
Permanent Ineff=
       F       F
Bank Sta=666.5,690
XS Rating Curve= 0 ,0
Exp/Cntr=0.3,0.1

Type RM Length L Ch R = 1 ,4765.3  ,389.6,384.3,379.5
XS GIS Cut Line= 2
     2359990.966      413744.775     2361208.505      414361.883
#Sta/Elev= 30
       0  744.29   123.7  704.72   247.5  661.89   275.4  650.45   291.4  641.23
   387.2  605.94   395.1  601.36   407.1  600.46     435  590.54     467  585.66
   494.9  579.04   570.8  569.01   606.7  557.06   626.6  556.02   646.6  546.33
   662.5  542.99   670.5  542.64     684  543.06   698.5  543.97   726.4  556.22
   746.4  557.78   842.2  554.45     910  555.13   973.9  553.08  1009.8  556.04
  1061.7  551.64  1133.5   553.3  1173.4  550.76  1197.4  552.02    1365  550.13
#Mann= 3 , 0 , 0
       0      .1       0   662.5    .045       0     684      .1       0
Bank Sta=662.5,684
XS Rating Curve= 0 ,0
Exp/Cntr=0.3,0.1

Type RM Length L Ch R = 1 ,4381    ,284.8,278.7,272.6
XS GIS Cut Line= 2
     2359862.525      414259.804     2361185.036      414597.722
#Sta/Elev= 30
       0  639.24    87.8  630.36   203.6   608.6   231.5  607.31   307.3  594.54
     431  579.91   538.8  569.83   578.7   546.7   586.7  545.31   618.6  545.89
   642.6  538.04   654.6  537.67   666.5  537.59   677.8  538.21   686.5  539.71
   702.5  547.73   718.4  549.16   782.3  546.86   818.2   542.8   846.1  547.65
   969.9  547.03   989.8  544.36  1025.8  546.45  1117.5  544.64  1157.5  547.04
  1193.4  543.39  1237.3  546.09  1257.2  544.49  1313.1  546.36    1365  545.05
#Mann= 3 , 0 , 0
       0      .1       0   654.6    .045       0   677.8      .1       0
#XS Ineff= 2 , 0
                          714.64          553.57
Permanent Ineff=
       F       F
Bank Sta=654.6,677.8
XS Rating Curve= 0 ,0
Exp/Cntr=0.3,0.1

Type RM Length L Ch R = 1 ,4102.4  ,225.2,224.5,223.8
XS GIS Cut Line= 2
      2359795.86      414716.646     2361160.555      414687.755
#Sta/Elev= 30
       0  598.68    91.8  601.91   235.5  597.94   279.4  592.29   315.3  583.82
   343.2  580.26   399.1  565.61   554.8  554.27   570.8  546.98   582.7  544.93
   594.7  539.21   654.6   539.5   674.5  534.64   690.5  534.51   698.5  534.74
   714.4  536.81   730.4  545.31   738.4  546.48   806.2  540.69   838.2  541.79
   866.1  540.14   882.1  541.81   965.9  542.59   993.8  537.96  1029.7  543.06
  1081.6   541.2  1173.4  543.62  1213.3   540.6  1245.3   543.4    1365  544.07
#Mann= 3 , 0 , 0
       0      .1       0   674.5    .045       0   698.5      .1       0
#XS Ineff= 2 , 0
                          731.26          548.48
Permanent Ineff=
       F       F
Bank Sta=674.5,698.5
XS Rating Curve= 0 ,0
Exp/Cntr=0.3,0.1