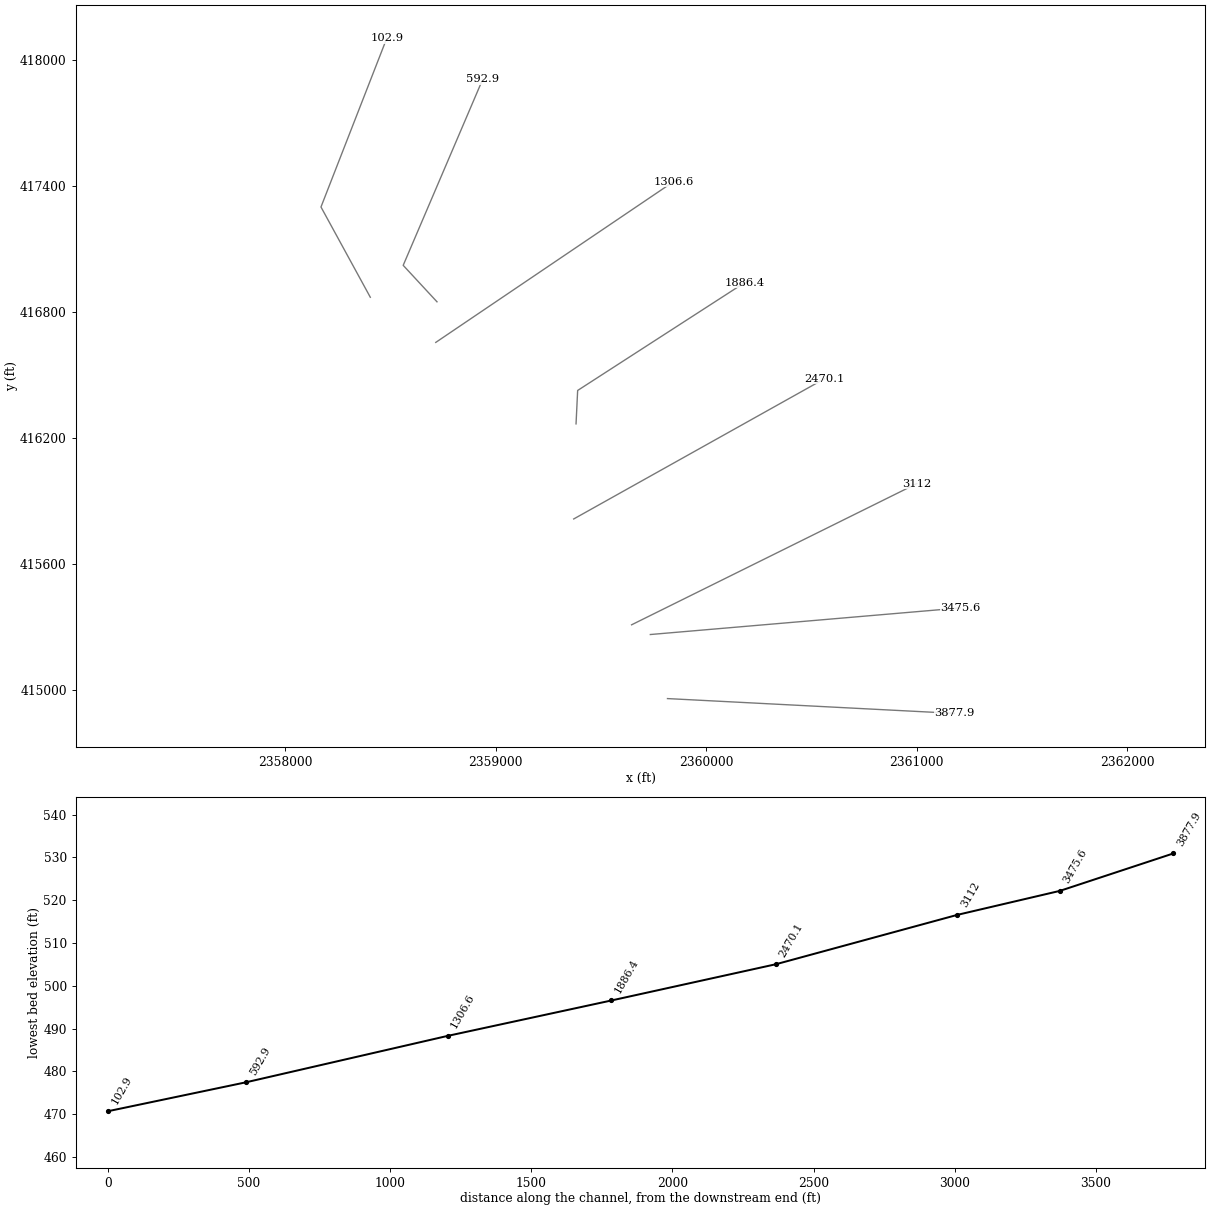
HEC-RAS study MEADOWBRCH.prj: MEADOWBRCH

--- MEADOWBRCH.g01 (geometry) --- (continued)

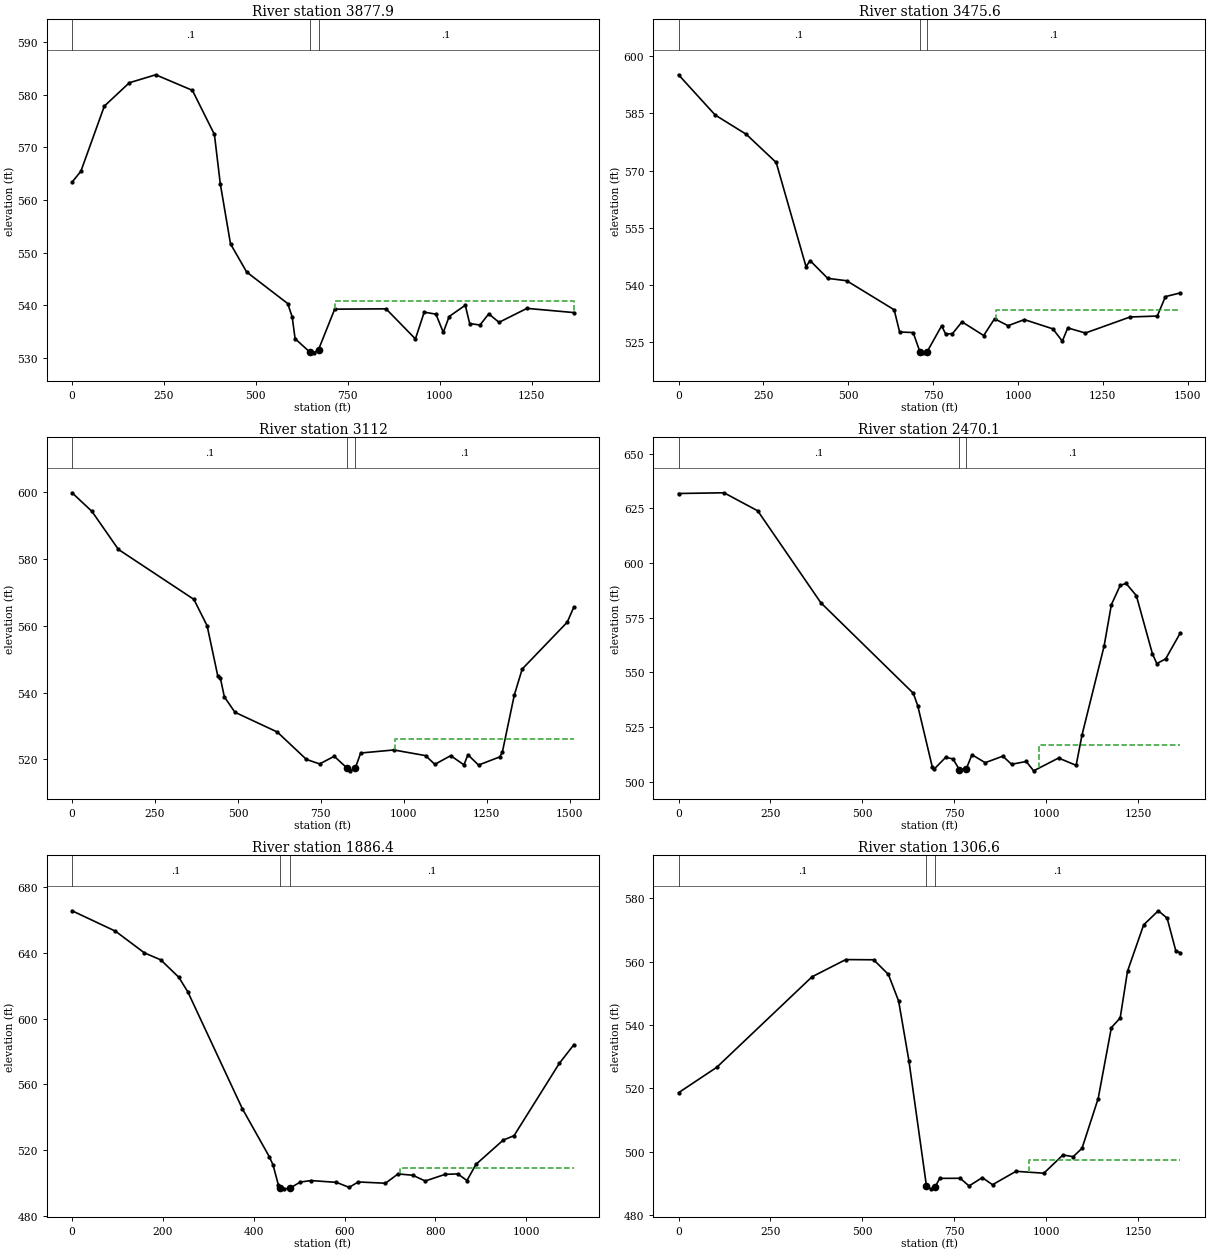
Type RM Length L Ch R = 1 ,3877.9  ,399.1,402.2,405.3
XS GIS Cut Line= 2
     2359816.148      414960.942      2361179.33      414890.507
#Sta/Elev= 30
       0   563.4      24  565.48    87.8  577.87   155.7  582.31   227.5  583.83
   327.3  580.87   387.2  572.48   403.1  563.13     431  551.66     475   546.3
   586.7   540.3   598.7  537.78   606.7  533.62   646.6  531.08   657.5  530.93
   670.5  531.56   714.4  539.24   854.1   539.3     934  533.58   957.9  538.67
   989.8  538.29  1009.8  534.82  1025.8  537.84  1069.6  539.99  1081.6   536.5
  1109.6  536.22  1133.5  538.35  1161.4  536.73  1237.3  539.39    1365  538.59
#Mann= 3 , 0 , 0
       0      .1       0   646.6    .045       0   670.5      .1       0
#XS Ineff= 2 , 0
                          714.64          540.86
Permanent Ineff=
       F       F
Bank Sta=646.6,670.5
XS Rating Curve= 0 ,0
Exp/Cntr=0.3,0.1

Type RM Length L Ch R = 1 ,3475.6  ,355.2,363.6,372.1
XS GIS Cut Line= 2
     2359734.663      415265.897     2361207.572      415392.492
#Sta/Elev= 30
       0  595.12   107.9  584.57   199.8  579.49   287.7  572.11   375.6  544.79
   387.6  546.37   439.5  541.72   495.4  541.09   635.3  533.47   651.3  527.65
   691.2   527.5   711.2  522.44   719.2  522.18   731.9   522.4   775.1  529.27
   787.1  527.09   807.1  527.23   835.1  530.31     899  526.72     931  531.11
   970.9   529.3  1018.9   530.9  1102.8  528.47  1130.7  525.24  1146.7  528.72
  1198.6  527.38  1330.5  531.59  1410.4  531.83  1434.4  536.93  1478.3   537.9
#Mann= 3 , 0 , 0
       0      .1       0   711.2    .045       0   731.9      .1       0
#XS Ineff= 2 , 0
                          935.22          533.33
Permanent Ineff=
       F       F
Bank Sta=711.2,731.9
XS Rating Curve= 0 ,0
Exp/Cntr=0.3,0.1

Type RM Length L Ch R = 1 ,3112    ,640.7,641.9,643.1
XS GIS Cut Line= 2
     2359645.637      415312.149     2361000.598      415984.399
#Sta/Elev= 30
       0  599.86    59.9  594.29   139.7  582.89   367.2  567.93   407.1  560.03
     439   545.1     447  544.39     459  538.74   490.9  534.12   618.6   528.2
   706.4  519.99   746.3  518.64   790.2  520.93   830.1  517.29   838.1  516.57
   854.1   517.5     870  521.91   969.8  522.82  1065.6  521.13  1093.5  518.51
  1141.4  521.12  1181.3  518.36  1193.3  521.39  1225.2   518.3  1289.1  520.74
    1297  522.14    1333  539.25  1356.9  547.07  1492.6  561.09  1512.6  565.64
#Mann= 3 , 0 , 0
       0      .1       0   830.1    .045       0   854.1      .1       0
#XS Ineff= 2 , 0
                          973.21          526.19
Permanent Ineff=
       F       F
Bank Sta=830.1,854.1
XS Rating Curve= 0 ,0
Exp/Cntr=0.3,0.1

Type RM Length L Ch R = 1 ,2470.1  ,582.5,583.7,585
XS GIS Cut Line= 2
     2359370.647      415816.073     2360561.463      416483.293
#Sta/Elev= 30
       0  631.79   123.7  632.12   215.5  623.86   387.2  581.85   638.6  540.52
   650.6  534.87   690.5  506.66   694.5  505.71   726.4  511.17   746.4  510.53
   764.1  505.57   782.3  505.78   798.2  512.42   834.2  508.77   882.1  511.75
     906  508.05   945.9  509.33   965.9  505.05  1033.7   510.9  1081.6  507.56
  1097.6  521.47  1157.5  561.93  1177.4  580.97  1201.4  589.78  1217.3  590.71
  1245.3  585.14  1289.2  558.48  1301.1  554.08  1325.1  556.21    1365  568.08
#Mann= 3 , 0 , 0
       0      .1       0   764.1    .045       0   782.3      .1       0
#XS Ineff= 2 , 0
                          979.76          516.67
Permanent Ineff=
       F       F
Bank Sta=764.1,782.3
XS Rating Curve= 0 ,0
Exp/Cntr=0.3,0.1

Type RM Length L Ch R = 1 ,1886.4  ,579.3,579.8,580.2
XS GIS Cut Line= 3
       2359381.7      416268.734     2359389.363      416427.819
      2360183.15      416941.472
#Sta/Elev= 30
       0  665.57    95.6  653.16   159.3  639.98   195.2  635.75   235.1  625.14
     255   616.2   374.7  545.38   434.5  515.99   442.5  511.06   454.5  498.63
   458.5  496.83   466.4  496.57   479.2  496.87   502.4   500.7   526.3   501.6
   582.1   500.5   610.1  497.45     630  500.75   689.9  499.98   717.8  505.62
   749.7  504.85   777.6  501.34   821.5  505.39   849.4  505.63   869.4  501.62
   889.3  511.45   949.2  526.19   973.1  528.89  1072.8  572.83  1104.8  584.17
#Mann= 3 , 0 , 0
       0      .1       0   458.5    .045       0   479.2      .1       0
#XS Ineff= 2 , 0
                          722.44          509.52
Permanent Ineff=
       F       F
Bank Sta=458.5,479.2
XS Rating Curve= 0 ,0
Exp/Cntr=0.3,0.1

Type RM Length L Ch R = 1 ,1306.6  ,701.2,713.7,726.2
XS GIS Cut Line= 2
      2358715.26      416656.627     2359845.322      417422.253
#Sta/Elev= 30
       0  518.62   103.8  526.62   363.2  555.19     455  560.62   530.8  560.55
   570.8  555.94   598.7  547.55   626.6  528.76   674.5  489.11   686.5   488.3
   697.9   488.9   710.4   491.6   766.3  491.63   790.3   489.2   826.2  491.85
   854.1   489.6     918  493.83   993.8  493.23  1045.7  498.99  1073.6  498.44
  1097.6  501.09  1141.5  516.77  1177.4  539.15  1201.4  542.19  1221.3  556.94
  1265.2  571.56  1305.1  576.01  1329.1  573.69    1353  563.26    1365  562.81
#Mann= 3 , 0 , 0
       0      .1       0   674.5    .045       0   697.9      .1       0
#XS Ineff= 2 , 0
                          952.06          497.26
Permanent Ineff=
       F       F
Bank Sta=674.5,697.9
XS Rating Curve= 0 ,0
Exp/Cntr=0.3,0.1

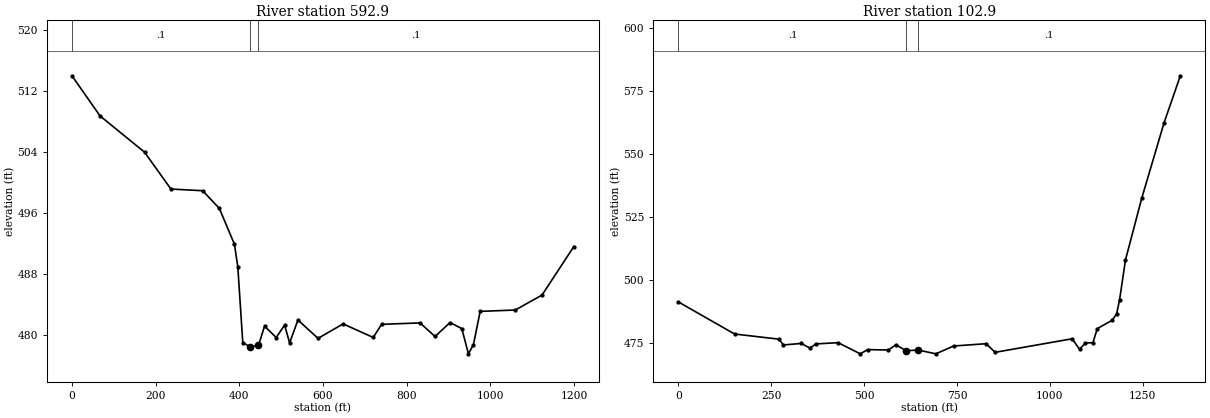
Type RM Length L Ch R = 1 ,592.9   ,487.1,489.9,492.7
XS GIS Cut Line= 3
     2358721.109      416849.897     2358560.519      417023.508
     2358938.123      417908.925
#Sta/Elev= 30
       0  513.95      67  508.69   173.4  503.93   236.5  499.09   312.4  498.87
   352.3  496.54   388.3  491.84   396.3  488.89   408.2  478.95   425.1  478.41
  445.68  478.57   460.2   481.1   488.1  479.61   508.1  481.25   520.1   478.9
     540  481.91     588   479.5   647.9   481.4   719.8  479.62   739.8  481.34
   831.6  481.53   867.6  479.75   903.5  481.58   931.5  480.78   947.4  477.47
   959.4  478.69   975.4  483.04  1059.3  483.22  1123.2  485.18  1199.1  491.54
#Mann= 3 , 0 , 0
       0      .1       0   425.1    .045       0  445.68      .1       0
Bank Sta=425.1,445.68
XS Rating Curve= 0 ,0
Exp/Cntr=0.3,0.1

Type RM Length L Ch R = 1 ,102.9   ,113.9,102.9,92
XS GIS Cut Line= 3
     2358404.269      416871.598     2358169.894      417301.286
     2358482.394      418104.237
#Sta/Elev= 30
       0  491.28   151.2  478.56   270.6  476.53   282.5  474.22   330.3  474.83
   354.2  472.98   370.1  474.64   429.8  475.13   489.4   470.7   509.4  472.38
   565.2  472.22   585.2  474.29   613.1  471.93     645  472.21   692.9  470.71
   740.8  473.81   828.5  474.72   852.4   471.3  1059.9  476.68  1079.8  472.51
  1095.8  475.04  1115.7   475.1  1127.7  480.73  1167.6  484.03  1179.5  486.54
  1187.5  492.09  1203.5  508.01  1247.4  532.55  1307.2  562.33  1351.1  581.06
#Mann= 3 , 0 , 0
       0      .1       0   613.1    .045       0     645      .1       0
Bank Sta=613.1,645
XS Rating Curve= 0 ,0
Exp/Cntr=0.3,0.1

Chan Stop Cuts=-1
Use User Specified Reach Order=0
Composite Channel Slope=5